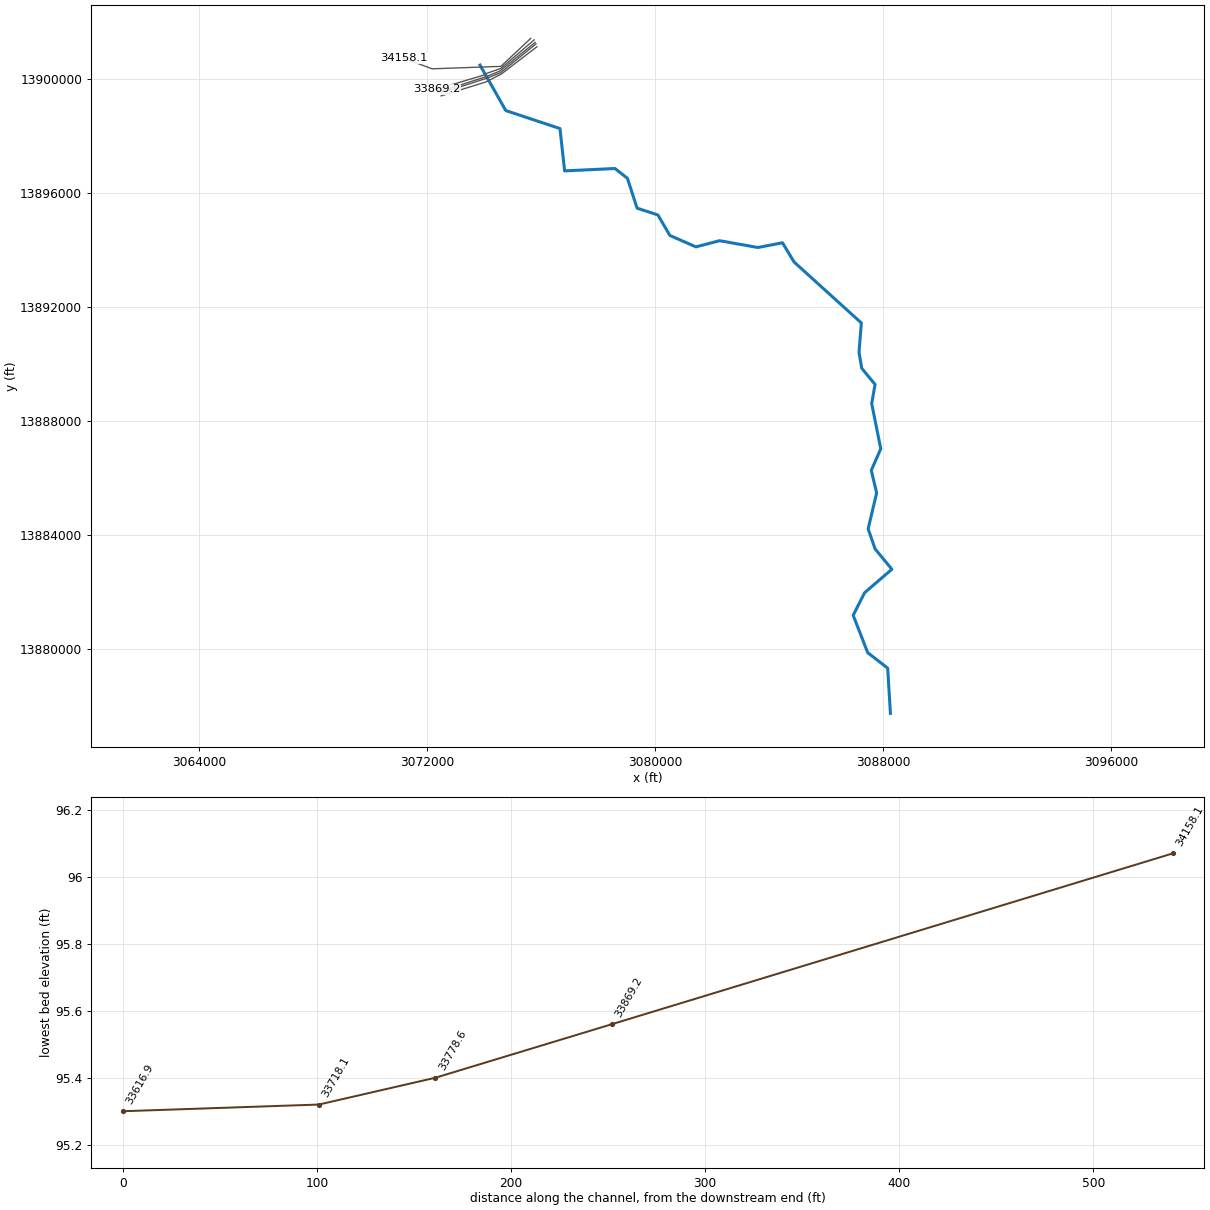
--- E121-00-00.prj (project) ---

Proj Title=E121-00-00 LOMR
Current Plan=p01
Default Exp/Contr=0.3,0.1
English Units
Geom File=g01
Flow File=f01
Flow File=f02
Plan File=p01
Plan File=p02
Y Axis Title=Elevation
X Axis Title(PF)=Main Channel Distance
X Axis Title(XS)=Station
BEGIN DESCRIPTION:
HCFCD MODEL SUMMARY METADATA
The purpose of this summary is to document the high points of hydrologic and hydraulic models filed within the HCFCD Model and Map Management (M3) system.  The document includes references to the project that prompted the creation or update of the model.
DESCRIPTION OF PROJECT:
The following model was the hydraulic model which represented the effective condition of Harris County's watersheds.
PURPOSE OF PROJECT:
Development of effective models to support the National Flood Insurance Program.
HCFCD Watershed Unit ID: E
M3 Study Identifier: 2007_Effective_E
Engineer: HCFCD
Project Name: EffectiveFEMA Study for watershed White Oak Bayou (E)
Study Completion Date: 6/18/2007
FEMA Case Number: [No Data]
FEMA Approval Date: [No Date in Database]
Vertical Datum: NAVD 1988
Datum Note: 2001 ADJ
HYDRAULICS
HCFCD Unit No.:  E121-00-00
Hydraulic Program Name: HEC-RAS
Hydraulic Program Version: 4.0
Steady Hydraulic Model: Yes
Unsteady Hydraulic Model: No
Update1:
The effective FEMA hydraulic model for unit number E121-00-00 has been updated by FEMA LOMR 09-06-2519P with an effective date of 12/31/2009.
Update2:
The effective FEMA hydraulic model for unit number E121-00-00 has been updated by FEMA LOMR 10-06-1715X with an effective date of 4/30/2010.
Update2:
The effective FEMA hydraulic model for unit number E121-00-00 has been updated by FEMA LOMR 16-06-0527P with an effective date of 11/04/2016.
Note: This LOMR was run using HEC-RAS 4.0 and all future submittals on E121-00-00 will need to be submitted using this version.
END DESCRIPTION:
DSS File=dss
DSS Export Rating Curves= 0
DSS Export Rating Curve Sorted= 0
DSS Export Volume Flow Curves= 0
DXF Filename=E1210000_VOGEL_IMPROV.
DXF OffsetX= 0
DXF OffsetY= 0
DXF ScaleX= 1
DXF ScaleY= 10

--- E121-00-00.p01 (plan) ---

Plan Title=Effective Multi-Profile 2016
Version=Version 3.0.1  May 2012
Short Identifier=EFF+LOMR MP
Geom File=g01
Flow File=f01
Subcritical Flow
K Sum by GR= 0
Std Step Tol= 0.01
Critical Tol= 0.01
Num of Std Step Trials= 20
Max Error Tol= 0.3
Flow Tol Ratio= 0.001
Split Flow NTrial= 30
Split Flow Tol= 0.02
Split Flow Ratio= 0.02
Log Output Level= 0
Friction Slope Method= 1
Unsteady Friction Slope Method= 2
Parabolic Critical Depth
Global Vel Dist= 0 , 0 , 0
Global Log Level= 0
CheckData=True
Encroach Param=-1 ,0,0, 0
BEGIN DESCRIPTION:
FEMA Effective Multi-Profile 2007 + LOMR 09-06-2519P + 10-06-1715X + 16-06-0527P
END DESCRIPTION:
Computation Interval=1HOUR
Output Interval=1HOUR
Run HTab= 0
Run UNet= 0
Run PostProcess= 0
UNET Theta= 1
UNET ZTol= 0.02
UNET ZSATol= 0.1
UNET MxIter= 20
UNET MaxInSteps= 20
UNET DtIC= 0
UNET DtMin= 0
UNET MaxCRTS= 20
UNET WFStab= 2
UNET SFStab= 1
UNET WFX= 1
UNET SFX= 1
UNET Convert EG Bridges=-1
UNET Use Existing IB Tables=-1
Instantaneous Interval=1HOUR
DSS File=dss
Write IC File= 0
IC Time=0
Write Velocity= 0
Write Detailed= 0

--- E121-00-00.p02 (plan) ---

Plan Title=Effective Floodway 2016
Program Version=4.00
Short Identifier=EFF+LOMR FW
Geom File=g01
Flow File=f02
Subcritical Flow
K Sum by GR= 0
Std Step Tol= 0.01
Critical Tol= 0.01
Num of Std Step Trials= 20
Max Error Tol= 0.3
Flow Tol Ratio= 0.001
Split Flow NTrial= 30
Split Flow Tol= 0.02
Split Flow Ratio= 0.02
Log Output Level= 0
Friction Slope Method= 1
Unsteady Friction Slope Method= 2
Unsteady Bridges Friction Slope Method= 1
Parabolic Critical Depth
Global Vel Dist= 0 , 0 , 0
Global Log Level= 0
CheckData=True
Encroach Param=-1 ,0,0, 3
Encroach River=E121-00-00
Encroach Reach=E121-00-00_0004
Encroach Node=34158.1
       14954.685 5045.32       14954.685 5045.32
Encroach Node=33869.2
       1  4944.3  5054.3       1  4944.3  5054.3
Encroach Node=33778.6
       1  4974.3  5025.7       1  4974.3  5025.7
Encroach Node=33718.1
       1  4974.3  5025.7       1  4974.3  5025.7
Encroach Node=33616.9
       1  4946.1  5056.1       1  4946.1  5056.1
Encroach Node=32909.4
       1  4965.1  5040.8       1  4965.1  5040.8
Encroach Node=31983.4
       1  4948.6  5048.6       1  4948.6  5048.6
Encroach Node=31871.7
       1  4971.4  5028.7       1  4971.4  5028.7
Encroach Node=31810.8
       1  4971.4  5028.7       1  4971.4  5028.7
Encroach Node=31706.9
       1  4948.7  5048.7       1  4948.7  5048.7
Encroach Node=31266.8
       1  4958.2  5036.5       1  4958.2  5036.5
Encroach Node=30239.7
       1  4959.3  5049.3       1  4959.3  5049.3
Encroach Node=30122.1
       1  4978.5  5022.2       1  4978.5  5022.2
Encroach Node=30060.2
       1  4978.5  5022.2       1  4978.5  5022.2
Encroach Node=29959.3
       1  4961.3  5054.6       1  4961.3  5054.6
Encroach Node=29290.4
       1    4964    5046       1    4964    5046
Encroach Node=28205.5
       1  4960.5  5044.6       1  4960.5  5044.6
Encroach Node=27432.9
       1  4956.4  5054.6       1  4956.4  5054.6
Encroach Node=27290.9
       1    4935  5055.5       1    4935  5055.5
Encroach Node=27179.8
       1    4935  5055.5       1    4935  5055.5
Encroach Node=27107.6
       1    4935  5050.3       1    4935  5050.3
Encroach Node=26749.01
       1 4925.46 5038.46       1 4925.46 5038.46
Encroach Node=26519.9
       1 4947.35 5088.89       1 4947.35 5088.89
Encroach Node=26466.65
       1 4931.65 5081.67       1 4931.65 5081.67
Encroach Node=26072.3
       1 4915.85 5082.35       1 4915.85 5082.35
Encroach Node=25765.4
       1 4908.28 5057.58       1 4908.28 5057.58
Encroach Node=25599.62
       1 4923.59 5061.13       1 4923.59 5061.13
Encroach Node=25378.56
       1 4916.33 5060.87       1 4916.33 5060.87
Encroach Node=24938.1
       1  4912.4 5137.12       1  4912.4 5137.12
Encroach Node=24097.4
       1  4928.7 5286.52       1  4928.7 5286.52
Encroach Node=23986.1
       1 4904.26  5226.9       1 4904.26  5226.9
Encroach Node=23925.6
       1 4909.26  5231.9       1 4909.26  5231.9
Encroach Node=23711.2
       1    4895    5182       1    4895    5182
Encroach Node=23443.5
       1  4955.4 5143.58       1  4955.4 5143.58
Encroach Node=23424.2
       1  4957.9 5144.16       1  4957.9 5144.16
Encroach Node=23402.9
       1  4952.9 5139.16       1  4952.9 5139.16
Encroach Node=23353.5
       1  4939.9 5132.16       1  4939.9 5132.16
Encroach Node=23204.2
       1 4862.64 5093.99       1 4862.64 5093.99
Encroach Node=23122
       1 4865.76 5111.75       1 4865.76 5111.75
Encroach Node=23042.6
       1 4865.76 5121.75       1 4865.76 5121.75
Encroach Node=22918.5
       1 4867.27 5103.95       1 4867.27 5103.95
Encroach Node=22694.1
       1 4855.21  5079.9       1 4855.21  5079.9
Encroach Node=21398.1
       1 4903.07 5088.13       1 4903.07 5088.13
Encroach Node=20863.9
       1 4928.99 5075.53       1 4928.99 5075.53
Encroach Node=20724.2
       1  4947.1  5053.9       1  4947.1  5053.9
Encroach Node=20600.8
       1  4947.1  5053.9       1  4947.1  5053.9
Encroach Node=20407
       1 4970.98  5047.6       1 4970.98  5047.6
Encroach Node=19742.6
       1  4984.3    5035       1  4984.3    5035
Encroach Node=19032
       1  4950.2  5040.2       1  4950.2  5040.2
Encroach Node=18886.6
       1 4964.11 5035.88       1 4964.11 5035.88
Encroach Node=18803.8
       1 4964.11 5035.88       1 4964.11 5035.88
Encroach Node=18514.7
       1  4934.3  5054.3       1  4934.3  5054.3
Encroach Node=17463.3
       1  4972.8 5037.22       1  4972.8 5037.22
Encroach Node=16453.3
       1    4974  5021.7       1    4974  5021.7
Encroach Node=15719.1
       1  4933.5  5033.5       1  4933.5  5033.5
Encroach Node=15528
       1    4961 5023.89       1    4961 5023.89
Encroach Node=15462.6
       1    4961 5023.89       1    4961 5023.89
Encroach Node=15273.1
       1  4938.3  5058.3       1  4938.3  5058.3
Encroach Node=14510.3
       1  4938.8  5044.8       1  4938.8  5044.8
Encroach Node=13784.6
       1  4899.3  5075.4       1  4899.3  5075.4
Encroach Node=13667.8
       1 4950.55 5049.45       1 4950.55 5049.45
Encroach Node=13523.1
       1 4950.55 5049.45       1 4950.55 5049.45
Encroach Node=13340.7
       1  4931.9  5129.8       1  4931.9  5129.8
Encroach Node=12430.3
       1  4932.5  5042.8       1  4932.5  5042.8
Encroach Node=11832.1
       1    4972  5074.6       1    4972  5074.6
Encroach Node=11338.6
       1  4936.9    5047       1  4936.9    5047
Encroach Node=10340.5
       1  4939.7  5048.3       1  4939.7  5048.3
Encroach Node=9425.5
       1  4947.7  5093.1       1  4947.7  5093.1
Encroach Node=9310.1
       1  4948.7  5035.6       1  4948.7  5035.6
Encroach Node=9247
       1  4948.7  5035.6       1  4948.7  5035.6
Encroach Node=9160.3
       1  4951.6  5133.4       1  4951.6  5133.4
Encroach Node=8652.7
       1 4948.56 5077.48       1 4948.56 5077.48
Encroach Node=8464.9
       1 4896.95 5043.51       1 4896.95 5043.51
Encroach Node=8337.6
       1 4869.17 5019.69       1 4869.17 5019.69
Encroach Node=8259.1
       1 4871.39 5023.46       1 4871.39 5023.46
Encroach Node=8126.2
       1 4883.56  5033.4       1 4883.56  5033.4
Encroach Node=8017.2
       1 4838.87 4993.17       1 4838.87 4993.17
Encroach Node=6978.8
       1 4849.37 5016.06       1 4849.37 5016.06
Encroach Node=6788
       1 4832.41 4992.89       1 4832.41 4992.89
Encroach Node=6720.6
       1    4842 5002.48       1    4842 5002.48
Encroach Node=6598.8
       1 4867.75 5031.32       1 4867.75 5031.32
Encroach Node=5908.6
       1 4872.33 5024.57       1 4872.33 5024.57
Encroach Node=5736.2
       1 4895.28 5065.29       1 4895.28 5065.29
Encroach Node=5613.6
       1 4906.54  5078.8       1 4906.54  5078.8
Encroach Node=5478.2
       1 4911.19 5091.42       1 4911.19 5091.42
Encroach Node=5408.5
       1 4904.77    5085       1 4904.77    5085
Encroach Node=5198.4
       1 4883.32 5047.93       1 4883.32 5047.93
Encroach Node=5068.7
       1 4873.85 5047.48       1 4873.85 5047.48
Encroach Node=5035.1
       1 4899.06 5067.58       1 4899.06 5067.58
Encroach Node=4875.7
       1 4925.34 5118.54       1 4925.34 5118.54
Encroach Node=4509.4
       1 4973.05 5138.55       1 4973.05 5138.55
Encroach Node=3842.7
       1 4917.84 5096.55       1 4917.84 5096.55
Encroach Node=3619.3
       1 4864.15 5029.56       1 4864.15 5029.56
Encroach Node=3583.9
       1 4860.03 5023.12       1 4860.03 5023.12
Encroach Node=3470.9
       1 4847.98 5023.15       1 4847.98 5023.15
Encroach Node=2901.9
       1 4967.18  5043.2       1 4967.18  5043.2
Encroach Node=2812.9
       1 4974.33 5052.35       1 4974.33 5052.35
Encroach Node=2699.7
       1 4978.01 5056.03       1 4978.01 5056.03
Encroach Node=2604.8
       1 4964.64 5082.64       1 4964.64 5082.64
Encroach Node=2193.7
       1 4982.32 5126.71       1 4982.32 5126.71
Encroach Node=1614.7
       1  4933.5 5129.28       1  4933.5 5129.28
Encroach Node=1337.6
       1 4875.36 5121.16       1 4875.36 5121.16
Encroach Node=1235.4
       1 4865.94 5114.08       1 4865.94 5114.08
Encroach Node=930.1
       1 4875.46 5101.24       1 4875.46 5101.24
Encroach Node=653.8
       1 4841.28 5020.92       1 4841.28 5020.92
Encroach Node=577.6
       1 4848.05 5027.58       1 4848.05 5027.58
Encroach Node=438
       1 4862.78  5042.6       1 4862.78  5042.6
BEGIN DESCRIPTION:
FEMA Effective Multi-Profile 2007 + LOMR 09-06-2519P + 10-06-1715X + 16-06-0527P
END DESCRIPTION:
Computation Interval=1HOUR
Output Interval=1HOUR
Run HTab= 0
Run UNet= 0
Run PostProcess= 0
Run WQNet= 0
UNET Theta= 1
UNET Theta Warmup= 1
UNET ZTol= 0.02
UNET ZSATol= 0.1
UNET MxIter= 20
UNET MaxInSteps= 20
UNET DtIC= 0
UNET DtMin= 0
UNET MaxCRTS= 20
UNET WFStab= 2
UNET SFStab= 1
UNET WFX= 1
UNET SFX= 1
UNET DSS MLevel= 4
UNET DZMax Abort= 100
UNET Convert EG Bridges=-1
UNET Use Existing IB Tables=-1
UNET Froude Reduction=False
UNET Froude Limit= 1
UNET Froude Power= 10
UNET Time Slicing=0,0, 5
Instantaneous Interval=1HOUR
DSS File=dss
Write IC File= 0
IC Time=0,,
Echo Input=False
Echo Output=False
Write Detailed= 0
Detailed Automatic Start=False, 10
WQ ULTIMATE=-1
WQ Max Comp Step=1HOUR
WQ Output Interval=15MIN
WQ Output Selected Increments= 0
WQ Output face flow=0
WQ Output face velocity=0
WQ Output face area=0
WQ Output face dispersion=0
WQ Output cell volume=0
WQ Output cell surface area=0
WQ Output cell continuity=0
WQ Output face conc=0
WQ Output face dconc_dx=0
WQ Output face courant=0
WQ Output face peclet=0
WQ Output face adv mass=0
WQ Output face disp mass=0
WQ Output cell mass=0
WQ Output cell source sink temp=0
WQ Output cell source sink nsm=0
WQ Output MaxMinRange=-1
WQ Daily Max Min Mean=-1
WQ Daily Range=0
WQ Daily Time=0
WQ Create Restart=0
WQ Fixed Restart=0
WQ System Summary=False
Sorting and Armoring Iterations= 10
XS Update Threshold= 0.02
Hydraulics Update Threshold= 0.02
Energy Slope Method= 1
Volume Change Method= 0
XS Weighting Method= 0
Number of US Weighted Cross Sections= 1
Number of DS Weighted Cross Sections= 1
Upstream XS Weight=0.25
Main XS Weight=0.5
Downstream XS Weight=0.25
Number of DS XS's Weighted with US Boundary= 1
Upstream Boundary Weight= 1
Weight of XSs Associated with US Boundary= 0
Number of US XS's Weighted with DS Boundary= 1
Downstream Boundary Weight= 0.5
Weight of XSs Associated with DS Boundary= 0.5
Sediment Output Level= 4
Mass or Volume Output= 0
Output Increment Type= 1
Profile and TS Output Increment= 10
XS Output Flag= 0
XS Output Increment= 10
Disregard all LS=0
Disregard all Conn=0
Disregard all Breaches=0
Disregard all Pumps=0

--- E121-00-00.f01 (steady flow) ---

Flow Title=Effective Multi-Profile 2016
Program Version=4.00
Number of Profiles= 4
Profile Names=10PCT_10yr,2PCT_50yr,1PCT_100yr,0.2PCT_500yr
River Rch & RM=E121-00-00,E121-00-00_0004 ,34158.1
     304     460     539     773
River Rch & RM=E121-00-00,E121-00-00_0004 ,33616.9
     322     486     570     817
River Rch & RM=E121-00-00,E121-00-00_0004 ,32909.4
     346     523     613     880
River Rch & RM=E121-00-00,E121-00-00_0004 ,31983.4
     354     534     627     899
River Rch & RM=E121-00-00,E121-00-00_0004 ,31706.9
     366     553     649     931
River Rch & RM=E121-00-00,E121-00-00_0004 ,31266.8
     397     600     704    1010
River Rch & RM=E121-00-00,E121-00-00_0004 ,30239.7
     406     614     720    1032
River Rch & RM=E121-00-00,E121-00-00_0004 ,29959.3
     428     647     759    1088
River Rch & RM=E121-00-00,E121-00-00_0004 ,29290.4
     467     705     827    1186
River Rch & RM=E121-00-00,E121-00-00_0004 ,28205.5
     496     749     879    1261
River Rch & RM=E121-00-00,E121-00-00_0004 ,27432.9
     509     769     902    1293
River Rch & RM=E121-00-00,E121-00-00_0004 ,27107.6
     533     805     945    1355
River Rch & RM=E121-00-00,E121-00-00_0004 ,26519.9
     566     855    1003    1438
River Rch & RM=E121-00-00,E121-00-00_0004 ,25765.4
     604     913    1071    1535
River Rch & RM=E121-00-00,E121-00-00_0004 ,24938.1
     646     976    1144    1641
River Rch & RM=E121-00-00,E121-00-00_0004 ,24097.4
     666    1006    1180    1692
River Rch & RM=E121-00-00,E121-00-00_0004 ,23711.2
     693    1047    1228    1761
River Rch & RM=E121-00-00,E121-00-00_0004 ,23204.2
     722    1090    1279    1834
River Rch & RM=E121-00-00,E121-00-00_0004 ,22694.1
     799    1208    1417    2032
River Rch & RM=E121-00-00,E121-00-00_0004 ,21398.1
     834    1260    1478    2119
River Rch & RM=E121-00-00,E121-00-00_0004 ,20863.9
     865    1306    1532    2197
River Rch & RM=E121-00-00,E121-00-00_0004 ,20407
     911    1377    1615    2316
River Rch & RM=E121-00-00,E121-00-00_0004 ,19742.6
     964    1456    1708    2450
River Rch & RM=E121-00-00,E121-00-00_0004 ,19032
     975    1473    1728    2478
River Rch & RM=E121-00-00,E121-00-00_0004 ,18886.6
    1004    1517    1779    2552
River Rch & RM=E121-00-00,E121-00-00_0004 ,18514.7
    1091    1649    1934    2773
River Rch & RM=E121-00-00,E121-00-00_0004 ,17463.3
    1182    1786    2095    3004
River Rch & RM=E121-00-00,E121-00-00_0004 ,16453.3
    1253    1892    2220    3183
River Rch & RM=E121-00-00,E121-00-00_0004 ,15719.1
    1298    1960    2299    3298
River Rch & RM=E121-00-00,E121-00-00_0004 ,15273.1
    1378    2082    2442    3503
River Rch & RM=E121-00-00,E121-00-00_0004 ,14510.3
    1480    2239    2626    3761
River Rch & RM=E121-00-00,E121-00-00_0004 ,13340.7
    1565    2369    2778    3975
River Rch & RM=E121-00-00,E121-00-00_0004 ,12430.3
    1672    2535    2972    4248
River Rch & RM=E121-00-00,E121-00-00_0004 ,11338.6
    1777    2696    3161    4515
River Rch & RM=E121-00-00,E121-00-00_0004 ,10340.5
    1879    2854    3345    4773
River Rch & RM=E121-00-00,E121-00-00_0004 ,9425.5
    1992    3029    3550    5060
River Rch & RM=E121-00-00,E121-00-00_0004 ,8464.9
    2047    3114    3650    5200
River Rch & RM=E121-00-00,E121-00-00_0004 ,8017.2
    2181    3321    3892    5540
River Rch & RM=E121-00-00,E121-00-00_0004 ,6978.8
    2328    3548    4159    5912
River Rch & RM=E121-00-00,E121-00-00_0004 ,5908.6
    2480    3783    4433    6296
River Rch & RM=E121-00-00,E121-00-00_0004 ,4875.7
    2641    4033    4726    6705
River Rch & RM=E121-00-00,E121-00-00_0004 ,3842.7
    2848    4354    5102    7229
River Rch & RM=E121-00-00,E121-00-00_0004 ,2604.8
    3076    4710    5518    7809
River Rch & RM=E121-00-00,E121-00-00_0004 ,1337.6
    3207    4914    5757    8141
River Rch & RM=E121-00-00,E121-00-00_0004 ,653.8
    3250    4980    5834    8248
Boundary for River Rch & Prof#=E121-00-00,E121-00-00_0004 , 1
Up Type= 0
Dn Type= 3
Dn Slope=0.0012
Boundary for River Rch & Prof#=E121-00-00,E121-00-00_0004 , 2
Up Type= 0
Dn Type= 3
Dn Slope=0.0012
Boundary for River Rch & Prof#=E121-00-00,E121-00-00_0004 , 3
Up Type= 0
Dn Type= 3
Dn Slope=0.0012
Boundary for River Rch & Prof#=E121-00-00,E121-00-00_0004 , 4
Up Type= 0
Dn Type= 3
Dn Slope=0.0012
DSS Import GetInterval= 0
DSS Import GetPeak= 0
DSS Import FillOption= 0

--- E121-00-00.f02 (steady flow) ---

Flow Title=Effective Floodway 2016
Program Version=4.00
Number of Profiles= 2
Profile Names=1PCT_100yr,1PCTFloodway_100yr
River Rch & RM=E121-00-00,E121-00-00_0004 ,34158.1
     539     539
River Rch & RM=E121-00-00,E121-00-00_0004 ,33616.9
     570     570
River Rch & RM=E121-00-00,E121-00-00_0004 ,32909.4
     613     613
River Rch & RM=E121-00-00,E121-00-00_0004 ,31983.4
     627     627
River Rch & RM=E121-00-00,E121-00-00_0004 ,31706.9
     649     649
River Rch & RM=E121-00-00,E121-00-00_0004 ,31266.8
     704     704
River Rch & RM=E121-00-00,E121-00-00_0004 ,30239.7
     720     720
River Rch & RM=E121-00-00,E121-00-00_0004 ,29959.3
     759     759
River Rch & RM=E121-00-00,E121-00-00_0004 ,29290.4
     827     827
River Rch & RM=E121-00-00,E121-00-00_0004 ,28205.5
     879     879
River Rch & RM=E121-00-00,E121-00-00_0004 ,27432.9
     902     902
River Rch & RM=E121-00-00,E121-00-00_0004 ,27107.6
     945     945
River Rch & RM=E121-00-00,E121-00-00_0004 ,26519.9
    1003    1003
River Rch & RM=E121-00-00,E121-00-00_0004 ,25765.4
    1071    1071
River Rch & RM=E121-00-00,E121-00-00_0004 ,24938.1
    1144    1144
River Rch & RM=E121-00-00,E121-00-00_0004 ,24097.4
    1180    1180
River Rch & RM=E121-00-00,E121-00-00_0004 ,23711.2
    1228    1228
River Rch & RM=E121-00-00,E121-00-00_0004 ,23204.2
    1279    1279
River Rch & RM=E121-00-00,E121-00-00_0004 ,22694.1
    1417    1417
River Rch & RM=E121-00-00,E121-00-00_0004 ,21398.1
    1478    1478
River Rch & RM=E121-00-00,E121-00-00_0004 ,20863.9
    1532    1532
River Rch & RM=E121-00-00,E121-00-00_0004 ,20407
    1615    1615
River Rch & RM=E121-00-00,E121-00-00_0004 ,19742.6
    1708    1708
River Rch & RM=E121-00-00,E121-00-00_0004 ,19032
    1728    1728
River Rch & RM=E121-00-00,E121-00-00_0004 ,18886.6
    1779    1779
River Rch & RM=E121-00-00,E121-00-00_0004 ,18514.7
    1934    1934
River Rch & RM=E121-00-00,E121-00-00_0004 ,17463.3
    2095    2095
River Rch & RM=E121-00-00,E121-00-00_0004 ,16453.3
    2220    2220
River Rch & RM=E121-00-00,E121-00-00_0004 ,15719.1
    2299    2299
River Rch & RM=E121-00-00,E121-00-00_0004 ,15273.1
    2442    2442
River Rch & RM=E121-00-00,E121-00-00_0004 ,14510.3
    2626    2626
River Rch & RM=E121-00-00,E121-00-00_0004 ,13340.7
    2778    2778
River Rch & RM=E121-00-00,E121-00-00_0004 ,12430.3
    2972    2972
River Rch & RM=E121-00-00,E121-00-00_0004 ,11338.6
    3161    3161
River Rch & RM=E121-00-00,E121-00-00_0004 ,10340.5
    3345    3345
River Rch & RM=E121-00-00,E121-00-00_0004 ,9425.5
    3550    3550
River Rch & RM=E121-00-00,E121-00-00_0004 ,8464.9
    3650    3650
River Rch & RM=E121-00-00,E121-00-00_0004 ,8017.2
    3892    3892
River Rch & RM=E121-00-00,E121-00-00_0004 ,6978.8
    4159    4159
River Rch & RM=E121-00-00,E121-00-00_0004 ,5908.6
    4433    4433
River Rch & RM=E121-00-00,E121-00-00_0004 ,4875.7
    4726    4726
River Rch & RM=E121-00-00,E121-00-00_0004 ,3842.7
    5102    5102
River Rch & RM=E121-00-00,E121-00-00_0004 ,2604.8
    5518    5518
River Rch & RM=E121-00-00,E121-00-00_0004 ,1337.6
    5757    5757
River Rch & RM=E121-00-00,E121-00-00_0004 ,653.8
    5834    5834
Boundary for River Rch & Prof#=E121-00-00,E121-00-00_0004 , 1
Up Type= 0
Dn Type= 3
Dn Slope=0.0012
Boundary for River Rch & Prof#=E121-00-00,E121-00-00_0004 , 2
Up Type= 0
Dn Type= 1
Dn Known WS=69.45
DSS Import GetInterval= 0
DSS Import GetPeak= 0
DSS Import FillOption= 0

--- E121-00-00.g01 (geometry) ---

Geom Title=E121-00-00 2016
Program Version=4.00

River Reach=E121-00-00      ,E121-00-00_0004
Reach XY= 30
3073856.16000003     13900472.413074760.67000003     13898879.52
3076661.71999998     13898248.453076824.04000002     13896765.81
      3078589.67     13896849.143079027.17000002     13896507.13
3079366.58000004     13895459.393080095.74000002     13895222.41
3080515.88000001     13894504.523081429.08000001     13894104.35
3082259.81000003     13894319.633083602.69000001     13894081.78
3084467.27000003     13894246.713084874.39000002     13893572.23
3087233.76000004     13891437.683087150.42999999     13890412.51
      3087245.05     13889852.613087714.67000003      13889282.3
3087595.74000004      13888611.33087914.31999999     13887028.83
3087581.84999999     13886272.763087769.36000004     13885484.56
3087471.50813204 13884223.743835 3087717.133135813883519.1672644
3088303.9027389113882808.58375393087347.5826654113881986.7811455
3086946.51398677 13881194.9744933087456.15046288   13879886.9445
3088156.3834723413879343.5689482 3088253.332465613877759.0970113

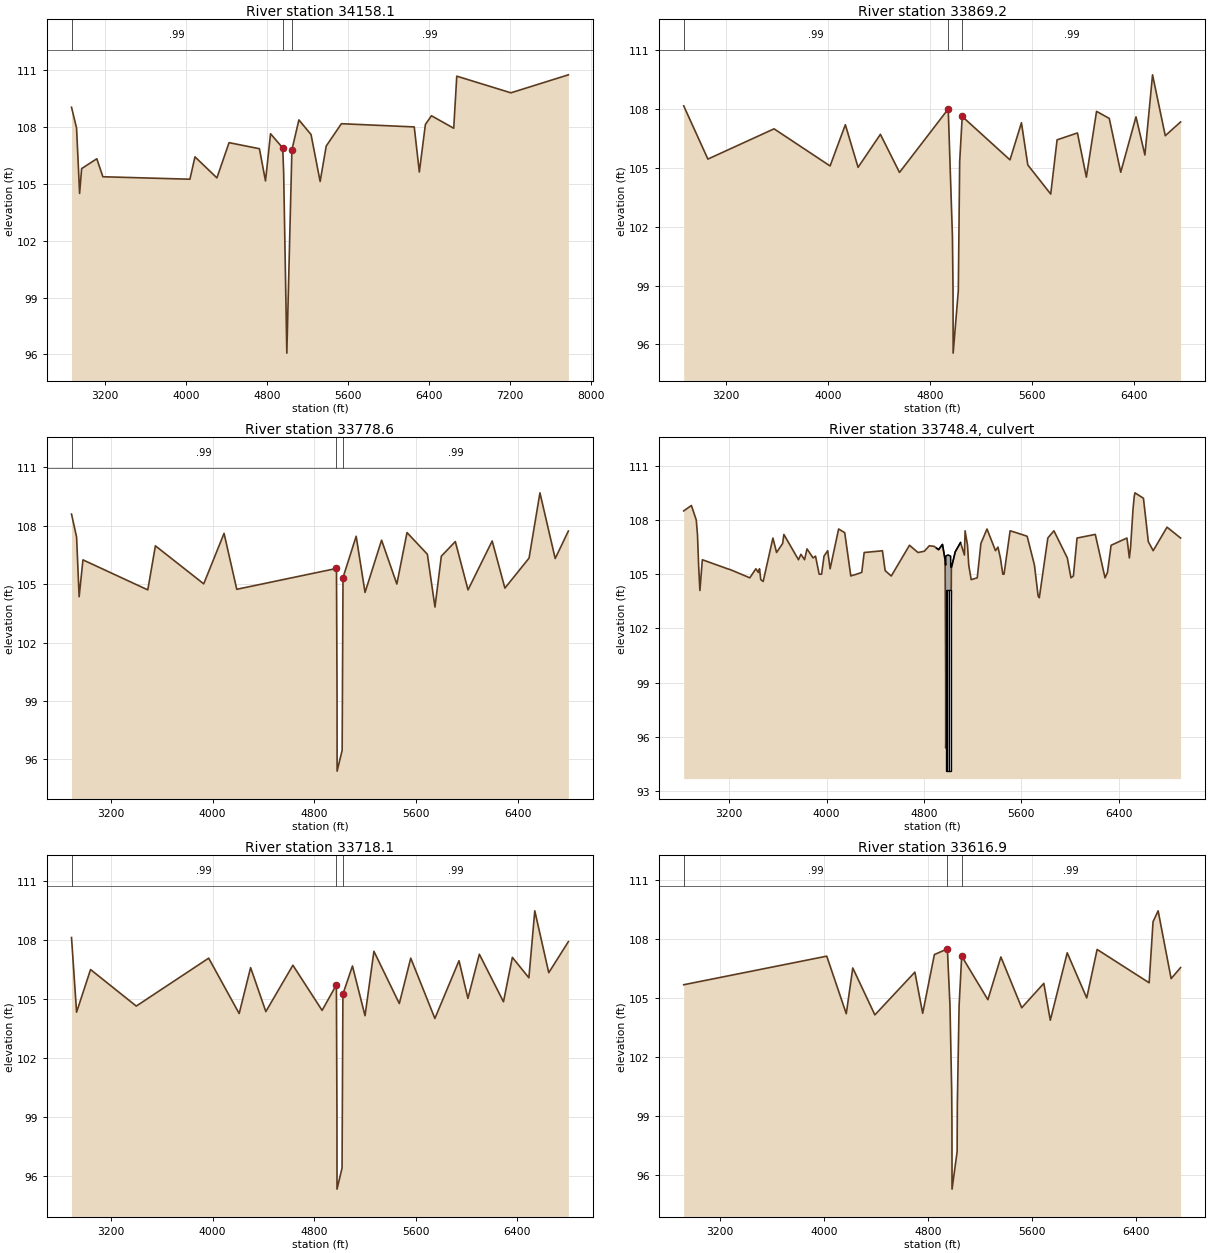
Type RM Length L Ch R = 1 ,34158.1 ,271,289,315
BEGIN DESCRIPTION:
Cross Section X23.5; skew
END DESCRIPTION:
XS GIS Cut Line= 4
      3075637.16     13901410.06       3074588.7     13900427.72
      3072175.34     13900342.71      3071183.55     13900711.09
#Sta/Elev= 30
  2867.5  109.05  2917.5  107.95  2947.5   104.5  2967.5  105.81  3117.5  106.33
  3177.5  105.38  4037.5  105.25  4087.5  106.43  4304.3  105.32  4424.3  107.18
  4724.3  106.86  4784.3  105.16  4834.3  107.654954.685   106.94963.748   105.6
4995.106   96.075045.315   106.8  5114.3  108.38  5234.3  107.61  5324.3  105.13
  5384.3     107  5534.3  108.18  6254.3  108.01  6304.3  105.63  6364.3  108.14
  6424.3   108.6  6644.3  107.94  6674.3  110.69  7209.1  109.81  7777.1  110.76
#Mann= 3 ,-1 , 0
  2867.5     .99       04954.685     .04       05045.315     .99       0
Bank Sta=4954.685,5045.315
XS Rating Curve= 0 ,0
Skew Angle= 25
Exp/Cntr=0.3,0.1

Type RM Length L Ch R = 1 ,33869.2 ,93,91,86
BEGIN DESCRIPTION:
Interpolated Channel - LIDAR overbanks
CROOKED WOOD - XS 4
END DESCRIPTION:
XS GIS Cut Line= 5
      3075756.35     13901356.92      3074581.72     13900352.74
      3074115.84     13900191.65      3073959.09     13900113.27
       3072339.4     13899629.98
#Sta/Elev= 30
    2866  108.15    3056  105.44    3576  106.98    4016  105.09    4136  107.19
    4236  105.02  4411.4   106.7  4561.4  104.76  4944.3  107.99 4977.24  101.53
 4981.91   98.88 4983.01   95.56 5023.47   98.73  5034.3  105.31  5054.3  107.61
  5429.6   105.4  5519.6  107.29  5569.6  105.14  5749.6  103.66  5799.6  106.42
  5959.6  106.77  6029.6  104.52  6109.6  107.87  6209.6  107.51  6299.6  104.77
  6419.6  107.59  6489.6  105.65  6549.6  109.73  6649.6  106.63  6769.8  107.33
#Mann= 3 ,-1 , 0
    2866     .99       0  4944.3     .04       0  5054.3     .99       0
Bank Sta=4944.3,5054.3
XS Rating Curve= 0 ,0
Exp/Cntr=0.5,0.3

Type RM Length L Ch R = 1 ,33778.6 ,61,60,59
BEGIN DESCRIPTION:
Upstream Section of Bridge/Culvert/Weir
CROOKED WOOD - XS 3
END DESCRIPTION:
XS GIS Cut Line= 5
      3075789.08     13901266.93      3074553.36     13900262.91
        3074074.     13900069.36      3072613.47     13899595.07
      3072349.97     13899585.99
#Sta/Elev= 30
    2890  108.59    2930  107.41    2950  104.35    2980  106.24    3490   104.7
    3550  106.96    3930  105.01    4090   107.6    4190  104.73  4974.3   105.8
  4978.8   99.23  4979.2    95.4  5018.9   96.47  5025.7  105.33  5129.1  107.45
  5199.1  104.57  5329.1  107.25  5449.1     105  5529.1  107.64  5689.1  106.53
  5749.1  103.82  5799.1  106.43  5909.1  107.18  6009.1   104.7  6199.1  107.21
  6299.1  104.79  6489.1  106.33  6574.8  109.68  6694.8  106.31  6798.4  107.72
#Mann= 3 ,-1 , 0
    2890     .99       0  4974.3     .04       0  5025.7     .99       0
#XS Ineff= 2 , 0
       0  4964.3  104.91  5035.7       0   104.1
Permanent Ineff=
       F       F
Bank Sta=4974.3,5025.7
XS Rating Curve= 0 ,0
Exp/Cntr=0.5,0.3

Type RM Length L Ch R = 2 ,33748.4 ,,,
BEGIN DESCRIPTION:
CROOKED WOOD
Structure ID: E121-00-00-22
END DESCRIPTION:
Bridge Culvert--1,0,-1,-1, 0
Deck Dist Width WeirC Skew NumUp NumDn MinLoCord MaxHiCord MaxSubmerge Is_Ogee
11,38,2.6,0, 18, 18, , , 0.95, 0, ,,,
  4904.1  4920.4  4952.7  4954.5  4974.3  4977.6  4978.8  4979.2 4979.49  4979.6
    4998    5019 5020.01  5020.6  5025.7  5050.2  5057.4  5100.9
  106.44  106.36  106.65  106.58   105.8   105.5  105.51  105.51  105.51     106
  106.07     106     106  105.42  105.37  106.03  106.24  106.75
  106.44  106.35  106.64  106.57  105.79  100.97   99.22   95.39   95.47   95.51
   95.68   96.62   98.21   99.14  105.32  106.02  106.23  106.75
  4904.1  4920.4  4952.7  4954.5  4974.3  4977.6  4978.8  4979.2 4979.49  4979.6
    4998    5019 5020.01  5020.6  5025.7  5050.2  5057.4  5100.9
  106.44  106.36  106.65  106.58   105.8   105.5  105.51  105.51  105.51     106
  106.07     106     106  105.42  105.37  106.03  106.24  106.75
  106.37  106.28  106.57   106.5  105.72   100.9   99.15   95.32    95.4   95.44
   95.61   96.55   98.14   99.07  105.25  105.95  106.16  106.68
BR Coef= 1 , 0 , 0 ,1.25, 0 ,,,0.8,0,2,0,
WSPro=,,,, 1 ,,,, 0 ,,,, 0 ,,,,-1 ,-1 ,-1 , 0 , 0 , 0 , 0 , 0
Culvert=2,10,12,38,0.015,0.5,1,8,2,94.14,4985.8,94.13,4985.8,Culvert #1  , 0 ,11.35
Culvert Bottom n=0.015
Culvert=2,10,14,37.8,0.015,0.5,1,8,2,94.12,4999.9,94.13,4999.9,Culvert #2  , 0 ,11.35
Culvert Bottom n=0.015
Culvert=2,10,12,37.8,0.015,0.5,1,8,2,94.11,5014.1,94.14,5014.1,Culvert #3  , 0 ,11.35
Culvert Bottom n=0.015
BR U #Sta/Elev= 172
  2826.3   108.5  2856.3  108.64  2866.3  108.69  2886.3  108.79  2889.4   108.8
  2896.3  108.66  2906.3  108.46  2929.4     108  2939.4   107.2  2949.4   105.4
  2959.4   104.1  2979.4   105.8  3066.3  105.59  3166.3  105.35  3186.3   105.3
  3206.3  105.26  3229.4   105.2  3246.3  105.15  3369.4   104.8  3419.4   105.3
  3439.4   105.1  3449.4   105.3  3459.4   104.7  3479.4   104.6  3559.4     107
  3589.4   106.2  3639.4   106.7  3649.4   107.2  3746.3  106.07  3766.3  105.84
  3769.4   105.8  3776.3   105.9  3789.4   106.1  3806.3  105.93  3819.4   105.8
  3839.4   106.4  3866.3  106.13  3889.4   105.9  3896.3  105.93  3909.4     106
  3939.4     105  3959.4     105  3979.4     106  4009.4   106.3  4029.4   105.3
  4046.3  105.83  4099.4   107.5  4106.3  107.47  4126.3  107.39  4136.3  107.35
  4149.4   107.3  4166.3  106.49  4199.4   104.9  4206.3  104.92  4216.3  104.94
  4246.3     105  4289.4   105.1  4309.4   106.2  4376.3  106.24  4436.3  106.28
  4459.4   106.3  4466.3  105.96  4481.6   105.2  4531.6   104.9  4548.8  105.09
  4628.8     106  4668.8  106.45  4681.6   106.6  4751.6   106.2  4788.8  106.25
  4803.5  106.27  4843.9  106.57  4849.3  106.57    4884  106.54  4904.1  106.44
  4920.4  106.35  4952.7  106.64  4954.5  106.57  4974.3  105.79  4977.6  100.97
  4978.8   99.22  4979.2   95.39 4979.49   95.47  4979.6   95.51 4979.71   95.54
  4980.1   95.65  4997.7   95.68    4998   95.68  5018.2    96.5  5018.9   96.46
    5019   96.62 5019.79   97.86  5019.9   98.04 5020.01   98.21  5020.6   99.14
  5025.7  105.32  5050.2  106.02  5057.4  106.23  5100.9  106.75  5117.9  106.38
    5133  106.06  5138.5   107.4  5147.9  107.02  5158.5   106.6  5168.5   105.5
  5188.5   104.7  5197.9  104.72  5217.9  104.76  5238.5   104.8  5267.9  106.66
  5268.5   106.7  5318.5   107.5  5388.5   106.3  5408.5   106.5  5427.9  105.92
  5428.5   105.9  5448.5     105  5457.9     105  5458.5     105  5467.9  105.45
  5508.5   107.4  5547.9  107.32  5648.5   107.1  5687.9  106.05  5708.5   105.5
  5717.9  104.97  5737.9  103.83  5738.5   103.8  5748.5   103.7  5757.9  104.14
  5787.9  105.56  5818.5     107  5827.9  107.08  5868.5   107.4  5937.9  106.45
  5978.5   105.9  6007.9  104.82  6008.5   104.8  6017.9  104.85  6028.5   104.9
  6057.9  106.96  6058.5     107  6208.5   107.2  6237.9  106.32  6257.9  105.72
  6287.9  104.82  6288.5   104.8  6307.9  105.09  6308.5   105.1  6337.9  106.57
  6338.5   106.6  6467.9     107  6468.5     107  6487.9  105.93  6488.5   105.9
  6497.9  106.46  6498.5   106.5  6518.5   108.6  6527.9  109.26  6528.5   109.3
  6534.2   109.5  6577.9  109.31  6597.9  109.23  6604.2   109.2  6637.9  107.18
  6644.2   106.8  6667.9   106.5  6684.2   106.3  6767.9  107.26  6797.8   107.6
  6827.9  107.44  6909.2     107
BR U #Mann= 3
  2826.3     .99  4974.3     .04  5025.7     .99
BR D #Sta/Elev= 172
  2826.3   108.5  2856.3  108.64  2866.3  108.69  2886.3  108.79  2889.4   108.8
  2896.3  108.66  2906.3  108.46  2929.4     108  2939.4   107.2  2949.4   105.4
  2959.4   104.1  2979.4   105.8  3066.3  105.59  3166.3  105.35  3186.3   105.3
  3206.3  105.26  3229.4   105.2  3246.3  105.15  3369.4   104.8  3419.4   105.3
  3439.4   105.1  3449.4   105.3  3459.4   104.7  3479.4   104.6  3559.4     107
  3589.4   106.2  3639.4   106.7  3649.4   107.2  3746.3  106.07  3766.3  105.84
  3769.4   105.8  3776.3   105.9  3789.4   106.1  3806.3  105.93  3819.4   105.8
  3839.4   106.4  3866.3  106.13  3889.4   105.9  3896.3  105.93  3909.4     106
  3939.4     105  3959.4     105  3979.4     106  4009.4   106.3  4029.4   105.3
  4046.3  105.83  4099.4   107.5  4106.3  107.47  4126.3  107.39  4136.3  107.35
  4149.4   107.3  4166.3  106.49  4199.4   104.9  4206.3  104.92  4216.3  104.94
  4246.3     105  4289.4   105.1  4309.4   106.2  4376.3  106.24  4436.3  106.28
  4459.4   106.3  4466.3  105.96  4481.6   105.2  4531.6   104.9  4548.8  105.09
  4628.8     106  4668.8  106.45  4681.6   106.6  4751.6   106.2  4788.8  106.25
  4803.5  106.27  4843.9  106.57  4849.3  106.57    4884  106.54  4904.1  106.44
  4920.4  106.35  4952.7  106.64  4954.5  106.57  4974.3  105.72  4977.6   100.9
  4978.8   99.15  4979.2   95.32 4979.49    95.4  4979.6   95.44 4979.71   95.47
  4980.1   95.58  4997.7   95.61    4998   95.61  5018.2   96.43  5018.9   96.39
    5019   96.55 5019.79   97.79  5019.9   97.97 5020.01   98.14  5020.6   99.07
  5025.7  105.25  5050.2  105.95  5057.4  106.23  5100.9  106.75  5117.9  106.38
    5133  106.06  5138.5   107.4  5147.9  107.02  5158.5   106.6  5168.5   105.5
  5188.5   104.7  5197.9  104.72  5217.9  104.76  5238.5   104.8  5267.9  106.66
  5268.5   106.7  5318.5   107.5  5388.5   106.3  5408.5   106.5  5427.9  105.92
  5428.5   105.9  5448.5     105  5457.9     105  5458.5     105  5467.9  105.45
  5508.5   107.4  5547.9  107.32  5648.5   107.1  5687.9  106.05  5708.5   105.5
  5717.9  104.97  5737.9  103.83  5738.5   103.8  5748.5   103.7  5757.9  104.14
  5787.9  105.56  5818.5     107  5827.9  107.08  5868.5   107.4  5937.9  106.45
  5978.5   105.9  6007.9  104.82  6008.5   104.8  6017.9  104.85  6028.5   104.9
  6057.9  106.96  6058.5     107  6208.5   107.2  6237.9  106.32  6257.9  105.72
  6287.9  104.82  6288.5   104.8  6307.9  105.09  6308.5   105.1  6337.9  106.57
  6338.5   106.6  6467.9     107  6468.5     107  6487.9  105.93  6488.5   105.9
  6497.9  106.46  6498.5   106.5  6518.5   108.6  6527.9  109.26  6528.5   109.3
  6534.2   109.5  6577.9  109.31  6597.9  109.23  6604.2   109.2  6637.9  107.18
  6644.2   106.8  6667.9   106.5  6684.2   106.3  6767.9  107.26  6797.8   107.6
  6827.9  107.44  6909.2     107
BR D #Mann= 3
  2826.3     .99  4974.3     .04  5025.7     .99
BC Design=,, 0 ,, 0 ,,,,,,
BC HTab HWMax=109.51
BC Use User HTab Curves=0
BC User HTab FreeFlow(D)= 0

Type RM Length L Ch R = 1 ,33718.1 ,99,101,107
BEGIN DESCRIPTION:
Downstream Section of Bridge/Culvert/Weir
CROOKED WOOD - XS 2
END DESCRIPTION:
XS GIS Cut Line= 5
      3075818.59     13901214.31      3074582.29     13900209.82
      3074102.07     13900015.93       3072640.7     13899541.37
       3072376.5     13899532.26
#Sta/Elev= 30
    2889  108.13    2929  104.33    3039   106.5    3399  104.64    3969  107.08
    4209  104.26    4299   106.6    4419  104.36  4631.9  106.72  4861.9  104.42
  4974.3  105.72  4978.8   99.15  4979.2   95.32  5018.9   96.39  5025.7  105.25
  5100.9  106.68  5199.8  104.15  5269.8  107.43  5469.8  104.77  5559.8  107.08
  5749.8  104.01  5939.8  106.95  6009.8  105.03  6099.8  107.28  6289.8  104.86
  6359.8  107.12  6489.8  106.08  6536.3  109.49  6646.3  106.34  6800.7  107.92
#Mann= 3 ,-1 , 0
    2889     .99       0  4974.3     .04       0  5025.7     .99       0
#XS Ineff= 2 , 0
       0 4967.63  104.91 5032.37       0   104.1
Permanent Ineff=
       F       F
Bank Sta=4974.3,5025.7
XS Rating Curve= 0 ,0
Exp/Cntr=0.5,0.3

Type RM Length L Ch R = 1 ,33616.9 ,709,708,704
BEGIN DESCRIPTION:
Interpolated Channel - LIDAR overbanks
CROOKED WOOD - XS 1
END DESCRIPTION:
XS GIS Cut Line= 5
      3075851.79      13901114.8      3074607.84     13900161.17
      3074063.59     13899882.51      3072689.79      13899454.1
      3072496.14     13899394.86
#Sta/Elev= 30
  2918.6  105.67  4018.6  107.12  4168.6   104.2  4218.6  106.52  4388.6  104.14
  4696.1  106.31  4756.1  104.22  4846.1   107.2  4946.1  107.49  4966.1   104.6
 4979.02  100.35 4981.15   98.67 4981.86    95.3  5020.9    97.2 5022.57    99.6
  5036.1   104.6  5056.1  107.12  5257.5  104.91  5357.5  107.08  5517.5   104.5
  5687.5  105.74  5737.5  103.87  5867.5  107.29  6017.5     105  6097.5  107.46
  6497.5  105.77  6527.5  108.87  6566.6  109.42  6666.6  105.98  6739.1  106.54
#Mann= 3 ,-1 , 0
  2918.6     .99       0  4946.1     .04       0  5056.1     .99       0
Bank Sta=4946.1,5056.1
XS Rating Curve= 0 ,0
Exp/Cntr=0.3,0.1