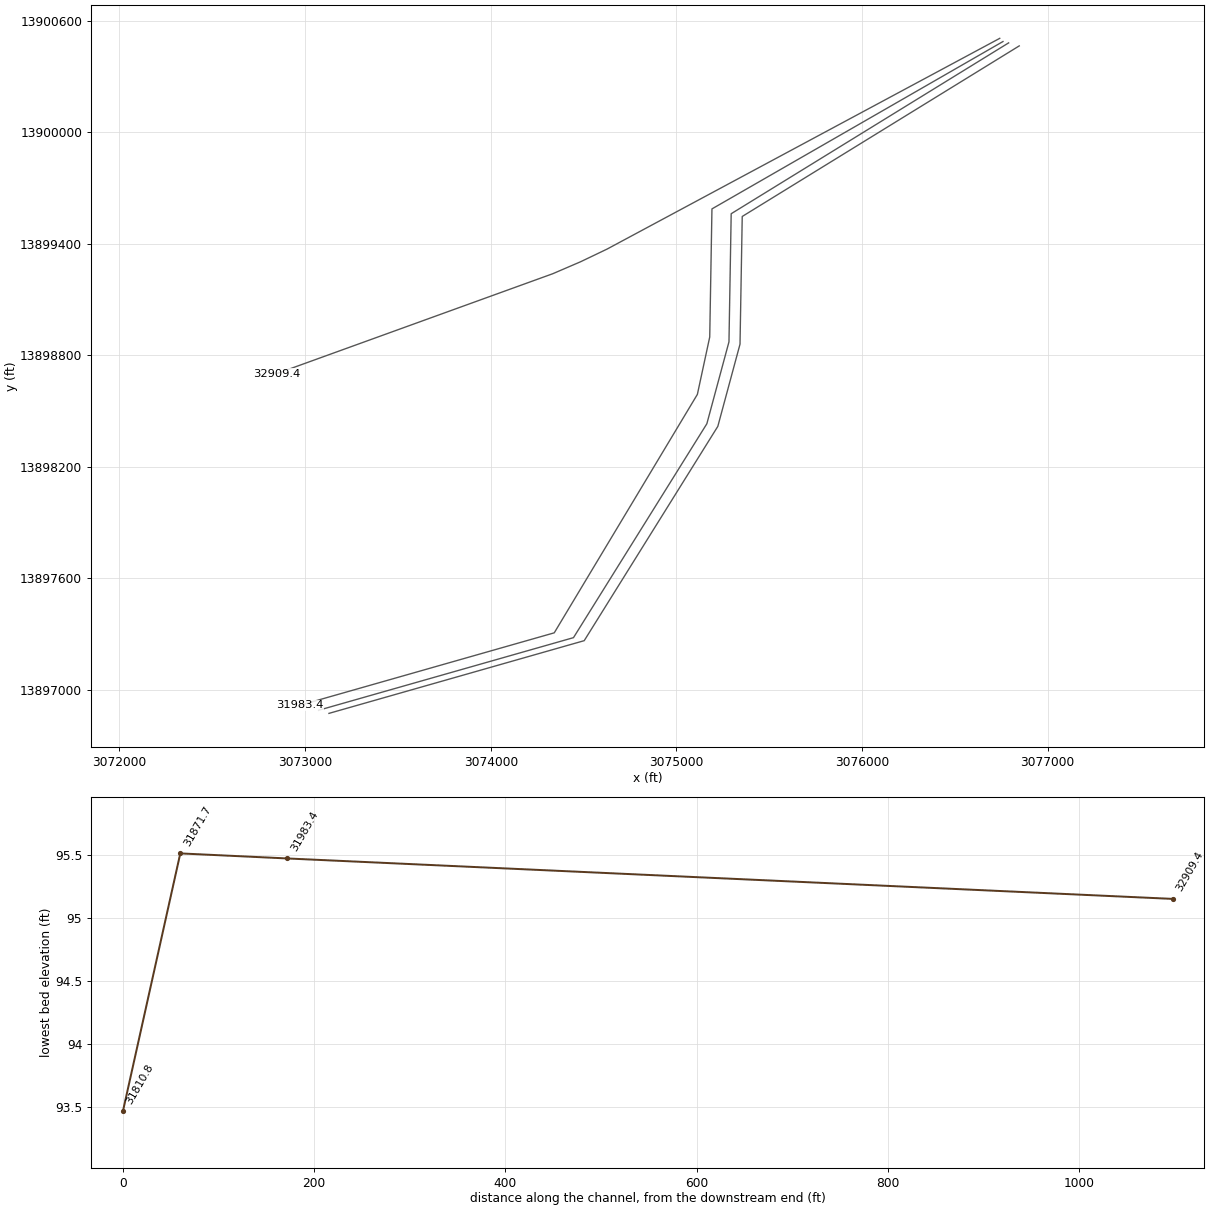
HEC-RAS study E121-00-00.prj: E121-00-00 LOMR

--- E121-00-00.g01 (geometry) --- (continued)

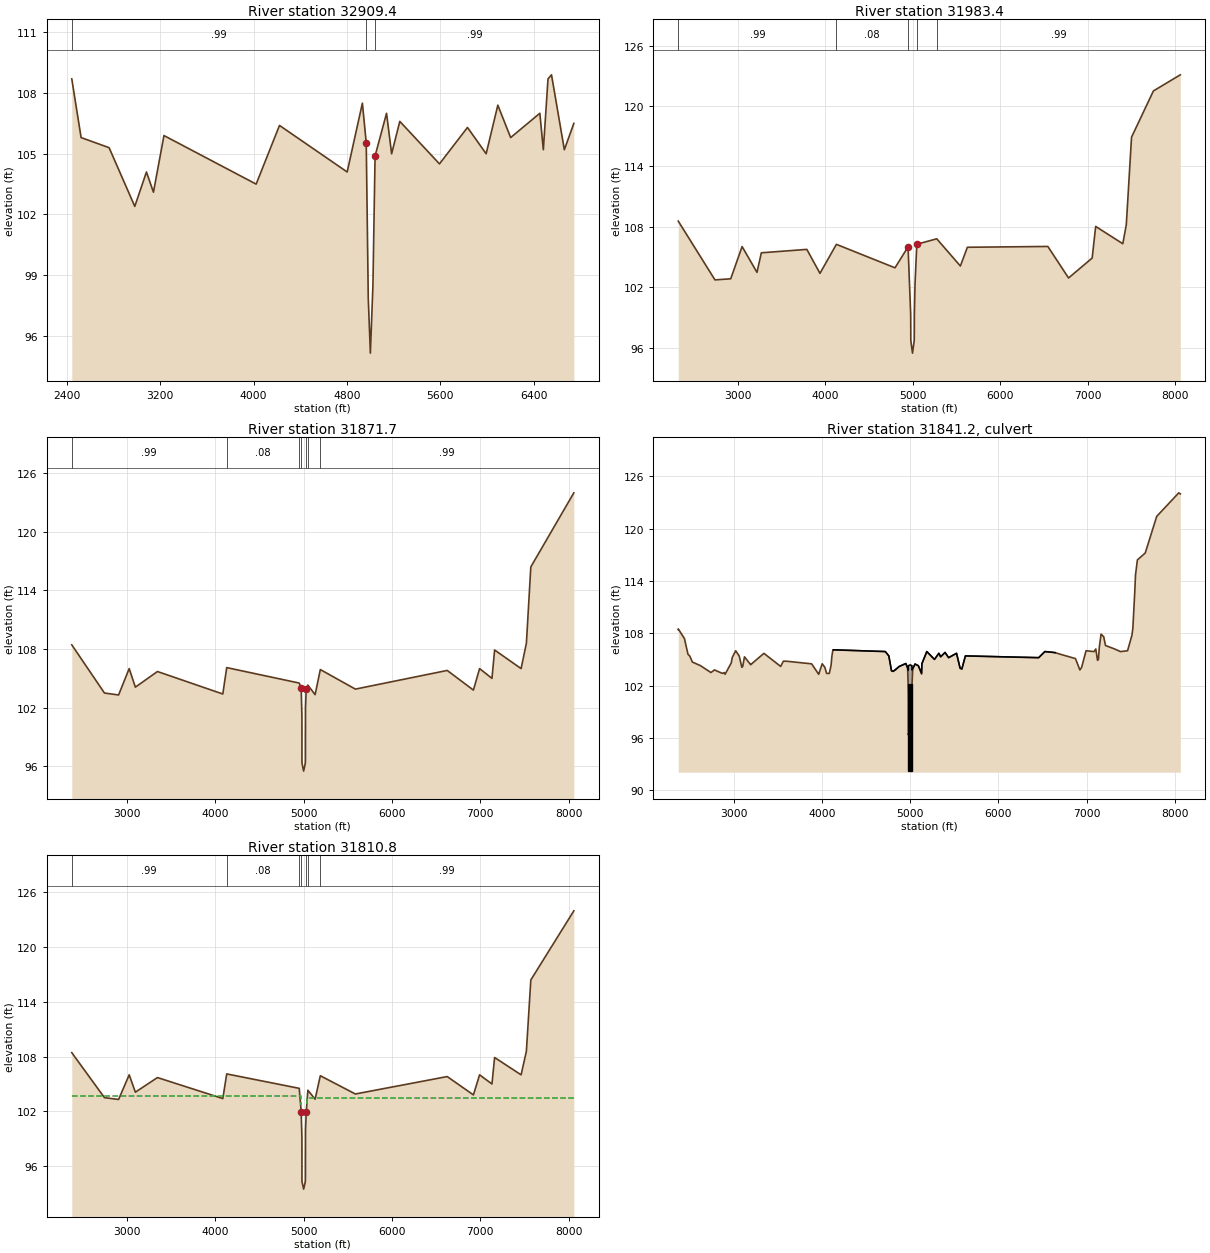
Type RM Length L Ch R = 1 ,32909.4 ,910,926,961
BEGIN DESCRIPTION:
Cross Section X23
END DESCRIPTION:
XS GIS Cut Line= 5
      3076741.57     13900504.92      3074625.96     13899370.86
      3074484.32     13899303.18      3074334.01      13899238.6
      3072846.74     13898701.12
#Sta/Elev= 30
  2441.7   108.7  2521.7   105.8  2761.7   105.3  2981.7   102.4  3081.7   104.1
  3141.7   103.1  3231.7   105.9  4021.7   103.5  4221.7   106.4  4801.7   104.1
  4932.1   107.5  4965.1  105.54  4982.5   97.86  5000.5   95.15  5022.4   98.49
  5040.8  104.89  5139.1     107  5182.7     105  5252.7   106.6  5592.7   104.5
  5832.7   106.3  5992.7     105  6092.7   107.4  6202.7   105.8  6452.7     107
  6482.7   105.2  6522.7   108.7  6552.7   108.9  6662.7   105.2  6744.1   106.5
#Mann= 3 ,-1 , 0
  2441.7     .99       0  4965.1     .04       0  5040.8     .99       0
Bank Sta=4965.1,5040.8
XS Rating Curve= 0 ,0
Exp/Cntr=0.3,0.1

Type RM Length L Ch R = 1 ,31983.4 ,113,112,109
BEGIN DESCRIPTION:
Interpolated Channel - LIDAR overbanks
WILLOW WOOD - XS 4
END DESCRIPTION:
XS GIS Cut Line= 6
      3076758.98     13900487.73      3075191.42      13899587.3
      3075179.46     13898898.17      3075112.91     13898589.36
      3074342.01     13897306.68      3072969.06     13896916.05
#Sta/Elev= 30
  2321.6  108.58  2741.6  102.74  2921.6  102.85  3051.6  106.05  3221.6  103.49
  3271.6  105.43  3791.6  105.77  3941.6  103.39  4129.4  106.27  4799.4  103.94
  4948.6  106.02  4978.6   99.33 4979.99   96.73 4999.25   95.47 5019.62   96.75
 5020.96   99.46  5028.6   102.4  5048.6  106.28  5276.5  106.82  5546.5  104.12
  5626.5  105.98  6546.5  106.06  6783.1  102.93  7053.1  104.91  7093.1  108.05
  7403.1  106.33  7443.1  108.21  7503.1  116.91  7753.1   121.5  8060.5   123.1
#Mann= 5 ,-1 , 0
  2321.6     .99       0  4129.4     .08       0  4948.6     .04       0
  5048.6     .08       0  5276.5     .99       0
Bank Sta=4948.6,5048.6
XS Rating Curve= 0 ,0
Exp/Cntr=0.5,0.3

Type RM Length L Ch R = 1 ,31871.7 ,59,60,61
BEGIN DESCRIPTION:
Upstream Section of Bridge/Culvert/Weir
WILLOW WOOD - XS 3
END DESCRIPTION:
XS GIS Cut Line= 6
      3076789.44     13900480.51      3075295.05     13899561.39
       3075283.1     13898872.26      3075163.98     13898431.49
      3074445.65     13897280.78      3073072.69     13896890.14
#Sta/Elev= 30
  2373.7  108.43  2743.9   103.5  2903.9   103.3  3023.9     106  3093.9   104.1
  3343.9   105.7  4083.9   103.4  4128.3   106.1  4949.3  104.52  4971.4  103.99
  4979.8  101.11  4980.4   96.35  4999.1   95.51  5018.7   96.34 5019.71   96.91
  5020.3  101.95  5028.7  103.92  5047.1  104.31  5129.1  103.33  5188.3   105.9
  5585.1   103.9  6625.1  105.81  6921.6   103.8  6991.6     106  7131.6     105
  7161.6   107.9  7461.6     106  7521.6   108.6  7571.6   116.4  8058.8  123.98
#Mann= 7 ,-1 , 0
  2373.7     .99       0  4128.3     .08       0  4949.3     .04       0
  4971.4     .04       0  5028.7     .04       0  5047.1     .08       0
  5188.3     .99       0
#XS Ineff= 2 , 0
       0  4961.4  103.64  5038.7       0  103.43
Permanent Ineff=
       F       F
Bank Sta=4971.4,5028.7
XS Rating Curve= 0 ,0
Exp/Cntr=0.5,0.3

Type RM Length L Ch R = 2 ,31841.2 ,,,
BEGIN DESCRIPTION:
WILLOW WOOD
Structure ID: E121-00-00-21
END DESCRIPTION:
Bridge Culvert--1,0,-1,-1, 0
Deck Dist Width WeirC Skew NumUp NumDn MinLoCord MaxHiCord MaxSubmerge Is_Ogee
12,38,2.6,0, 39, 39, , , 0.95, 0, ,,,
  4128.3  4718.3  4758.3  4788.3  4806.9  4875.9    4951  4971.4 4979.59  4979.7
  4979.8  4980.3  4980.4 4981.01  4999.1  5018.7  5019.6 5019.71  5020.1 5020.21
  5020.3  5028.7  5054.9  5092.1  5129.1  5132.9  5188.3  5275.1  5325.1  5345.1
  5395.1  5435.1  5525.1  5565.1  5585.1  5625.1  6455.1  6525.1  6642.9
  106.11  105.91  105.41  103.71  103.64   104.2  104.54     104  103.77  104.26
  104.26  104.28  104.28   104.3  104.38   104.3  104.29  104.28  104.28  103.79
  103.79  103.93  104.48  104.29  103.43  104.52  105.91  105.01  105.71  105.31
  105.81  105.21  105.71  104.01  103.91  105.41  105.21  105.91  105.78
   106.1   105.9   105.4   103.7  103.63  104.19  104.53  103.99  101.18  101.14
  101.11    96.9   96.35    96.5   95.51   96.34   96.63   96.91  100.24  101.18
  101.95  103.92  104.47  104.28  103.33  104.51   105.9     105   105.7   105.3
   105.8   105.2   105.7     104   103.9   105.4   105.2   105.9  105.77
  4128.3  4718.3  4758.3  4788.3  4806.9  4875.9    4951  4971.4 4979.59  4979.7
  4979.8  4980.3  4980.4 4981.01  4999.1  5018.7  5019.6 5019.71  5020.1 5020.21
  5020.3  5028.7  5054.9  5092.1  5129.1  5132.9  5188.3  5275.1  5325.1  5345.1
  5395.1  5435.1  5525.1  5565.1  5585.1  5625.1  6455.1  6525.1  6642.9
  106.11  105.91  105.41  103.71  103.64   104.2  104.54     104  103.77  104.26
  104.26  104.28  104.28   104.3  104.38   104.3  104.29  104.28  104.28  103.79
  103.79  103.93  104.48  104.29  103.43  104.52  105.91  105.01  105.71  105.31
  105.81  105.21  105.71  104.01  103.91  105.41  105.21  105.91  105.78
  104.06  103.86  103.36  101.66  101.59  102.15  102.49  101.95   99.14    99.1
   99.07   94.86   94.31   94.46   93.47    94.3   94.59   94.87    98.2   99.14
   99.91  101.88  102.43  102.24  101.29  102.47  103.86  102.96  103.66  103.26
  103.76  103.16  103.66  101.96  101.86  103.36  103.16  103.86  103.73
BR Coef= 1 , 0 , 0 ,1.25, 0 ,,,0.8,-1,2,0,
WSPro=,,,, 1 ,,,, 0 ,,,, 0 ,,,,-1 ,-1 ,-1 , 0 , 0 , 0 , 0 , 0
Culvert=2,10,12,38,0.015,0.5,1,8,2,92.2,4986,92.2,4986,Culvert #1  , 0 ,11.5
Culvert Bottom n=0.015
Culvert=2,10,14,37.8,0.015,0.5,1,8,2,92.2,5000,92.2,5000,Culvert #2  , 0 ,11.5
Culvert Bottom n=0.015
Culvert=2,10,12,37.8,0.015,0.5,1,8,2,92.2,5014.1,92.2,5014.1,Culvert #3  , 0 ,11.5
Culvert Bottom n=0.015
BR U #Sta/Elev= 190
  2373.7  108.43  2373.9   108.5  2425.5  107.69  2443.9   107.4  2483.9   105.6
  2495.5  105.48  2503.9   105.4  2515.5  105.13  2533.9   104.7  2575.5  104.52
  2623.9   104.3  2743.9   103.5  2783.9   103.8  2873.9   103.4  2893.9   103.5
  2903.9   103.3  2905.5  103.33  2973.9   104.6  2983.9   105.2  2985.5  105.23
  3005.5  105.63  3023.9     106  3025.5  105.98  3035.5  105.83  3063.9   105.4
  3075.5   104.9  3093.9   104.1  3103.9   104.2  3123.9   105.3  3145.5  105.02
  3175.5  104.64  3193.9   104.4  3195.5  104.41  3215.5  104.59  3265.5  105.02
  3343.9   105.7  3395.5  105.29  3425.5  105.06  3455.5  104.82  3533.9   104.2
  3563.9   104.8  3593.9   104.8  3625.5  104.77  3645.5  104.75  3825.5  104.56
  3855.5  104.53  3883.9   104.5  3895.5  104.33  3963.9   103.3  3965.5  103.35
  4003.9   104.5  4033.9   104.1  4053.9   103.4  4083.9   103.4  4095.5  103.92
  4103.9   104.3  4113.9   105.4  4123.9     106  4128.3   106.1  4155.5  106.09
  4166.1  106.09  4570.6  105.95  4718.3   105.9  4758.3   105.4  4786.9  103.78
  4788.3   103.7  4806.9  103.63  4826.9  103.76  4835.2  103.81    4862  104.06
  4875.9  104.19  4893.1  104.27  4917.9  104.39  4922.7  104.41  4949.3  104.52
    4951  104.53  4961.8  104.24  4971.4  103.99  4979.1  101.35 4979.59  101.18
  4979.7  101.14  4979.8  101.11 4979.91  100.18  4980.3    96.9  4980.4   96.35
 4981.01    96.5    4999   95.52  4999.1   95.51  5018.7   96.34  5019.6   96.63
 5019.71   96.91 5019.99    99.3  5020.1  100.24 5020.21  101.18  5020.3  101.95
  5020.6  102.02  5028.7  103.92  5032.8  104.01  5047.1  104.31  5054.9  104.47
  5067.8   104.4  5092.1  104.28  5105.6  103.93  5129.1  103.33  5132.9  104.51
  5176.9  105.61  5188.3   105.9  5224.5  105.52  5244.5  105.32  5275.1     105
  5325.1   105.7  5334.5  105.51  5345.1   105.3  5354.5  105.39  5374.5  105.59
  5394.5  105.79  5395.1   105.8  5404.5  105.66  5435.1   105.2  5525.1   105.7
  5554.5  104.45  5565.1     104  5585.1   103.9  5625.1   105.4  5725.1  105.38
  5855.1  105.34  5875.1  105.34  5885.1  105.34  5935.1  105.33  6005.1  105.31
  6145.1  105.27  6285.1  105.24  6435.1   105.2  6445.1   105.2    6455   105.2
  6455.1   105.2  6525.1   105.9  6625.1  105.81  6631.6   105.8  6642.9  105.77
  6682.9  105.65  6722.9  105.53  6871.6   105.1  6921.6   103.8  6922.9  103.82
  6941.6   104.1  6952.9  104.53  6982.9  105.67  6991.6     106  7062.9  105.92
  7081.6   105.9  7101.6   106.2  7121.6   104.9  7131.6     105  7141.6   106.4
  7152.9  107.25  7161.6   107.9  7162.9  107.89  7172.9  107.79  7191.6   107.6
  7192.9  107.54  7202.9  107.04  7211.6   106.6  7232.9  106.52  7262.9  106.41
  7291.6   106.3  7312.9  106.21  7342.9  106.07  7372.9  105.94  7381.6   105.9
  7461.6     106  7502.9  107.49  7511.6   107.8  7521.6   108.6  7532.9  110.75
  7541.6   112.4  7542.9   112.7  7551.6   114.7  7562.9  115.66  7571.6   116.4
  7572.9  116.41  7592.9  116.59  7602.9  116.68  7661.6   117.2  7752.9  120.15
  7791.6   121.4  7862.9  122.17  7952.9  123.14  8041.6   124.1  8058.8  123.98
BR U #Mann= 7
  2373.7     .99  4128.3     .08  4949.3     .04  4971.4     .04  5028.7     .04
  5047.1     .08  5188.3     .99
BR U Banks=4971.4,5028.7
BR D #Sta/Elev= 190
  2373.7  108.43  2373.9   108.5  2425.5  107.69  2443.9   107.4  2483.9   105.6
  2495.5  105.48  2503.9   105.4  2515.5  105.13  2533.9   104.7  2575.5  104.52
  2623.9   104.3  2743.9   103.5  2783.9   103.8  2873.9   103.4  2893.9   103.5
  2903.9   103.3  2905.5  103.33  2973.9   104.6  2983.9   105.2  2985.5  105.23
  3005.5  105.63  3023.9     106  3025.5  105.98  3035.5  105.83  3063.9   105.4
  3075.5   104.9  3093.9   104.1  3103.9   104.2  3123.9   105.3  3145.5  105.02
  3175.5  104.64  3193.9   104.4  3195.5  104.41  3215.5  104.59  3265.5  105.02
  3343.9   105.7  3395.5  105.29  3425.5  105.06  3455.5  104.82  3533.9   104.2
  3563.9   104.8  3593.9   104.8  3625.5  104.77  3645.5  104.75  3825.5  104.56
  3855.5  104.53  3883.9   104.5  3895.5  104.33  3963.9   103.3  3965.5  103.35
  4003.9   104.5  4033.9   104.1  4053.9   103.4  4083.9   103.4  4095.5  103.92
  4103.9   104.3  4113.9   105.4  4123.9     106  4128.3   106.1  4155.5  106.09
  4166.1  106.09  4570.6  105.95  4718.3   105.9  4758.3   105.4  4786.9  103.78
  4788.3   103.7  4806.9  103.63  4826.9  103.76  4835.2  103.81    4862  104.06
  4875.9  104.19  4893.1  104.27  4917.9  104.39  4922.7  104.41  4949.3  104.52
    4951  104.53  4961.8  104.24  4971.4  101.95  4979.1   99.31 4979.59   99.14
  4979.7    99.1  4979.8   99.07 4979.91   98.14  4980.3   94.86  4980.4   94.31
 4981.01   94.46    4999   93.48  4999.1   93.47  5018.7    94.3  5019.6   94.59
 5019.71   94.87 5019.99   97.26  5020.1    98.2 5020.21   99.14  5020.3   99.91
  5020.6   99.98  5028.7  101.88  5032.8  104.01  5047.1  104.31  5054.9  104.47
  5067.8   104.4  5092.1  104.28  5105.6  103.93  5129.1  103.33  5132.9  104.51
  5176.9  105.61  5188.3   105.9  5224.5  105.52  5244.5  105.32  5275.1     105
  5325.1   105.7  5334.5  105.51  5345.1   105.3  5354.5  105.39  5374.5  105.59
  5394.5  105.79  5395.1   105.8  5404.5  105.66  5435.1   105.2  5525.1   105.7
  5554.5  104.45  5565.1     104  5585.1   103.9  5625.1   105.4  5725.1  105.38
  5855.1  105.34  5875.1  105.34  5885.1  105.34  5935.1  105.33  6005.1  105.31
  6145.1  105.27  6285.1  105.24  6435.1   105.2  6445.1   105.2    6455   105.2
  6455.1   105.2  6525.1   105.9  6625.1  105.81  6631.6   105.8  6642.9  105.77
  6682.9  105.65  6722.9  105.53  6871.6   105.1  6921.6   103.8  6922.9  103.82
  6941.6   104.1  6952.9  104.53  6982.9  105.67  6991.6     106  7062.9  105.92
  7081.6   105.9  7101.6   106.2  7121.6   104.9  7131.6     105  7141.6   106.4
  7152.9  107.25  7161.6   107.9  7162.9  107.89  7172.9  107.79  7191.6   107.6
  7192.9  107.54  7202.9  107.04  7211.6   106.6  7232.9  106.52  7262.9  106.41
  7291.6   106.3  7312.9  106.21  7342.9  106.07  7372.9  105.94  7381.6   105.9
  7461.6     106  7502.9  107.49  7511.6   107.8  7521.6   108.6  7532.9  110.75
  7541.6   112.4  7542.9   112.7  7551.6   114.7  7562.9  115.66  7571.6   116.4
  7572.9  116.41  7592.9  116.59  7602.9  116.68  7661.6   117.2  7752.9  120.15
  7791.6   121.4  7862.9  122.17  7952.9  123.14  8041.6   124.1  8058.8  123.98
BR D #Mann= 8
  2373.7     .99  2373.9     .99  4128.3     .08  4949.3     .04  4971.4     .04
  5028.7     .04  5047.1     .08  5188.3     .99
BR D Banks=4971.4,5028.7
BC Design=,, 0 ,, 0 ,,,,,,
BC HTab HWMax=124.1
BC Use User HTab Curves=0
BC User HTab FreeFlow(D)= 0

Type RM Length L Ch R = 1 ,31810.8 ,103,104,109
BEGIN DESCRIPTION:
Downstream Section of Bridge/Culvert/Weir
WILLOW WOOD - XS 2
END DESCRIPTION:
XS GIS Cut Line= 6
      3076846.58     13900464.29      3075354.53     13899546.61
      3075342.61      13898859.8      3075223.06      13898417.4
      3074503.39     13897264.54      3073128.58     13896873.38
#Sta/Elev= 30
  2373.7  108.43  2743.9   103.5  2903.9   103.3  3023.9     106  3093.9   104.1
  3343.9   105.7  4083.9   103.4  4128.3   106.1  4949.3  104.52  4971.4  101.95
  4979.8   99.07  4980.4   94.31  4999.1   93.47  5018.7    94.3 5019.71   94.87
  5020.3   99.91  5028.7  101.88  5047.1  104.31  5129.1  103.33  5188.3   105.9
  5585.1   103.9  6625.1  105.81  6921.6   103.8  6991.6     106  7131.6     105
  7161.6   107.9  7461.6     106  7521.6   108.6  7571.6   116.4  8058.8  123.98
#Mann= 7 ,-1 , 0
  2373.7     .99       0  4128.3     .08       0  4949.3     .04       0
  4971.4     .04       0  5028.7     .04       0  5047.1     .08       0
  5188.3     .99       0
#XS Ineff= 2 , 0
       0 4964.73  103.64 5035.37       0  103.43
Permanent Ineff=
       F       F
Bank Sta=4971.4,5028.7
XS Rating Curve= 0 ,0
Exp/Cntr=0.5,0.3