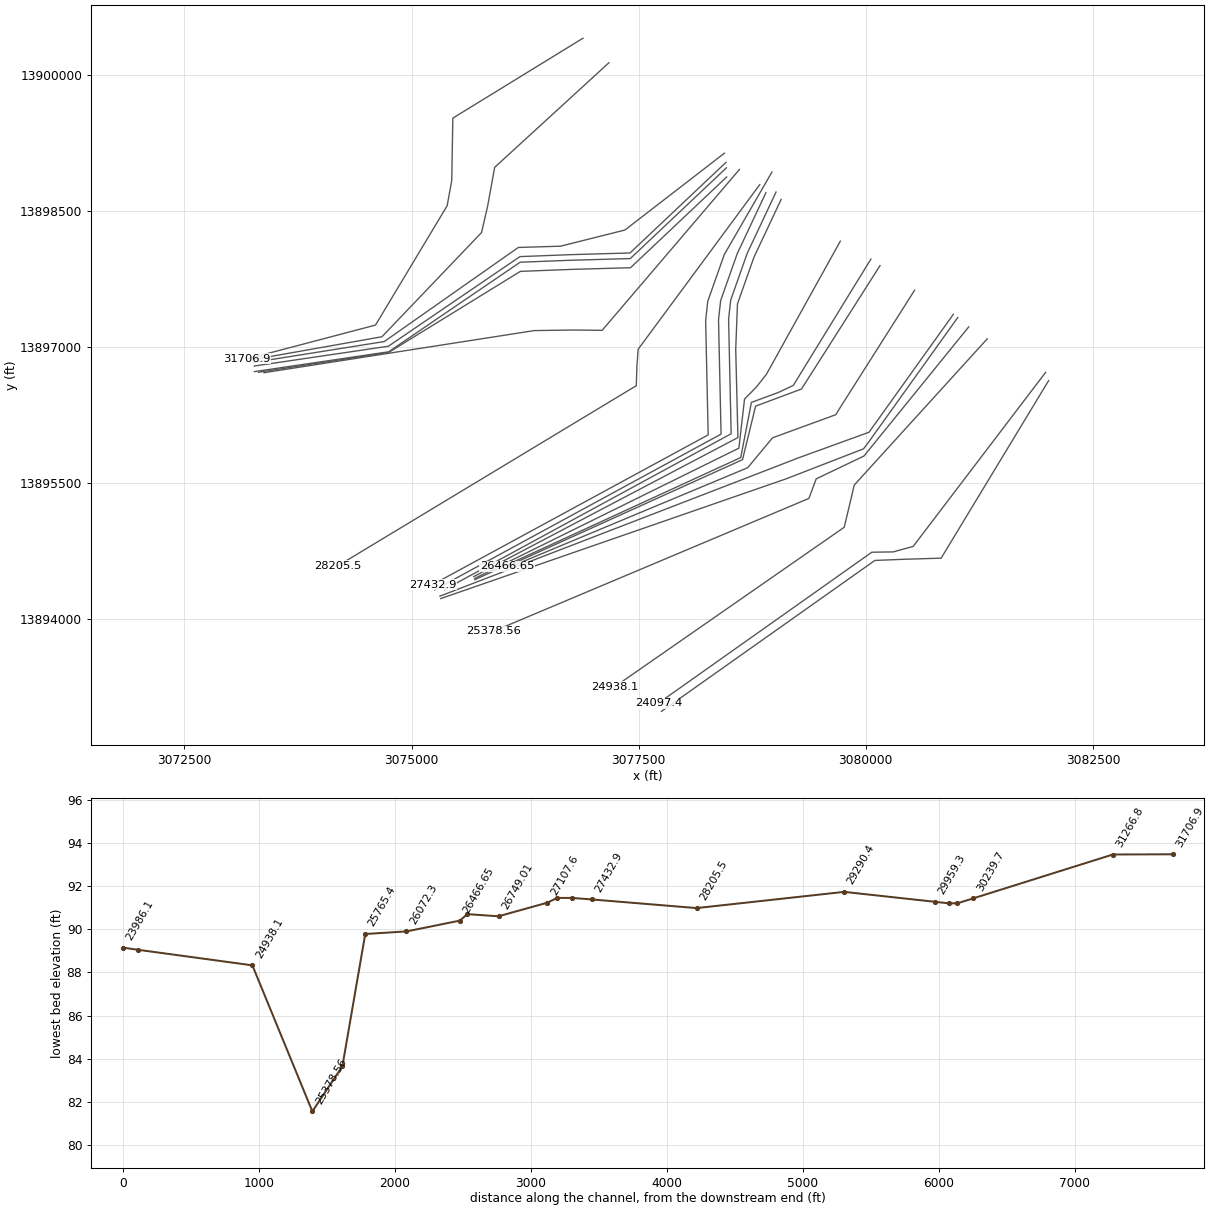
HEC-RAS study E121-00-00.prj: E121-00-00 LOMR

--- E121-00-00.g01 (geometry) --- (continued)

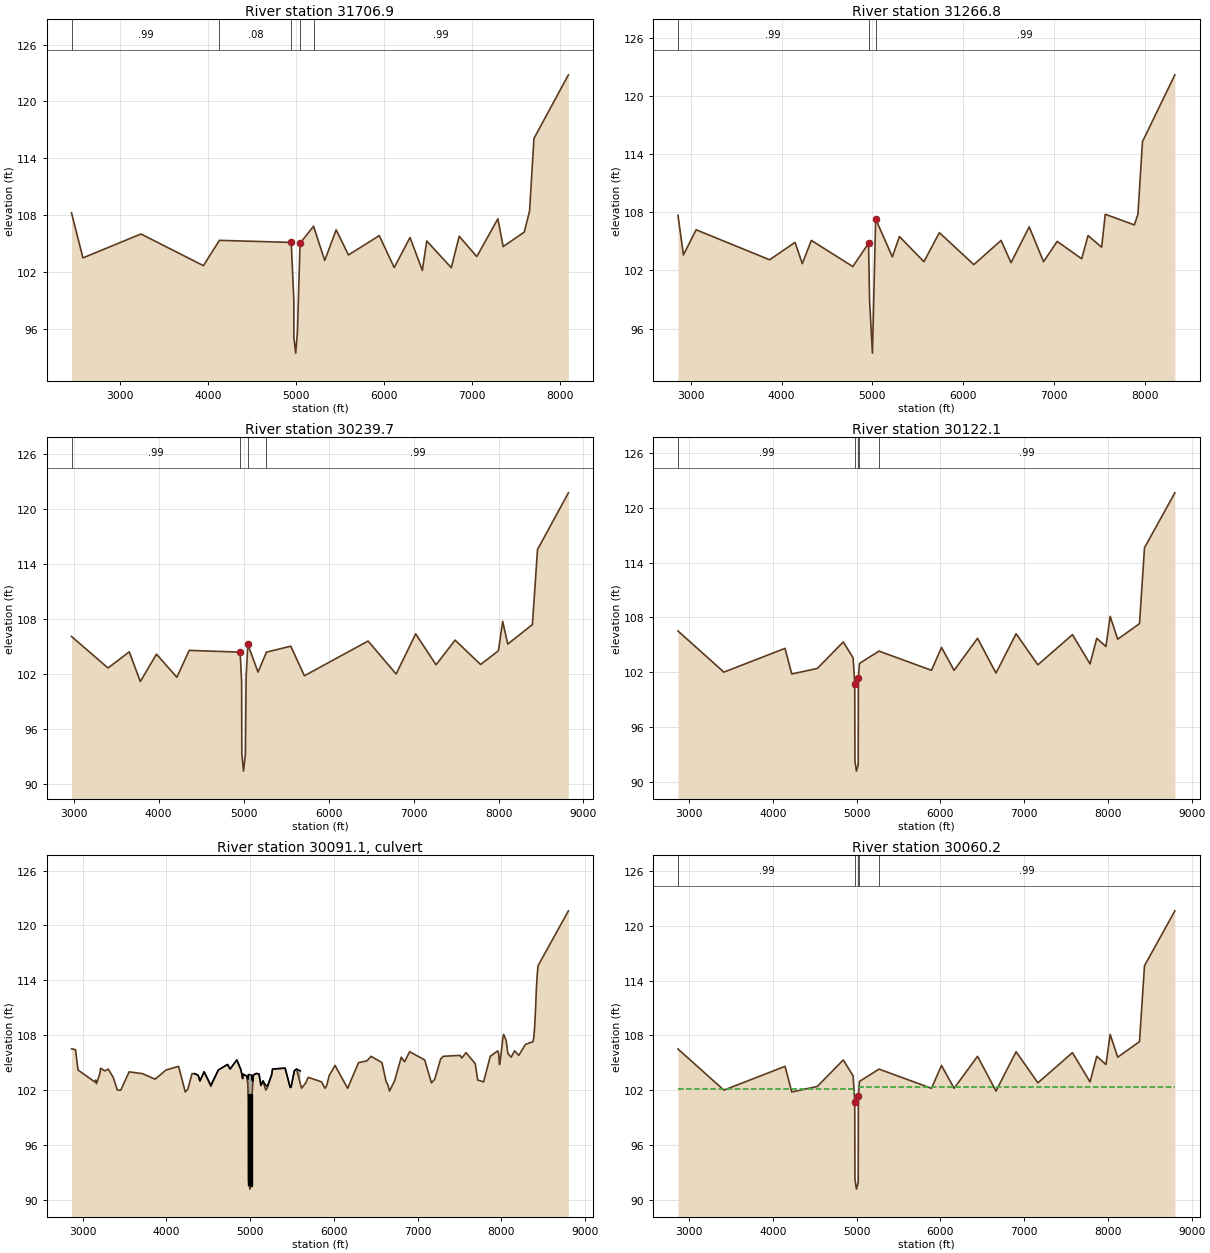
Type RM Length L Ch R = 1 ,31706.9 ,442,441,438
BEGIN DESCRIPTION:
Interpolated Channel - LIDAR overbanks
WILLOW WOOD - XS 1
END DESCRIPTION:
XS GIS Cut Line= 6
      3076886.49      13900401.7      3075454.07      13899520.7
      3075442.15     13898833.89      3075391.57     13898554.53
      3074602.93     13897238.63      3073189.35     13896865.89
#Sta/Elev= 30
  2450.1  108.26  2580.1  103.51  3240.1  106.03  3950.1  102.69  4131.8  105.36
  4948.7  105.14  4978.7   99.02 4978.71   95.56 4978.82   95.11 4999.48   93.47
 5019.81   95.77  5048.7  105.05  5202.6  106.85  5329.6  103.24  5459.6  106.47
  5599.6  103.82  5949.6  105.86  6119.6  102.49  6299.6  105.66  6439.6  102.19
  6489.6  105.29  6768.7  102.48  6858.7  105.79  7058.7  103.65  7298.7  107.63
  7358.7   104.7  7598.7  106.23  7658.7  108.44  7708.7   116.1  8100.6  122.81
#Mann= 5 ,-1 , 0
  2450.1     .99       0  4131.8     .08       0  4948.7     .04       0
  5048.7     .08       0  5202.6     .99       0
Bank Sta=4948.7,5048.7
XS Rating Curve= 0 ,0
Exp/Cntr=0.3,0.1

Type RM Length L Ch R = 1 ,31266.8 ,1051,1027,998
BEGIN DESCRIPTION:
Cross Section X22
END DESCRIPTION:
XS GIS Cut Line= 6
      3077172.42     13900131.53      3075914.52     13898977.87
      3075836.93      13898549.4      3075770.09     13898258.94
      3074673.52     13897109.87      3073248.86     13896857.11
#Sta/Elev= 30
  2858.2   107.7  2918.2   103.6  3058.2   106.2  3868.2   103.1  4148.2   104.9
  4228.2   102.7  4328.2   105.1    4785   102.4  4958.2   104.8  4969.9   98.83
  5001.1   93.46  5036.5  107.31  5220.5   103.4  5298.5   105.5  5568.5   102.9
  5738.5   105.9  6118.5   102.6  6418.5   105.1  6528.5   102.8  6728.5   106.5
  6886.8   102.9  7036.8     105  7306.8   103.2  7376.8   105.6  7526.8   104.4
  7566.8   107.8  7886.8   106.7  7926.8   107.8  7976.8   115.3  8333.8   122.2
#Mann= 3 ,-1 , 0
  2858.2     .99       0  4958.2     .04       0  5036.5     .99       0
Bank Sta=4958.2,5036.5
XS Rating Curve= 0 ,0
Exp/Cntr=0.3,0.1

Type RM Length L Ch R = 1 ,30239.7 ,122,117,113
BEGIN DESCRIPTION:
Interpolated Channel - LIDAR overbanks
SILENT WOOD - XS 4
END DESCRIPTION:
XS GIS Cut Line= 6
      3078443.95     13899134.28      3077348.16     13898286.74
      3076640.52     13898108.72      3076174.84     13898094.51
        3074699.     13897056.87       3073253.6     13896826.34
#Sta/Elev= 30
    2974  106.13    3404  102.69    3654  104.45    3784  101.21    3974   104.2
    4214  101.68  4359.3  104.61  4959.3  104.42 4976.42  101.16 4978.77   93.36
 4998.59   91.43 5021.05    93.3  5029.3  101.68  5049.3  105.28    5169  102.24
    5269  104.42  5554.9  105.07  5714.9  101.84  6464.9  105.63  6794.9  102.03
  7024.9  106.41  7264.9  103.04    7489  105.73    7789  103.07    7999  104.57
    8049  107.78    8109   105.3    8399  107.43    8459  115.62  8822.7  121.81
#Mann= 4 ,-1 , 0
    2974     .99       0  4959.3     .04       0  5049.3     .08       0
    5269     .99       0
Bank Sta=4959.3,5049.3
XS Rating Curve= 0 ,0
Exp/Cntr=0.5,0.3

Type RM Length L Ch R = 1 ,30122.1 ,63,62,61
BEGIN DESCRIPTION:
Upstream Section of Bridge/Culvert/Weir
SILENT WOOD - XS 3
END DESCRIPTION:
XS GIS Cut Line= 6
      3078461.68     13899033.37      3077404.67     13898033.82
      3076748.13     13898015.12      3076192.56      13897993.6
      3074744.93     13897005.53      3073268.57     13896787.24
#Sta/Elev= 30
  2868.6  106.52  3416.5  102.02  4146.5  104.62  4226.5  101.82  4531.3  102.42
  4841.3  105.32  4959.1  103.58  4978.5  100.75  4980.6   92.32  4998.3    91.2
 5019.71   91.89  5022.2  101.33  5034.1  102.97  5268.1  104.32  5894.1  102.22
  6014.1  104.72  6164.1  102.22  6444.1  105.72  6664.1  101.92  6904.1  106.22
  7164.1  102.82  7576.8  106.12  7786.8  102.92  7866.8  105.72  7976.8  104.82
  8026.8  108.12  8116.8  105.62  8376.8  107.32  8436.8  115.62  8799.2  121.62
#Mann= 5 ,-1 , 0
  2868.6     .99       0  4978.5     .04       0  5022.2     .04       0
  5034.1     .08       0  5268.1     .99       0
#XS Ineff= 2 , 0
       0  4968.5   102.1  5032.2       0  102.31
Permanent Ineff=
       F       F
Bank Sta=4978.5,5022.2
XS Rating Curve= 0 ,0
Exp/Cntr=0.5,0.3

Type RM Length L Ch R = 2 ,30091.1 ,,,
BEGIN DESCRIPTION:
SILENT WOOD
Structure ID: E121-00-00-20
END DESCRIPTION:
Bridge Culvert--1,0,-1,-1, 0
Deck Dist Width WeirC Skew NumUp NumDn MinLoCord MaxHiCord MaxSubmerge Is_Ogee
12,38,2.6,0, 54, 54, , , 0.95, 0, ,,,
  4333.3  4341.3  4381.3  4401.3  4451.3  4531.3  4621.3  4731.3  4761.3  4841.3
  4891.3  4910.4  4916.6  4935.9  4945.2  4959.1  4972.2  4978.5  4978.9 4978.99
  4979.1 4979.21  4979.5  4980.2  4980.6  4982.4  4998.3  5018.6 5019.71 5020.09
  5020.2 5020.31  5021.2  5021.3  5022.2  5034.1  5039.1  5057.4  5073.7  5088.8
  5106.3  5129.6  5153.4  5188.1  5208.1  5258.1  5268.1  5418.1  5478.1  5488.1
  5500.5  5528.1  5554.1  5600.5
  103.81  103.81  103.61  103.01  104.01  102.57  104.21  104.81  104.31  105.31
  104.21  103.28  103.76  103.63  103.61  103.57  103.24  103.21  103.21  103.21
  103.71  103.71  103.71  103.71  103.71  103.71  103.68  103.64  103.64  103.64
  103.64  103.14  103.14  103.14  103.12  102.96  103.65  103.75  103.83   103.8
  103.76  102.54  103.01   102.5  102.49  103.71  104.31  104.41  102.31  102.31
  102.87  104.11  104.31   104.1
   103.8   103.8   103.6     103     104   102.4   104.2   104.8   104.3   105.3
   104.2  103.26  103.75  103.62   103.6  103.56  102.69  100.73   98.96   98.56
   98.07   97.58    96.3   94.16    92.3   91.93   91.18   91.81   91.87    92.9
    93.2    93.5   95.91   96.18  101.31  102.95  103.64  103.74  103.82  103.79
  103.75  102.49     103     102   102.3   103.7   104.3   104.4   102.3   102.3
  102.86   104.1   104.3  102.68
  4333.3  4341.3  4381.3  4401.3  4451.3  4531.3  4621.3  4731.3  4761.3  4841.3
  4891.3  4910.4  4916.6  4935.9  4945.2  4959.1  4972.2  4978.5  4978.9 4978.99
  4979.1 4979.21  4979.5  4980.2  4980.6  4982.4  4998.3  5018.6 5019.71 5020.09
  5020.2 5020.31  5021.2  5021.3  5022.2  5034.1  5039.1  5057.4  5073.7  5088.8
  5106.3  5129.6  5153.4  5188.1  5208.1  5258.1  5268.1  5418.1  5478.1  5488.1
  5500.5  5528.1  5554.1  5600.5
  103.81  103.81  103.61  103.01  104.01  102.57  104.21  104.81  104.31  105.31
  104.21  103.28  103.76  103.63  103.61  103.57  103.24  103.21  103.21  103.21
  103.71  103.71  103.71  103.71  103.71  103.71  103.68  103.64  103.64  103.64
  103.64  103.14  103.14  103.14  103.12  102.96  103.65  103.75  103.83   103.8
  103.76  102.54  103.01   102.5  102.49  103.71  104.31  104.41  102.31  102.31
  102.87  104.11  104.31   104.1
   103.8   103.8   103.6     103     104   102.4   104.2   104.8   104.3   105.3
   104.2  103.26  103.75  103.62   103.6  103.56  102.69  100.73   98.96   98.56
   98.07   97.58    96.3   94.16    92.3   91.93   91.18   91.81   91.87    92.9
    93.2    93.5   95.91   96.18  101.31  102.95  103.64  103.74  103.82  103.79
  103.75  102.49     103     102   102.3   103.7   104.3   104.4   102.3   102.3
  102.86   104.1   104.3  102.68
BR Coef= 1 , 0 , 0 ,1.25, 0 ,,,0.8,-1,2,0,
WSPro=,,,, 1 ,,,, 0 ,,,, 0 ,,,,-1 ,-1 ,-1 , 0 , 0 , 0 , 0 , 0
Culvert=2,10,11.5,38,0.015,0.5,1,8,2,91.6,4985.7,91.65,4985.7,Culvert #1  , 0 ,12
Culvert Bottom n=0.015
Culvert=2,10,13,37.8,0.015,0.5,1,8,2,91.56,5000,91.62,5000,Culvert #2  , 0 ,12
Culvert Bottom n=0.015
Culvert=2,10,11.5,37.8,0.015,0.5,1,8,2,91.54,5014.1,91.61,5014.1,Culvert #3  , 0 ,12
Culvert Bottom n=0.015
BR U #Sta/Elev= 192
  2868.6   106.5  2886.5   106.5  2888.6  106.49  2908.6  106.43  2916.5   106.4
  2946.5   104.2  3138.6  102.95  3146.5   102.9  3156.5   103.1  3166.5   102.7
  3206.5   103.8  3216.5   104.4  3266.5   104.1  3268.6  104.11  3306.5   104.3
  3308.6  104.27  3338.6  103.82  3358.6  103.52  3366.5   103.4  3416.5     102
  3418.6     102  3438.6     102  3456.5     102  3488.6  102.64  3556.5     104
  3628.6  103.91  3658.6  103.87  3716.5   103.8  3758.6  103.63  3798.6  103.47
  3828.6  103.35  3866.5   103.2  3898.6  103.45  3958.6  103.91  3996.5   104.2
  4118.6  104.53  4146.5   104.6  4196.2  102.86  4226.2  101.81  4226.5   101.8
  4256.5   102.1  4296.2  103.45  4306.5   103.8  4333.3   103.8  4341.3   103.8
  4381.3   103.6  4401.3     103  4451.3     104  4531.3   102.4  4621.3   104.2
  4731.3   104.8  4761.3   104.3  4841.3   105.3  4891.3   104.2  4910.4  103.26
  4916.6  103.75  4935.9  103.62  4945.2   103.6  4959.1  103.56  4972.2  102.69
  4978.5  100.73  4978.9   98.96 4978.99   98.56  4979.1   98.07 4979.21   97.58
  4979.5    96.3  4980.2   94.16  4980.6    92.3  4982.4   91.93  4998.3   91.18
  5018.6   91.81 5019.71   91.87 5020.09    92.9  5020.2    93.2 5020.31    93.5
  5021.2   95.91  5021.3   96.18  5022.2  101.31  5034.1  102.95  5039.1  103.64
  5057.4  103.74  5073.7  103.82  5088.8  103.79  5106.3  103.75  5129.6  102.49
  5153.4     103  5188.1     102  5208.1   102.3  5258.1   103.7  5268.1   104.3
  5418.1   104.4  5478.1   102.3  5488.1   102.3  5500.5  102.86  5528.1   104.1
  5554.1   104.3  5600.5  102.68  5614.1   102.2  5664.1   102.8  5680.5  103.13
  5694.1   103.4  5854.1   102.9  5860.5  102.79  5894.1   102.2  5914.1   102.5
  5940.5  103.47  5944.1   103.6  6014.1   104.7  6020.5  104.59  6060.5  103.93
  6164.1   102.2  6170.5  102.34  6270.5  104.49  6280.5  104.71  6294.1     105
  6380.5  105.17  6394.1   105.2  6444.1   105.7  6490.5  105.45  6540.5  105.18
  6570.5  105.02  6574.1     105  6624.1   102.9  6644.1   102.6  6664.1   101.9
  6720.5  102.93  6724.1     103  6804.1   105.6  6844.1   105.1  6880.5  105.77
  6904.1   106.2  6980.5  105.82  7010.5  105.67  7040.5  105.52  7084.1   105.3
  7110.5  104.48  7164.1   102.8  7204.1   103.2    7253  104.74  7274.1   105.4
  7306.8   105.7    7403  105.75    7433  105.76  7506.8   105.8    7523  105.56
  7526.8   105.5    7573  106.05  7576.8   106.1    7653  105.27  7686.8   104.9
    7693  104.53    7713  103.33  7716.8   103.1    7743  103.03    7773  102.94
  7786.8   102.9    7813  103.82  7866.8   105.7    7953  106.27  7956.8   106.3
    7963  106.11  7966.8     106  7976.8   104.8    7983  105.11  7986.8   105.3
    8003   106.6  8016.8   107.7  8026.8   108.1    8033  107.96  8056.8   107.4
    8063  106.97  8076.8     106    8113  105.64  8116.8   105.6    8133  105.88
  8156.8   106.3  8206.8   105.8  8286.8     107    8353  107.22    8373  107.29
  8376.8   107.3  8386.8   107.8  8396.8     109    8403  110.12  8406.8   110.8
  8416.8   113.1    8423  114.03  8426.8   114.6  8436.8   115.6    8633  118.85
    8743  120.67  8799.2   121.6
BR U #Mann= 5
  2868.6     .99  4978.5     .04  5022.2     .04  5034.1     .08  5268.1     .99
BR U Banks=4978.5,5022.2
BR D #Sta/Elev= 192
  2868.6   106.5  2886.5   106.5  2888.6  106.49  2908.6  106.43  2916.5   106.4
  2946.5   104.2  3138.6  102.95  3146.5   102.9  3156.5   103.1  3166.5   102.7
  3206.5   103.8  3216.5   104.4  3266.5   104.1  3268.6  104.11  3306.5   104.3
  3308.6  104.27  3338.6  103.82  3358.6  103.52  3366.5   103.4  3416.5     102
  3418.6     102  3438.6     102  3456.5     102  3488.6  102.64  3556.5     104
  3628.6  103.91  3658.6  103.87  3716.5   103.8  3758.6  103.63  3798.6  103.47
  3828.6  103.35  3866.5   103.2  3898.6  103.45  3958.6  103.91  3996.5   104.2
  4118.6  104.53  4146.5   104.6  4196.2  102.86  4226.2  101.81  4226.5   101.8
  4256.5   102.1  4296.2  103.45  4306.5   103.8  4333.3   103.8  4341.3   103.8
  4381.3   103.6  4401.3     103  4451.3     104  4531.3   102.4  4621.3   104.2
  4731.3   104.8  4761.3   104.3  4841.3   105.3  4891.3   104.2  4910.4  103.26
  4916.6  103.75  4935.9  103.62  4945.2   103.6  4959.1  103.56  4972.2  102.69
  4978.5  100.73  4978.9   98.96 4978.99   98.56  4979.1   98.07 4979.21   97.58
  4979.5    96.3  4980.2   94.16  4980.6    92.3  4982.4   91.93  4998.3   91.18
  5018.6   91.81 5019.71   91.87 5020.09    92.9  5020.2    93.2 5020.31    93.5
  5021.2   95.91  5021.3   96.18  5022.2  101.31  5034.1  102.95  5039.1  103.64
  5057.4  103.74  5073.7  103.82  5088.8  103.79  5106.3  103.75  5129.6  102.49
  5153.4     103  5188.1     102  5208.1   102.3  5258.1   103.7  5268.1   104.3
  5418.1   104.4  5478.1   102.3  5488.1   102.3  5500.5  102.86  5528.1   104.1
  5554.1   104.3  5600.5  102.68  5614.1   102.2  5664.1   102.8  5680.5  103.13
  5694.1   103.4  5854.1   102.9  5860.5  102.79  5894.1   102.2  5914.1   102.5
  5940.5  103.47  5944.1   103.6  6014.1   104.7  6020.5  104.59  6060.5  103.93
  6164.1   102.2  6170.5  102.34  6270.5  104.49  6280.5  104.71  6294.1     105
  6380.5  105.17  6394.1   105.2  6444.1   105.7  6490.5  105.45  6540.5  105.18
  6570.5  105.02  6574.1     105  6624.1   102.9  6644.1   102.6  6664.1   101.9
  6720.5  102.93  6724.1     103  6804.1   105.6  6844.1   105.1  6880.5  105.77
  6904.1   106.2  6980.5  105.82  7010.5  105.67  7040.5  105.52  7084.1   105.3
  7110.5  104.48  7164.1   102.8  7204.1   103.2    7253  104.74  7274.1   105.4
  7306.8   105.7    7403  105.75    7433  105.76  7506.8   105.8    7523  105.56
  7526.8   105.5    7573  106.05  7576.8   106.1    7653  105.27  7686.8   104.9
    7693  104.53    7713  103.33  7716.8   103.1    7743  103.03    7773  102.94
  7786.8   102.9    7813  103.82  7866.8   105.7    7953  106.27  7956.8   106.3
    7963  106.11  7966.8     106  7976.8   104.8    7983  105.11  7986.8   105.3
    8003   106.6  8016.8   107.7  8026.8   108.1    8033  107.96  8056.8   107.4
    8063  106.97  8076.8     106    8113  105.64  8116.8   105.6    8133  105.88
  8156.8   106.3  8206.8   105.8  8286.8     107    8353  107.22    8373  107.29
  8376.8   107.3  8386.8   107.8  8396.8     109    8403  110.12  8406.8   110.8
  8416.8   113.1    8423  114.03  8426.8   114.6  8436.8   115.6    8633  118.85
    8743  120.67  8799.2   121.6
BR D #Mann= 5
  2868.6     .99  4978.5     .04  5022.2     .04  5034.1     .08  5268.1     .99
BR D Banks=4978.5,5022.2
BC Design=,, 0 ,, 0 ,,,,,,
BC HTab HWMax=121.62
BC Use User HTab Curves=0
BC User HTab FreeFlow(D)= 0

Type RM Length L Ch R = 1 ,30060.2 ,100,101,102
BEGIN DESCRIPTION:
Downstream Section of Bridge/Culvert/Weir
SILENT WOOD - XS 2
END DESCRIPTION:
XS GIS Cut Line= 6
      3078465.93      13898972.9      3077407.54     13897972.03
      3076749.12     13897953.28      3076195.02     13897931.82
      3074747.62     13896943.91      3073270.12     13896725.45
#Sta/Elev= 30
  2868.6  106.52  3416.5  102.02  4146.5  104.62  4226.5  101.82  4531.3  102.42
  4841.3  105.32  4959.1  103.58  4978.5  100.75  4980.6   92.32  4998.3    91.2
 5019.71   91.89  5022.2  101.33  5034.1  102.97  5268.1  104.32  5894.1  102.22
  6014.1  104.72  6164.1  102.22  6444.1  105.72  6664.1  101.92  6904.1  106.22
  7164.1  102.82  7576.8  106.12  7786.8  102.92  7866.8  105.72  7976.8  104.82
  8026.8  108.12  8116.8  105.62  8376.8  107.32  8436.8  115.62  8799.2  121.62
#Mann= 5 ,-1 , 0
  2868.6     .99       0  4978.5     .04       0  5022.2     .04       0
  5034.1     .08       0  5268.1     .99       0
#XS Ineff= 2 , 0
       0 4971.83   102.1 5028.87       0  102.31
Permanent Ineff=
       F       F
Bank Sta=4978.5,5022.2
XS Rating Curve= 0 ,0
Exp/Cntr=0.5,0.3

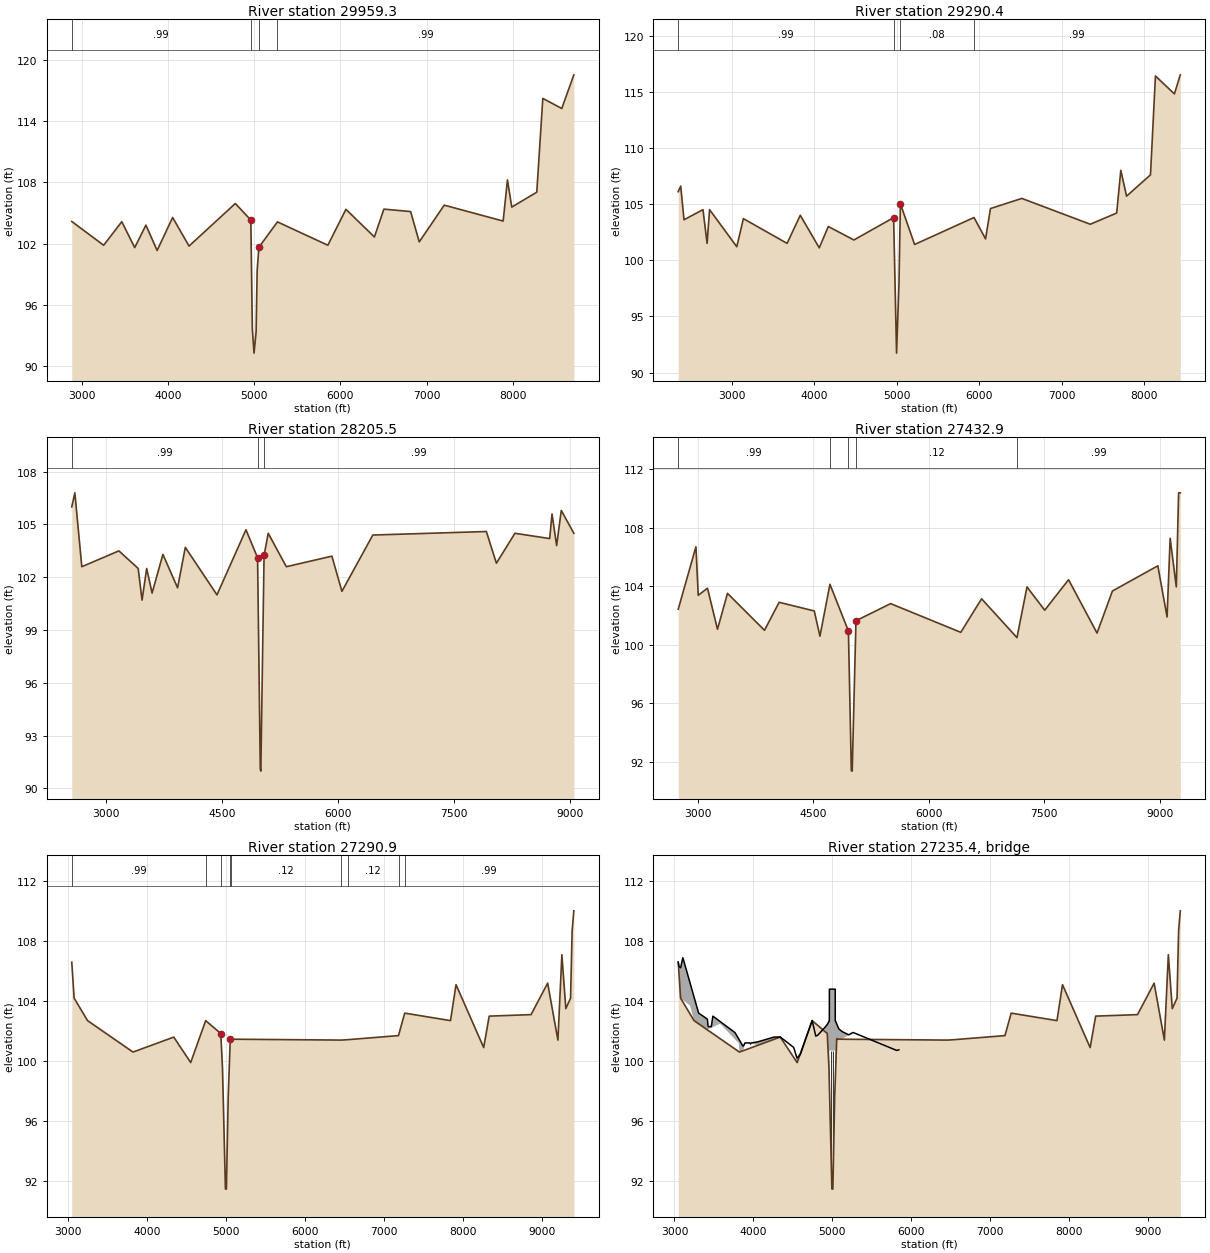
Type RM Length L Ch R = 1 ,29959.3 ,671,669,668
BEGIN DESCRIPTION:
Interpolated Channel - LIDAR overbanks
SILENT WOOD - XS 1
END DESCRIPTION:
XS GIS Cut Line= 6
      3078468.66     13898871.99      3077410.27     13897871.12
      3076751.85     13897852.38      3076197.75     13897830.91
      3074748.04     13896937.17      3073314.65      13896718.4
#Sta/Elev= 30
  2884.6  104.17  3254.6  101.84  3464.6  104.15  3614.6  101.61  3744.6  103.81
  3874.6  101.33  4054.6  104.56  4244.6  101.76  4781.3  105.93  4961.3  104.31
 4978.92   93.64 4998.46   91.27 5022.52   93.35  5034.6   99.34  5054.6  101.64
    5270  104.13  5854.5  101.84  6064.5  105.36  6394.5  102.65  6504.5  105.38
  6814.5  105.14  6914.5  102.17  7204.5  105.77  7887.6  104.21  7937.6  108.24
  7987.6  105.58  8277.6  107.04  8347.6  116.23  8567.6  115.24  8707.5  118.54
#Mann= 4 ,-1 , 0
  2884.6     .99       0  4961.3     .04       0  5054.6     .08       0
    5270     .99       0
Bank Sta=4961.3,5054.6
XS Rating Curve= 0 ,0
Exp/Cntr=0.3,0.1

Type RM Length L Ch R = 1 ,29290.4 ,1015,1085,1144
BEGIN DESCRIPTION:
Cross Section X21
END DESCRIPTION:
XS GIS Cut Line= 5
      3078608.56     13898953.88      3077097.82     13897180.64
      3076781.25     13897184.22      3076350.87     13897177.91
      3073375.24      13896713.5
#Sta/Elev= 30
  2352.2   106.1  2382.2   106.6  2422.2   103.6  2652.2   104.5  2702.2   101.5
  2732.2   104.5  3062.2   101.2  3142.2   103.7  3672.2   101.5  3832.2     104
  4062.2   101.1  4172.2     103  4482.2   101.8    4964  103.79  4999.5   91.73
  5029.2   97.96    5046  105.03  5218.3   101.4  5938.7   103.8  6078.8   101.9
  6138.8   104.6  6518.8   105.5  7348.8   103.2  7668.8   104.2  7718.8     108
  7788.8   105.7  8078.8   107.6  8138.8   116.4  8368.8   114.8  8440.4   116.5
#Mann= 4 ,-1 , 0
  2352.2     .99       0    4964     .04       0    5046     .08       0
  5938.7     .99       0
Bank Sta=4964,5046
XS Rating Curve= 0 ,0
Exp/Cntr=0.3,0.1

Type RM Length L Ch R = 1 ,28205.5 ,772,772,930
BEGIN DESCRIPTION:
Cross Section X20
END DESCRIPTION:
XS GIS Cut Line= 5
       3078832.6     13898787.29      3077494.11       13896972.
      3077480.59     13896784.29      3077473.74     13896570.17
      3074185.23     13894582.25
#Sta/Elev= 30
  2554.8     106  2594.8   106.8  2684.8   102.6  3164.8   103.5  3414.8   102.5
  3464.8   100.7  3524.8   102.5  3594.8   101.1  3734.8   103.3  3924.8   101.4
  4024.8   103.7  4434.8     101  4810.2   104.7  4960.5  103.11  4995.5    91.1
  5002.6   90.98  5044.6  103.24  5098.4   104.5  5332.6   102.6  5922.6   103.2
  6052.6   101.2  6452.6   104.4  7922.6   104.6  8052.6   102.8  8292.6   104.5
  8742.6   104.2  8772.6   105.6  8832.6   103.8  8892.6   105.8  9055.3   104.5
#Mann= 3 ,-1 , 0
  2554.8     .99       0  4960.5     .04       0  5044.6     .99       0
Bank Sta=4960.5,5044.6
XS Rating Curve= 0 ,0
Exp/Cntr=0.3,0.1

Type RM Length L Ch R = 1 ,27432.9 ,142,142,204
BEGIN DESCRIPTION:
Interpolated Channel - LIDAR overbanks
CHAMPION FOREST - XS 4
END DESCRIPTION:
XS GIS Cut Line= 6
      3078966.81     13898925.78       3078441.9     13898015.33
      3078260.24     13897500.19      3078237.15     13897287.51
      3078265.14     13896027.86      3075233.03     13894377.72
#Sta/Elev= 30
  2745.3  102.43  2975.3  106.69  3005.3  103.38  3125.3  103.86  3255.3  101.06
  3385.3  103.51  3866.2  100.99  4056.2   102.9  4512.5  102.31  4586.4  100.59
  4716.4  104.13  4956.4  100.94 4994.13   91.41 5005.56   91.38  5054.6  101.64
  5504.6  102.81  6416.4  100.85  6686.4  103.14  7146.4  100.49  7276.4  103.95
  7506.4  102.36  7816.4  104.44  8186.4   100.8  8386.4  103.67  8976.4  105.39
  9096.4   101.9  9136.4  107.27  9216.4  103.95  9246.4  110.37  9268.4  110.37
#Mann= 5 ,-1 , 0
  2745.3     .99       0  4716.4     .05       0  4956.4     .04       0
  5054.6     .12       0  7146.4     .99       0
Bank Sta=4956.4,5054.6
XS Rating Curve= 0 ,0
Exp/Cntr=0.5,0.3

Type RM Length L Ch R = 1 ,27290.9 ,112,112,112
BEGIN DESCRIPTION:
CHAMPION FOREST - XS 3
END DESCRIPTION:
XS GIS Cut Line= 6
      3078900.47      13898698.3      3078583.72     13898023.51
      3078402.05     13897508.37      3078378.97     13897295.69
      3078406.95     13896036.04      3075252.82     13894318.51
#Sta/Elev= 30
  3048.3   106.6  3078.3   104.2  3248.3   102.7  3823.7   100.6  4339.9   101.6
  4553.9    99.9  4743.9   102.7    4935  101.84  4956.7   99.54  4993.9   91.46
  5006.1   91.45  5029.1   97.59  5055.5   101.5  5065.1  101.46  6463.1   101.4
  6548.3  101.43  7185.3   101.7  7263.8   103.2  7843.8   102.7  7913.8   105.1
  8263.8   100.9  8333.8     103  8863.8   103.1  9073.8   105.2  9203.8   101.4
  9253.8   107.1  9303.8   103.5  9363.8   104.2  9383.8   108.7  9405.4  110.03
#Mann= 9 ,-1 , 0
  3048.3     .99       0  4743.9     .05       0    4935     .04       0
  5055.5     .04       0  5065.1     .12       0  6463.1     .05       0
  6548.3     .12       0  7185.3      .1       0  7263.8     .99       0
#XS Ineff= 2 , 0
       0    4925   100.2  5065.5       0  100.71
Permanent Ineff=
       F       F
Bank Sta=4935,5055.5
XS Rating Curve= 0 ,0
Exp/Cntr=0.5,0.3

Type RM Length L Ch R = 3 ,27235.4 ,,,
BEGIN DESCRIPTION:
CHAMPION FOREST; Rectangular piers
Structure ID: E121-00-00-19
END DESCRIPTION:
Bridge Culvert--1,0,-1,-1, 0
Deck Dist Width WeirC Skew NumUp NumDn MinLoCord MaxHiCord MaxSubmerge Is_Ogee
12,88,2.6,0, 50, 50, , , 0.95, 0, ,,,
  3048.3  3058.3  3078.3  3106.9  3198.3  3248.3  3306.9  3416.9  3426.9  3466.9
  3486.9  3578.3  3766.9  3813.7  3823.7  3867.3  3873.7  3893.7  3953.7  3963.7
  3973.7  4053.7  4261.5  4339.9  4509.9    4552  4593.9  4743.9  4789.4  4811.8
    4856  4899.4    4935  4956.7 4961.41  4961.5 4961.69  4961.9  5036.4 5036.51
 5037.49  5037.6  5055.5  5081.3  5100.1  5122.5  5207.5  5262.1  5813.8  5841.7
  106.61  106.31  106.23   106.9  105.21  104.28   103.2   102.8   102.3   102.3
     103  102.64   101.9  101.48  101.39     101  101.01  101.21  101.21  101.15
  101.21  101.28   101.6  101.61  100.91   100.2  100.44  102.71  101.67  101.71
  101.96  102.21  102.44  102.65   102.7   102.7   102.7   104.8   104.8   102.7
  102.69  102.69  102.47  102.15  102.07  101.97  101.75  101.91  100.71  100.75
   106.6   106.3   104.2  104.08   103.7   102.7  102.49   102.1  102.12  102.22
  102.27   102.5  101.45   101.2   100.6   100.6   100.6   101.2   101.2     101
   101.2   100.7  101.35   101.6   100.9    99.9     100   102.7  101.66  101.33
  101.46  102.12  101.84   99.54   98.65   100.7   100.7   100.7   100.7   100.7
  100.69   98.87   101.5   101.4  101.32  101.38  101.74   101.9   100.7  100.74
  3048.3  3058.3  3078.3  3106.9  3198.3  3248.3  3306.9  3416.9  3426.9  3466.9
  3486.9  3578.3  3766.9  3813.7  3823.7  3867.3  3873.7  3893.7  3953.7  3963.7
  3973.7  4053.7  4261.5  4339.9  4509.9    4552  4593.9  4743.9  4789.4  4811.8
    4856  4899.4    4935  4956.7 4961.41  4961.5 4961.69  4961.9  5036.4 5036.51
 5037.49  5037.6  5055.5  5081.3  5100.1  5122.5  5207.5  5262.1  5813.8  5841.7
  106.61  106.31  106.23   106.9  105.21  104.28   103.2   102.8   102.3   102.3
     103  102.64   101.9  101.48  101.39     101  101.01  101.21  101.21  101.15
  101.21  101.28   101.6  101.61  100.91   100.2  100.44  102.71  101.67  101.71
  101.96  102.21  102.44  102.65   102.7   102.7   102.7   104.8   104.8   102.7
  102.69  102.69  102.47  102.15  102.07  101.97  101.75  101.91  100.71  100.75
   106.6   106.3   104.2  104.08   103.7   102.7  102.49   102.1  102.12  102.22
  102.27   102.5  101.45   101.2   100.6   100.6   100.6   101.2   101.2     101
   101.2   100.7  101.35   101.6   100.9    99.9     100   102.7  101.66  101.33
  101.46  102.12  101.84   99.54   98.65   100.7   100.7   100.7   100.7   100.7
  100.69   98.87   101.5   101.4  101.32  101.38  101.74   101.9   100.7  100.74
Pier Skew, UpSta & Num, DnSta & Num=  ,4987, 2 ,4987, 2 , 0 , 0 , 0 ,,
     1.2     1.2
   92.68   101.7
     1.2     1.2
    92.9  101.92
Pier Skew, UpSta & Num, DnSta & Num=  ,5012, 2 ,5012, 2 , 0 , 0 , 0 ,,
     1.2     1.2
   92.79   101.7
     1.2     1.2
   93.01  101.92
BR Coef= 1 , 1 , 0 ,1.25, 0 ,,,0.8,0,2,0,
WSPro=,,,, 1 ,,,, 0 ,,,, 0 ,,,,-1 ,-1 ,-1 , 0 , 0 , 0 , 0 , 0
BC Design=,, 0 ,, 0 ,,,,,,
BC HTab HWMax=110.6
BC Use User HTab Curves=0
BC User HTab FreeFlow(D)= 0

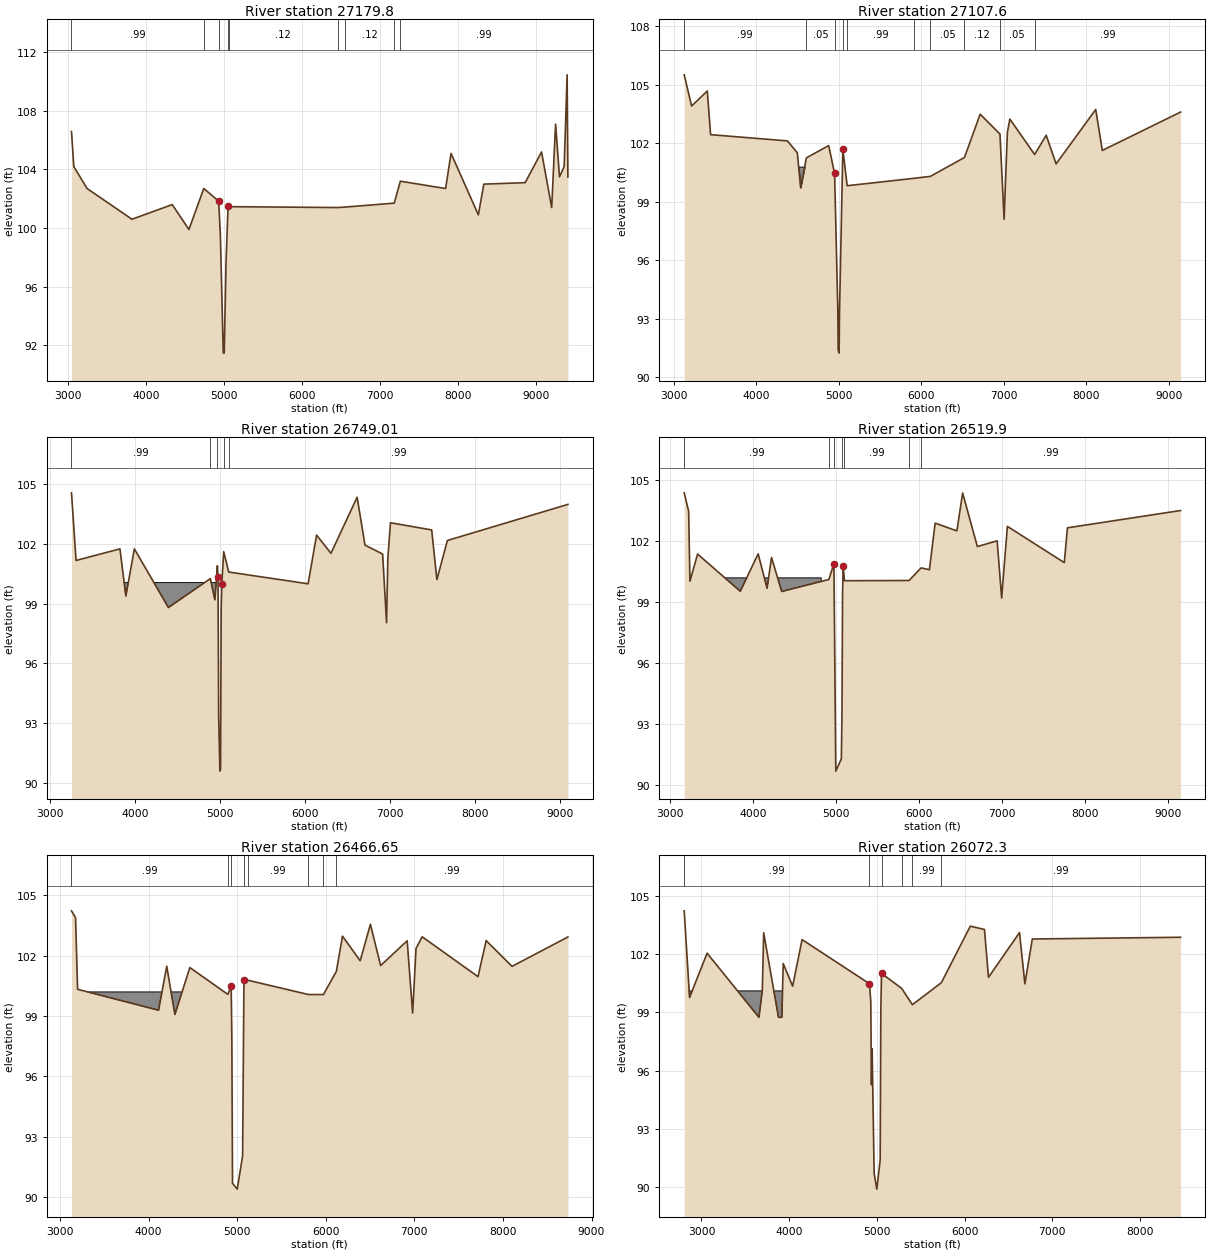
Type RM Length L Ch R = 1 ,27179.8 ,71,72,115
BEGIN DESCRIPTION:
CHAMPION FOREST - XS 2
END DESCRIPTION:
XS GIS Cut Line= 6
      3079011.85      13898705.3      3078694.22     13898028.67
      3078512.83     13897514.32      3078489.84     13897302.55
      3078517.88     13896040.15      3075361.08     13894321.17
#Sta/Elev= 30
  3048.3   106.6  3078.3   104.2  3248.3   102.7  3823.7   100.6  4339.9   101.6
  4553.9    99.9  4743.9   102.7    4935  101.84  4956.7   99.54  4993.9   91.46
  5006.1   91.45  5029.1   97.59  5055.5   101.5  5065.1  101.46  6463.1   101.4
  6548.3  101.43  7185.3   101.7  7263.8   103.2  7843.8   102.7  7913.8   105.1
  8263.8   100.9  8333.8     103  8863.8   103.1  9073.8   105.2  9203.8   101.4
  9253.8   107.1  9303.8   103.5  9363.8   104.2  9401.7  110.47  9411.4  103.48
#Mann= 9 ,-1 , 0
  3048.3     .99       0  4743.9     .05       0    4935     .04       0
  5055.5     .04       0  5065.1     .12       0  6463.1     .05       0
  6548.3     .12       0  7185.3      .1       0  7263.8     .99       0
#XS Ineff= 2 , 0
       0 4928.33   100.2 5062.17       0  100.71
Permanent Ineff=
       F       F
Bank Sta=4935,5055.5
XS Rating Curve= 0 ,0
Exp/Cntr=0.5,0.3

Type RM Length L Ch R = 1 ,27107.6 ,585,359,310
BEGIN DESCRIPTION:
Interpolated Channel - LIDAR overbanks
CHAMPION FOREST - XS 1
EHRA Revised Cross-Section per NW Park Colony AsBuilt for LOMR dated March 2009
END DESCRIPTION:
XS GIS Cut Line= 6
      3079068.41      13898624.8      3078768.79     13897986.52
       3078587.4     13897472.17       3078568.3     13896971.05
      3078592.45       13895998.      3075683.59     13894464.91
#Sta/Elev= 30
  3128.3  105.51  3218.3  103.91  3408.3  104.68  3448.3  102.44  4378.8  102.12
  4498.8  101.51  4538.8   99.72  4608.8  101.25  4878.8  101.88  4950.3  100.45
 4989.29   93.48 4994.02   91.38 5005.36   91.23    5009   93.13  5050.3   101.7
 5102.74   99.82  5913.1   100.2  6110.7   100.3  6523.8  101.27  6713.8  103.49
  6953.8  102.47  7003.8    98.1  7043.8  102.57  7073.8  103.24  7373.8  101.42
  7513.8  102.41  7633.8  100.94  8113.8  103.73  8193.8  101.63  9141.9   103.6
#Mann= 10 ,-1 , 0
  3128.3     .99       0  4608.8     .05       0  4950.3     .04       0
  5050.3      .1       0 5102.74     .99       0  5913.1      .1       0
  6110.7     .05       0  6523.8     .12       0  6953.8     .05       0
  7373.8     .99       0
#Block Obstruct= 2 , 0
       0  4880.3   100.8  5050.3       0   100.8
Bank Sta=4950.3,5050.3
XS Rating Curve= 0 ,0
Exp/Cntr=0.3,0.1

Type RM Length L Ch R = 1 ,26749.01,270,229,169
BEGIN DESCRIPTION:
EHRA Added Cross-Section per NW Park Colony AsBuilt for LOMR dated March 2009
Area outside of NW Park Colony and Vogel Creek based on 2001 LiDAR
END DESCRIPTION:
XS GIS Cut Line= 6
  3079719.80692913898164.3930717 3078906.714157213896696.7362164
 3078796.874961313896556.8466743 3078665.447872913896422.8290389
 3078602.814201413895881.2319971 3075696.182004413894445.5699971
#Sta/Elev= 30
 3255.46  104.55 3309.34  101.16  3825.1  101.74 3894.38   99.38 3994.45  101.74
 4394.74    98.8  4887.4  100.25 4940.71   99.19 4970.35  100.89 4977.77  100.33
 4985.18   93.33    5000    90.6 5007.41    90.7 5014.82   98.83 5022.23     100
 5044.46   101.6 5103.75  100.58 6036.19   99.99  6136.1  102.43 6305.16  101.52
 6612.55  104.33 6704.77  101.93 6912.26  101.48 6958.37   98.04 6973.74   101.3
 7004.48  103.05 7488.62  102.69  7550.1   100.2 7673.05  102.16 9089.47  103.97
#Mann= 5 ,-1 , 0
 3255.46     .99       0  4887.4     .12       0 4970.35     .04       0
 5044.46     .12       0 5103.75     .99       0
#Block Obstruct= 2 , 0
       0 4962.94  100.05 5051.87       0  100.05
Bank Sta=4977.77,5022.23
XS Rating Curve= 0 ,0
Exp/Cntr=0.3,0.1

Type RM Length L Ch R = 1 ,26519.9 ,62,55,52
BEGIN DESCRIPTION:
EHRA Revised Cross-Section per NW Park Colony AsBuilt for LOMR dated March 2009
END DESCRIPTION:
XS GIS Cut Line= 6
 3080056.249958713897965.9999765 3079201.749861513896573.0000391
 3079036.249957413896495.0001671  3078740.749925 13896385.999975
 3078623.749988813895777.9999743 3075695.913678513894430.6941505
#Sta/Elev= 30
 3175.43  104.38  3229.2  103.47 3244.56  100.04 3336.74  101.37 3850.73   99.54
 4065.43  101.38 4172.78   99.69 4226.46   101.2  4349.2   99.53 4916.36  100.12
 4977.35  100.89    5000    90.7 5066.67    91.3 5074.08   93.39 5081.48   99.46
 5088.89  100.78 5103.71  100.06 5881.45  100.07  6026.7  100.69  6126.7   100.6
 6195.93  102.89 6457.46  102.51 6526.69  104.37 6703.61  101.74 6942.07  102.02
 6995.91   99.21 7065.14  102.73 7749.72  100.95 7788.18  102.66 9149.65  103.51
#Mann= 7 ,-1 , 0
 3175.43     .99       0 4916.36     .12       0 4977.35     .04       0
 5074.08     .12       0 5103.71     .99       0 5881.45     .99       0
  6026.7     .99       0
#Block Obstruct= 2 , 0
       0 4824.88   100.2 5177.78       0   100.2
Bank Sta=4977.35,5088.89
XS Rating Curve= 0 ,0
Exp/Cntr=0.3,0.1

Type RM Length L Ch R = 1 ,26466.65,401,393,403
BEGIN DESCRIPTION:
EHRA Added Cross-Section per NW Park Colony AsBuilt for LOMR dated March 2009
Area outside of NW Park Colony and Vogel Creek based on 2001 LiDAR
END DESCRIPTION:
XS GIS Cut Line= 5
 3080157.216147413897895.0158094 3079292.254016413896533.4078538
 3078787.122768713896344.7368654 3078643.021414913895754.4173881
 3076052.574468313894578.8455555
#Sta/Elev= 30
 3128.67  104.23 3174.76  103.89  3197.8  100.33  4111.9   99.29 4204.08  101.48
 4296.26   99.08 4465.25  101.41 4893.68  100.08 4931.65  100.49 4939.25   97.89
 4946.84   90.69    5000    90.4 5060.76   92.05 5075.95   100.8 5121.52  100.78
 5804.05  100.07 5973.24  100.07 6119.32  101.22 6188.51  102.97 6388.41  101.75
 6503.74  103.56 6619.07  101.51 6918.92  102.74 6980.43   99.15 7018.87  102.36
 7088.06  102.94 7718.52  100.96 7810.78  102.75 8102.94  101.47  8733.4  102.93
#Mann= 8 ,-1 , 0
 3128.67     .99       0 4893.68     .07       0 4931.65     .04       0
 5075.95     .07       0 5121.52     .99       0 5804.05     .99       0
 5973.24     .12       0 6119.32     .99       0
#Block Obstruct= 2 , 0
       0 4657.29   100.2 5511.76       0   100.2
Bank Sta=4931.65,5075.95
XS Rating Curve= 0 ,0
Exp/Cntr=0.3,0.1

Type RM Length L Ch R = 1 ,26072.3 ,303,303,307
BEGIN DESCRIPTION:
EHRA Added Cross-Section per NW Park Colony AsBuilt for LOMR dated March 2009
Area outside of NW Park Colony and Vogel Creek based on 2001 LiDAR
END DESCRIPTION:
XS GIS Cut Line= 6
 3080537.302191313897622.9413224 3079699.1240466 13896298.916554
 3079670.8448061 13896250.702767   3078973.9759413895995.8419069
 3078700.165670913895665.7049538 3076055.318012813894559.6407437
#Sta/Elev= 30
 2803.35  104.22  2864.8   99.76 3064.52  102.04    3656   98.74 3694.41  100.14
 3709.77  103.09 3878.76   98.74 3917.17   98.74 3932.53  101.51 4040.07  100.34
 4147.62  102.74 4915.85  100.47 4931.15   99.55  4938.8   95.27 4946.45   97.13
  4969.4   90.71    5000    89.9 5038.25    91.4  5045.9   99.16 5053.55     101
 5283.18  100.23 5405.73   99.39 5735.55  100.52 6066.04  103.43 6227.44  103.26
 6273.56   100.8  6627.1   103.1 6688.59  100.46 6773.13  102.77 8464.06  102.86
#Mann= 6 ,-1 , 0
 2803.35     .99       0 4915.85     .04       0 5053.55     .99       0
 5283.18     .07       0 5405.73     .99       0 5735.55     .99       0
#Block Obstruct= 2 , 0
       0 4594.57   100.1 5275.52       0   100.1
Bank Sta=4915.85,5053.55
XS Rating Curve= 0 ,0
Exp/Cntr=0.3,0.1

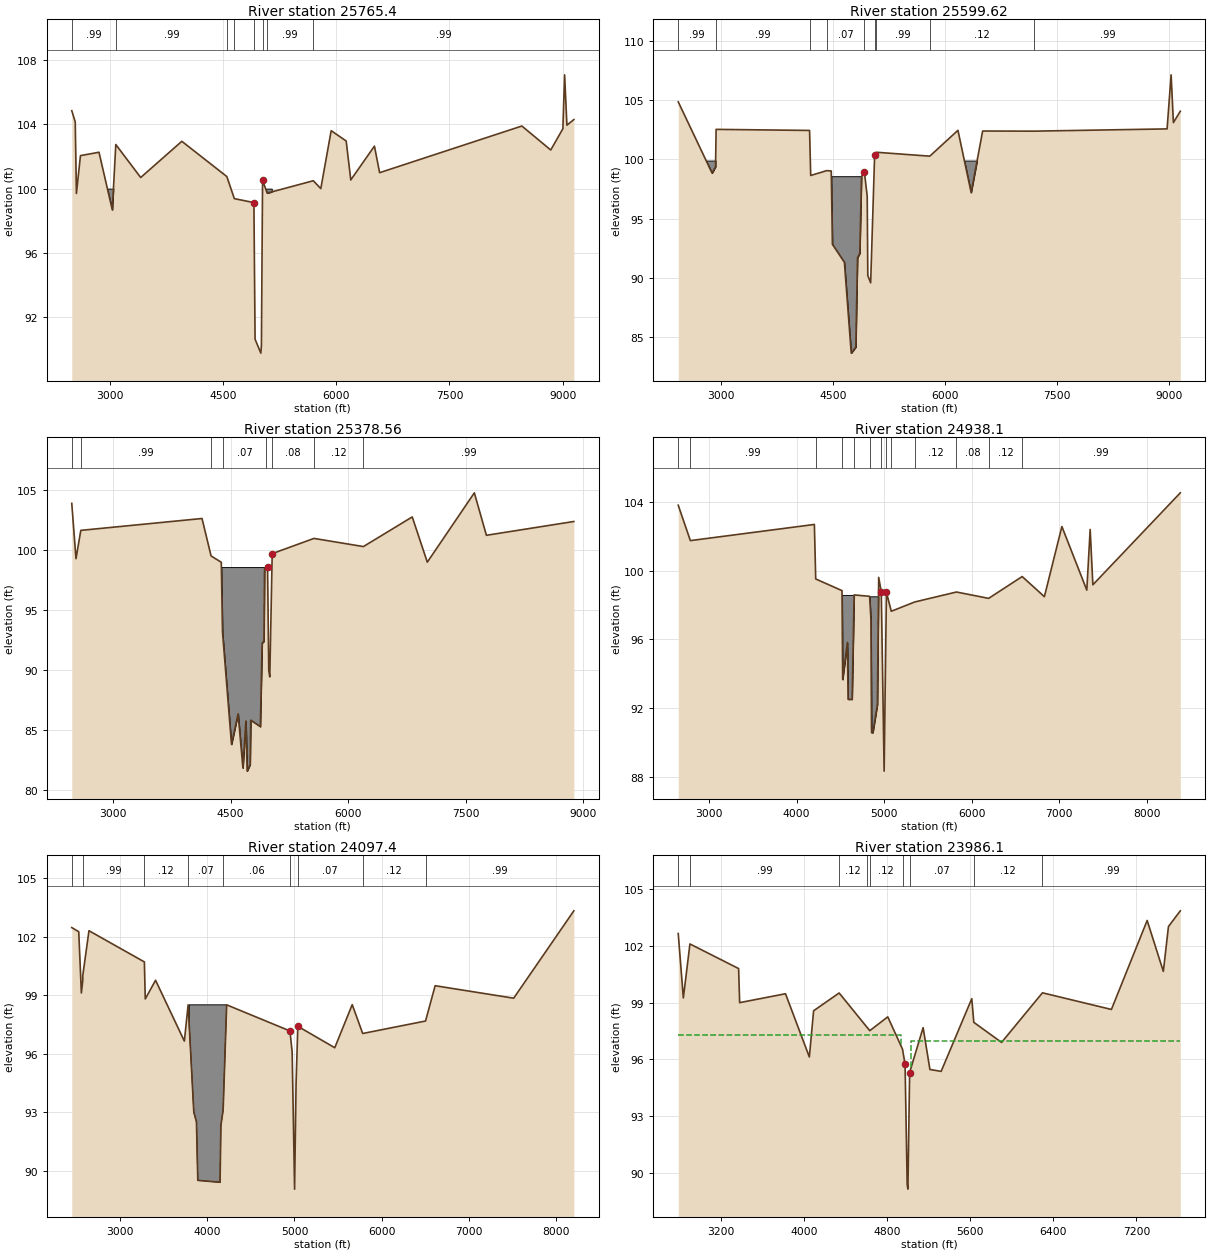
Type RM Length L Ch R = 1 ,25765.4 ,164,168,167
BEGIN DESCRIPTION:
EHRA Revised Cross-Section per NW Park Colony AsBuilt for LOMR dated March 2009
END DESCRIPTION:
XS GIS Cut Line= 6
 3080963.7499918  13897357.00004 3080035.499878613896057.0000387
 3079260.249957613895775.0001664 3078583.218893313895512.5670187
 3076836.331334213894837.9550269 3075311.250016613894249.0000368
#Sta/Elev= 30
 2493.58  104.84 2539.66  104.15 2555.02    99.7 2608.78  102.05 2854.53  102.26
 3031.16   98.68 3077.24  102.74 3407.47  100.69 3952.74  102.94 4549.28  100.75
 4648.58   99.38 4908.28   99.13 4923.57   90.65    5000   89.78 5007.64   90.26
 5022.93  100.52 5084.08   99.72 5695.55  100.49 5794.94     100 5932.56   103.6
 6131.33  102.96  6192.5  100.54 6505.95  102.64 6574.76  100.99 8460.39  103.89
 8843.23   102.4 9004.02  103.72 9026.99  107.07 9057.61  103.94  9149.5  104.29
#Mann= 8 ,-1 , 0
 2493.58     .99       0 3077.24     .99       0 4549.28     .08       0
 4648.58     .08       0 4908.28     .04       0 5022.93     .12       0
 5084.08     .99       0 5695.55     .99       0
#Block Obstruct= 2 ,-1
 2933.58 3063.58     100 5068.58 5144.58     100
Bank Sta=4908.28,5022.93
XS Rating Curve= 0 ,0
Exp/Cntr=0.3,0.1

Type RM Length L Ch R = 1 ,25599.62,102,221,297
BEGIN DESCRIPTION:
EHRA Added Cross-Section per NW Park Colony AsBuilt for LOMR dated March 2009
Area outside of NW Park Colony and Vogel Creek based on 2001 LiDAR
END DESCRIPTION:
XS GIS Cut Line= 5
 3081012.1255048 13897321.343316 3080039.045923613895959.0319024
  3079975.35344213895874.1085935 3079127.7607607 13895544.841824
 3075321.4940224 13894222.895193
#Sta/Elev= 30
 2432.66  104.85 2885.76   98.84 2931.83   99.38 2939.51  102.53 4190.21  102.44
 4205.38   98.64 4419.27   99.05  4480.4   99.02 4495.69   92.84 4656.15   91.32
 4747.84   83.66 4808.97   84.17 4831.89   91.71 4862.46   92.08 4885.38   98.57
 4923.59   98.94 4961.79   96.88 4969.43    90.2 5007.64   89.59 5061.13   100.4
 5084.05   100.6 5798.93  100.27 6175.71  102.45 6352.57    97.2 6506.36  102.39
 7198.41  102.38 8974.67  102.57  9028.5  107.13 9059.26   103.1 9151.53  104.06
#Mann= 9 ,-1 , 0
 2432.66     .99       0 2939.51     .99       0 4190.21     .12       0
 4419.27     .07       0 4923.59     .04       0 5061.13     .07       0
 5084.05     .99       0 5798.93     .12       0 7198.41     .99       0
#Block Obstruct= 3 ,-1
 4466.83 4887.63   98.58 2432.66 4190.21    99.9 5084.05 9151.53    99.9
Bank Sta=4923.59,5061.13
XS Rating Curve= 0 ,0
Exp/Cntr=0.3,0.1

Type RM Length L Ch R = 1 ,25378.56,306,441,502
BEGIN DESCRIPTION:
EHRA Added Cross-Section per NW Park Colony AsBuilt for LOMR dated March 2009
Area outside of NW Park Colony and Vogel Creek based on 2001 LiDAR
END DESCRIPTION:
XS GIS Cut Line= 5
 3081133.072297413897218.4302696 3079979.859745313895794.4634662
 3079454.137406313895542.9033096 3079373.757237913895327.1460156
 3075905.514882113893863.5027114
#Sta/Elev= 30
 2472.01  103.89  2525.9   99.28  2587.5  101.64    4135  102.63 4250.48   99.51
 4381.06   98.98  4396.4   93.17 4511.43    83.8 4595.78   86.35 4657.13   81.83
 4695.47   85.75 4710.81   81.57 4749.15   82.12 4756.82   85.82 4879.51   85.28
 4902.53   92.24 4925.55    92.4 4933.23   98.43 4956.25   98.71  4971.6   98.62
 4986.95   89.96    5000   89.42 5030.87    99.7 5563.92  100.97 6195.18  100.29
 6818.74  102.76 7011.19   98.99 7611.65  104.77 7765.62  101.23 8881.86  102.38
#Mann= 8 ,-1 , 0
 2472.01     .04       0  2587.5     .99       0 4250.48     .12       0
  4396.4     .07       0 4956.25     .04       0 5030.87     .08       0
 5563.92     .12       0 6195.18     .99       0
#Block Obstruct= 1 ,-1
 4315.47 4958.17   98.58
Bank Sta=4971.6,5030.87
XS Rating Curve= 0 ,0
Exp/Cntr=0.3,0.1

Type RM Length L Ch R = 1 ,24938.1 ,879,841,420
BEGIN DESCRIPTION:
EHRA Revised Cross-Section per NW Park Colony AsBuilt for LOMR dated March 2009
END DESCRIPTION:
XS GIS Cut Line= 6
 3081337.249896213897087.0001677 3079872.5000704 13895473.999974
 3079833.999974413895308.0001019 3079762.499942313895009.0000376
 3078699.368773713894268.9732288  3077235.49987513893249.9999718
#Sta/Elev= 30
  2647.8   103.8 2786.38  101.74    4203  102.68  4218.4   99.51 4518.66   98.83
 4526.36   93.66 4580.25   95.82 4587.95   92.51 4634.14   92.51 4657.24   98.58
 4834.03    98.5 4848.84   97.17 4856.25   90.57 4871.07   90.57 4922.93    92.2
 4937.75    99.6  4967.4   98.76    5000   88.33  5026.1   98.73 5081.57   97.63
 5349.16   98.17 5826.55   98.75 6194.03   98.38 6576.81   99.65 6830.57   98.48
 7030.58  102.56 7315.22   98.86 7353.68  102.39 7384.45   99.17 8383.35  104.52
#Mann= 13 ,-1 , 0
  2647.8     .04       0 2786.38     .99       0  4218.4     .07       0
 4518.66     .07       0 4657.24     .07       0 4834.03     .07       0
  4967.4     .04       0  5026.1     .12       0 5081.57     .07       0
 5349.16     .12       0 5826.55     .08       0 6194.03     .12       0
 6576.81     .99       0
#Block Obstruct= 2 ,-1
  4447.6 4657.24   98.58 4834.03 4940.55    98.5
Bank Sta=4967.4,5026.1
XS Rating Curve= 0 ,0
Exp/Cntr=0.3,0.1

Type RM Length L Ch R = 1 ,24097.4 ,263,111,97
BEGIN DESCRIPTION:
Interpolated Channel - LIDAR overbanks
RAMONA - XS 4
EHRA Revised Cross-Section per NW Park Colony AsBuilt for LOMR dated March 2009
END DESCRIPTION:
XS GIS Cut Line= 5
      3081979.71     13896717.04      3080521.73     13894798.05
      3080302.16     13894737.48      3080066.58     13894733.87
      3077717.22     13893069.23
#Sta/Elev= 30
  2448.7  102.46  2528.7  102.25  2558.7   99.11 2574.83   99.75 2574.83     100
 2645.75   102.3  3280.7   100.7  3290.7    98.8  3408.7   99.76  3738.7   96.64
 3782.13    98.5 3847.06      93 3877.32    92.5 3892.79    89.5 4147.88    89.4
 4157.24    92.3 4182.92    93.1  4223.4    98.5  4948.7   97.16 4973.71   96.09
 5001.75   89.05  5018.7   94.45  5038.7    97.4  5462.1    96.3  5662.1   98.51
  5782.1   97.03  6502.1   97.67  6612.1   99.48  7512.1   98.84  8201.4  103.32
#Mann= 9 ,-1 , 0
  2448.7     .04       0 2574.83     .99       0  3280.7     .12       0
 3782.13     .07       0 4182.92     .06       0  4948.7     .04       0
  5038.7     .07       0  5782.1     .12       0  6502.1     .99       0
#Block Obstruct= 1 ,-1
    3795 4238.96    98.5
Bank Sta=4948.7,5038.7
XS Rating Curve= 0 ,0
Exp/Cntr=0.5,0.3

Type RM Length L Ch R = 1 ,23986.1 ,60,61,62
BEGIN DESCRIPTION:
Upstream Section of Bridge/Culvert/Weir
RAMONA - XS 3
EHRA Revised Cross-Section per NW Park Colony AsBuilt for LOMR dated March 2009
END DESCRIPTION:
XS GIS Cut Line= 5
      3082013.09     13896626.37      3080829.68     13894668.39
      3080421.43     13894656.06      3080099.96      13894643.2
       3077750.6     13892978.56
#Sta/Elev= 30
2791.985  102.65 2841.13   99.25  2904.5   102.1 3372.99   100.8 3382.99      99
 3824.12   99.47 4053.48   96.13 4094.44   98.57 4340.18   99.51 4609.52   97.69
 4635.08   97.52    4808   98.25 4950.13   96.54 4974.45   95.74 4994.93   89.39
 5001.89   89.15 5017.54   94.98 5018.44   95.31 5148.19   97.68 5213.64   95.47
 5321.53   95.37 5616.42   99.21 5635.84   97.96 5903.12    96.9 6296.32   99.52
 6959.83   98.64 7303.87  103.34 7459.51  100.65 7508.66  103.02 7622.77  103.85
#Mann= 9 ,-1 , 0
2791.985     .04       0  2904.5     .99       0 4340.18     .12       0
 4609.52     .07       0 4635.08     .12       0 4950.13     .04       0
 5017.54     .07       0 5635.84     .12       0 6296.32     .99       0
#XS Ineff= 2 , 0
       0 4933.25    97.35034.823       0      97
Permanent Ineff=
       F       F
Bank Sta=4974.45,5018.44
XS Rating Curve= 0 ,0
Skew Angle= 35
Exp/Cntr=0.5,0.3