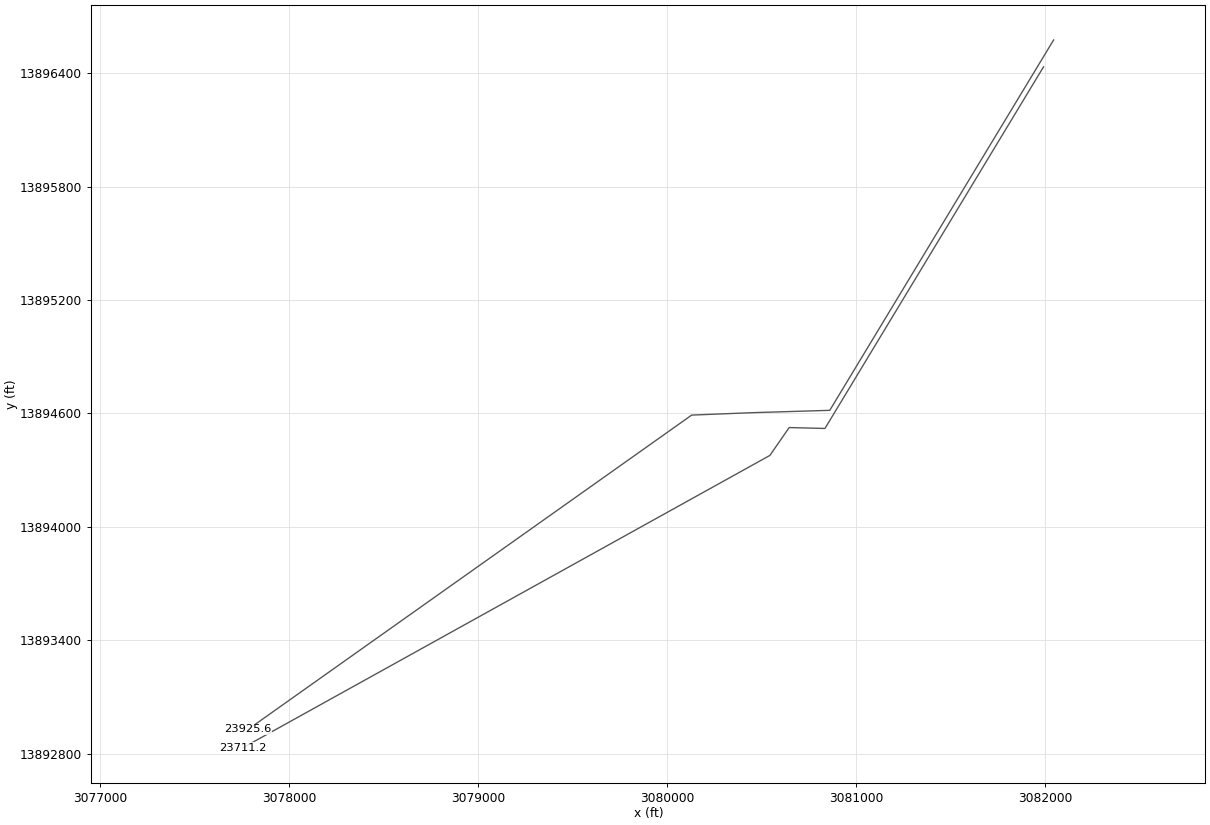
HEC-RAS study E121-00-00.prj: E121-00-00 LOMR

--- E121-00-00.g01 (geometry) --- (continued)

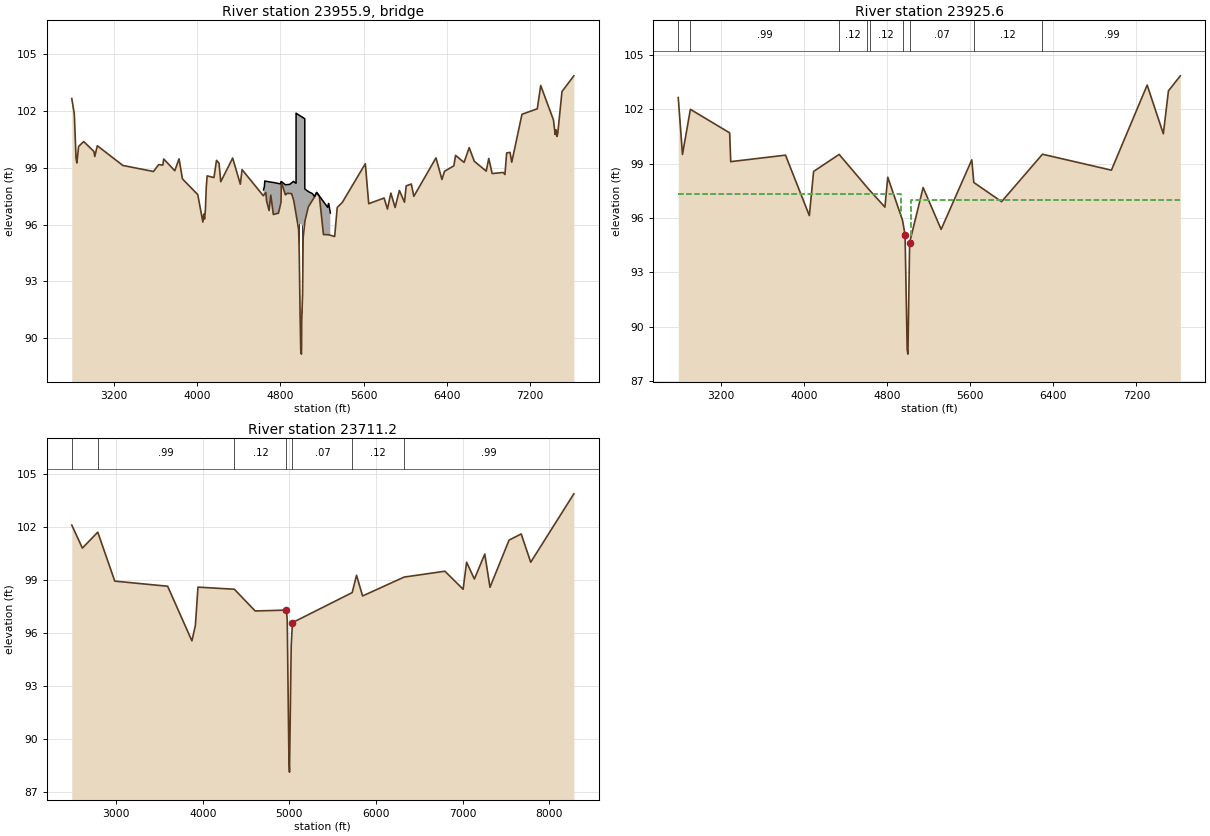
Type RM Length L Ch R = 3 ,23955.9 ,,,
BEGIN DESCRIPTION:
RAMONA
Structure ID: E121-00-00-18
END DESCRIPTION:
Bridge Culvert--1,0,-1,-1, 0
Deck Dist Width WeirC Skew NumUp NumDn MinLoCord MaxHiCord MaxSubmerge Is_Ogee
11,39,2.6,35, 61, 61, , , 0.95, 0, ,,,
 4636.88 4645.07 4649.25 4665.63 4706.59 4722.97  4796.7    4808 4847.15 4849.94
 4867.31 4889.01  4907.2 4926.04 4926.86  4942.5  4942.6 4942.67 4945.62 4949.95
 4950.04 4950.13 4963.06 4974.45 4978.63 4980.02  4980.1 4988.38 4994.44 4994.93
 4998.29 5001.89 5003.12 5004.11 5006.56 5012.95 5013.03 5017.54 5018.44 5026.38
 5026.47    5034 5034.09 5034.18 5035.97 5066.52 5067.92 5098.06 5108.06 5128.12
 5133.37 5148.19 5157.94 5174.32  5198.9 5223.47 5254.19 5262.38 5263.78 5272.62
 5280.08
   97.83      98    98.3   98.28   98.24   98.23   98.15   98.27    98.1    98.1
   98.11   98.12    98.2   98.28   98.28    98.2    98.2    98.2   98.19   98.18
  101.88  101.88  101.83  101.79  101.78  101.77  101.77  101.74  101.72  101.72
  101.71  101.69  101.69  101.69  101.68  101.66  101.65  101.64  101.64  101.61
  101.61  101.58  101.58   97.88   97.87   97.75   97.74   97.66   97.63   97.48
   97.54    97.7   97.63   97.51   97.32   97.14   96.91   97.11   97.11   96.84
   96.61
                                                                                
                                                                           96.13
   96.13   96.13   96.13   96.09   96.08   96.07   96.07   96.04   96.02   96.02
   96.01   95.99   95.99   95.99   95.98   95.96   95.95   95.94   95.94   95.91
   95.72
                                                                                
        
 4636.88 4645.07 4649.25 4665.63 4706.59 4722.97  4796.7    4808 4847.15 4849.94
 4867.31 4889.01  4907.2 4926.04 4926.86  4942.5  4942.6 4942.67 4945.62 4949.95
 4950.04 4950.13 4963.06 4974.45 4978.63 4980.02  4980.1 4988.38 4994.44 4994.93
 4998.29 5001.89 5003.12 5004.11 5006.56 5012.95 5013.03 5017.54 5018.44 5026.38
 5026.47    5034 5034.09 5034.18 5035.97 5066.52 5067.92 5098.06 5108.06 5128.12
 5133.37 5148.19 5157.94 5174.32  5198.9 5223.47 5254.19 5262.38 5263.78 5272.62
 5280.08
   97.83      98    98.3   98.28   98.24   98.23   98.15   98.27    98.1    98.1
   98.11   98.12    98.2   98.28   98.28    98.2    98.2    98.2   98.19   98.18
  101.88  101.88  101.83  101.79  101.78  101.77  101.77  101.74  101.72  101.72
  101.71  101.69  101.69  101.69  101.68  101.66  101.65  101.64  101.64  101.61
  101.61  101.58  101.58   97.88   97.87   97.75   97.74   97.66   97.63   97.48
   97.54    97.7   97.63   97.51   97.32   97.14   96.91   97.11   97.11   96.84
   96.61
                                                                                
                                                                           96.13
   96.13   96.13   96.13   96.09   96.08   96.07   96.07   96.04   96.02   96.02
   96.01   95.99   95.99   95.99   95.98   95.96   95.95   95.94   95.94   95.91
   95.72
                                                                                
        
Pier Skew, UpSta & Num, DnSta & Num=  ,4978.628, 2 ,4978.628, 2 , 0 , 0 , 0 ,,
     1.3     1.3
   90.23   96.98
     1.3     1.3
   89.57   96.32
Pier Skew, UpSta & Num, DnSta & Num=  ,5006.56, 2 ,5006.56, 2 , 0 , 0 , 0 ,,
     1.3     1.3
   90.23   96.98
     1.3     1.3
   89.57   96.32
Abutment Skew #Up #Dn= , 2 , 2
4039.4844077.084
   96.79   94.72
4039.4844077.084
   96.13   94.06
Abutment Skew #Up #Dn= , 2 , 2
4110.0144123.521
   92.35   95.91
4110.0144123.521
   91.69   95.25
BR Coef= 1 , 1 , 0 ,1.25, 0 ,,,0.8,0,2,0,
WSPro=,,,, 1 ,,,, 0 ,,,, 0 ,,,,-1 ,-1 ,-1 , 0 , 0 , 0 , 0 , 0
BR U #Sta/Elev= 129
2791.985  102.65 2816.56  101.84 2832.94   99.51 2841.13   99.25 2857.52  100.12
 2906.67  100.38 3004.96   99.86 3013.16   99.59 3037.73  100.16 3283.48   99.12
 3578.37    98.8 3627.52   99.16 3668.48   99.14 3676.67   99.46 3783.16   98.84
 3824.12   99.47 3856.88   98.41 4004.33   97.58 4053.48   96.13 4061.67   96.55
 4069.86   96.29 4078.05   96.82 4086.25   97.98 4094.44   98.57 4159.97   98.48
 4184.54   99.39 4209.12   99.23  4225.5   98.26 4340.18   99.51 4413.91   98.13
 4430.29    98.9 4609.52   97.69 4635.08   97.52 4659.65   97.69 4666.04   97.25
 4690.61   96.74    4707   97.55 4731.57   96.53 4780.72    96.6  4805.3   97.18
    4808   98.25 4847.15   97.57 4849.94   97.58 4867.31   97.65 4889.01   97.64
  4907.2   97.63 4926.04    97.3 4926.86   97.29  4942.5    96.8  4942.6    96.8
 4942.67   96.79 4945.62    96.7 4949.95   96.56 4950.04   96.55 4950.13   96.55
 4963.06   96.13 4974.45   95.75 4980.02   94.75  4980.1   94.72 4988.38   91.43
 4994.44   89.61 4994.93    89.4 4998.29   89.21 5001.89   89.16 5003.12   89.62
 5004.11   90.83 5006.56   91.34 5012.95    92.3 5013.03   92.35 5017.54   94.99
 5018.44   95.32 5026.38   95.72 5026.47   95.72    5034    96.1 5034.09   96.11
 5034.18   96.11 5035.97    96.2 5066.52   96.92 5067.92   96.93 5098.06   97.19
 5108.06   97.28 5128.12   97.46 5133.37   97.52 5148.19   97.68 5157.94   97.61
 5174.32   97.49 5213.64   95.47 5264.19   95.46 5321.53   95.37  5346.1    96.9
 5395.25   97.17 5616.42   99.21 5635.84   97.96 5649.19    97.1 5796.63    97.4
  5829.4   96.82 5862.17   97.66 5903.12    96.9 5944.08    97.8 5993.23   97.18
 6009.61   98.04 6058.76   98.14 6083.34   97.49 6296.32   99.52 6353.66   98.38
 6378.23   98.81 6468.34    99.1 6484.72   99.65 6566.64   99.28 6615.79  100.06
 6664.94   99.34 6779.62   98.82 6804.19   99.49 6836.96   98.69 6943.45   98.75
 6959.83   98.64 6976.21   99.78 7008.98   99.81 7025.36   99.29 7123.66  101.82
 7271.11  102.11 7303.87  103.34 7426.75  101.52 7443.13  100.75 7451.32     101
 7459.51  100.65 7467.71   100.8 7508.66  103.02 7622.77  103.85
BR U #Mann= 8
2791.985     .99 4340.18     .12 4609.52     .07 4635.08     .12 4950.13     .04
 5017.54     .07 5635.84     .12 6296.32     .99
BR U Banks=4974.45,5018.44
BR D #Sta/Elev= 129
2791.985  102.65 2816.56  101.84 2832.94   99.51 2841.13   99.25 2857.52  100.12
 2906.67  100.38 3004.96   99.86 3013.16   99.59 3037.73  100.16 3283.48   99.12
 3578.37    98.8 3627.52   99.16 3668.48   99.14 3676.67   99.46 3783.16   98.84
 3824.12   99.47 3856.88   98.41 4004.33   97.58 4053.48   96.13 4061.67   96.55
 4069.86   96.29 4078.05   96.82 4086.25   97.98 4094.44   98.57 4159.97   98.48
 4184.54   99.39 4209.12   99.23  4225.5   98.26 4340.18   99.51 4413.91   98.13
 4430.29    98.9 4609.52   97.69 4635.08   97.52 4659.65   97.69 4666.04   97.25
 4690.61   96.74    4707   97.55 4731.57   96.53 4780.72    96.6  4805.3   97.18
    4808   98.25 4847.15   97.57 4849.94   97.58 4867.31   97.65 4889.01   97.64
  4907.2   97.63 4926.04   96.64 4926.86   96.63  4942.5   96.14  4942.6   96.14
 4942.67   96.13 4945.62   96.04 4949.95    95.9 4950.04   95.89 4950.13   95.89
 4963.06   95.47 4974.45   95.09 4980.02   94.09  4980.1   94.06 4988.38   90.77
 4994.44   88.95 4994.93   88.74 4998.29   88.55 5001.89    88.5 5003.12   88.96
 5004.11   90.17 5006.56   90.68 5012.95   91.64 5013.03   91.69 5017.54   94.33
 5018.44   94.66 5026.38   95.06 5026.47   95.06    5034   95.44 5034.09   95.45
 5034.18   95.45 5035.97   95.54 5066.52   96.26 5067.92   96.27 5098.06   97.19
 5108.06   97.28 5128.12   97.46 5133.37   97.52 5148.19   97.68 5157.94   97.61
 5174.32   97.49 5213.64   95.47 5264.19   95.46 5321.53   95.37  5346.1    96.9
 5395.25   97.17 5616.42   99.21 5635.84   97.96 5649.19    97.1 5796.63    97.4
  5829.4   96.82 5862.17   97.66 5903.12    96.9 5944.08    97.8 5993.23   97.18
 6009.61   98.04 6058.76   98.14 6083.34   97.49 6296.32   99.52 6353.66   98.38
 6378.23   98.81 6468.34    99.1 6484.72   99.65 6566.64   99.28 6615.79  100.06
 6664.94   99.34 6779.62   98.82 6804.19   99.49 6836.96   98.69 6943.45   98.75
 6959.83   98.64 6976.21   99.78 7008.98   99.81 7025.36   99.29 7123.66  101.82
 7271.11  102.11 7303.87  103.34 7426.75  101.52 7443.13  100.75 7451.32     101
 7459.51  100.65 7467.71   100.8 7508.66  103.02 7622.77  103.85
BR D #Mann= 8
2791.985     .99 4340.18     .12 4609.52     .07 4635.08     .12 4950.13     .04
 5017.54     .07 5635.84     .12 6296.32     .99
BR D Banks=4974.45,5018.44
BC Design=,, 0 ,, 0 ,,,,,,
BC HTab HWMax=104.09
BC Use User HTab Curves=0
BC User HTab FreeFlow(D)= 0

Type RM Length L Ch R = 1 ,23925.6 ,28,214,365
BEGIN DESCRIPTION:
Downstream Section of Bridge/Culvert/Weir
RAMONA - XS 2
EHRA Revised Cross-Section per NW Park Colony AsBuilt for LOMR dated March 2009
END DESCRIPTION:
XS GIS Cut Line= 5
      3082046.29     13896576.91      3080861.47      13894616.6
      3080450.53     13894604.19      3080130.56     13894591.39
      3077782.42     13892927.61
#Sta/Elev= 30
2791.985  102.65 2832.94   99.51  2908.9     102 3286.99   100.7 3296.99   99.11
 3824.12   99.47 4053.48   96.13 4094.44   98.57 4340.18   99.51 4609.52   97.69
 4635.08   97.52 4780.72    96.6    4808   98.25 4950.13   95.87 4974.45   95.07
 4994.93   88.72 5001.89   88.48 5017.54   94.31 5018.44   94.64 5148.19   97.68
 5321.53   95.37 5616.42   99.21 5635.84   97.96 5903.12    96.9 6296.32   99.52
 6959.83   98.64 7303.87  103.34 7459.51  100.65 7508.66  103.02 7622.77  103.85
#Mann= 9 ,-1 , 0
2791.985     .04       0  2908.9     .99       0 4340.18     .12       0
 4609.52     .07       0 4635.08     .12       0 4950.13     .04       0
 5017.54     .07       0 5635.84     .12       0 6296.32     .99       0
#XS Ineff= 2 , 0
       0 4933.25    97.3 5034.82       0      97
Permanent Ineff=
       F       F
#Block Obstruct= 2 , 0
       0  2908.9    99.5               0
Bank Sta=4974.45,5018.44
XS Rating Curve= 0 ,0
Skew Angle= 35
Exp/Cntr=0.5,0.3

Type RM Length L Ch R = 1 ,23711.2 ,26,268,837
BEGIN DESCRIPTION:
Interpolated Channel - LIDAR overbanks
RAMONA - XS 1
EHRA Revised Cross-Section per NW Park Colony AsBuilt for LOMR dated March 2009
END DESCRIPTION:
XS GIS Cut Line= 5
      3081993.05      13896434.9      3080836.01     13894520.64
      3080646.66     13894525.48      3080544.44     13894377.84
      3077756.96     13892831.64
#Sta/Elev= 30
  2488.7   102.1  2611.3   100.8  2788.7   101.7    2985   98.93    3595   98.64
    3875   95.55    3915   96.42    3945   98.59    4365   98.47    4605   97.24
    4965   97.29    4975   96.74 4994.54    88.8 5000.87   88.12 5020.82   95.27
    5035   96.58  5724.5   98.28  5774.5   99.26  5844.5   98.09  6324.5   99.16
  6794.5   99.49  7004.5   98.47  7044.5     100  7134.5   99.05  7254.5  100.46
  7314.5   98.58  7534.5  101.25  7674.5   101.6  7784.5     100  8282.1  103.87
#Mann= 7 ,-1 , 0
  2488.7     .04       0  2788.7     .99       0    4365     .12       0
    4965     .04       0    5035     .07       0  5724.5     .12       0
  6324.5     .99       0
Bank Sta=4965,5035
XS Rating Curve= 0 ,0
Exp/Cntr=0.3,0.1