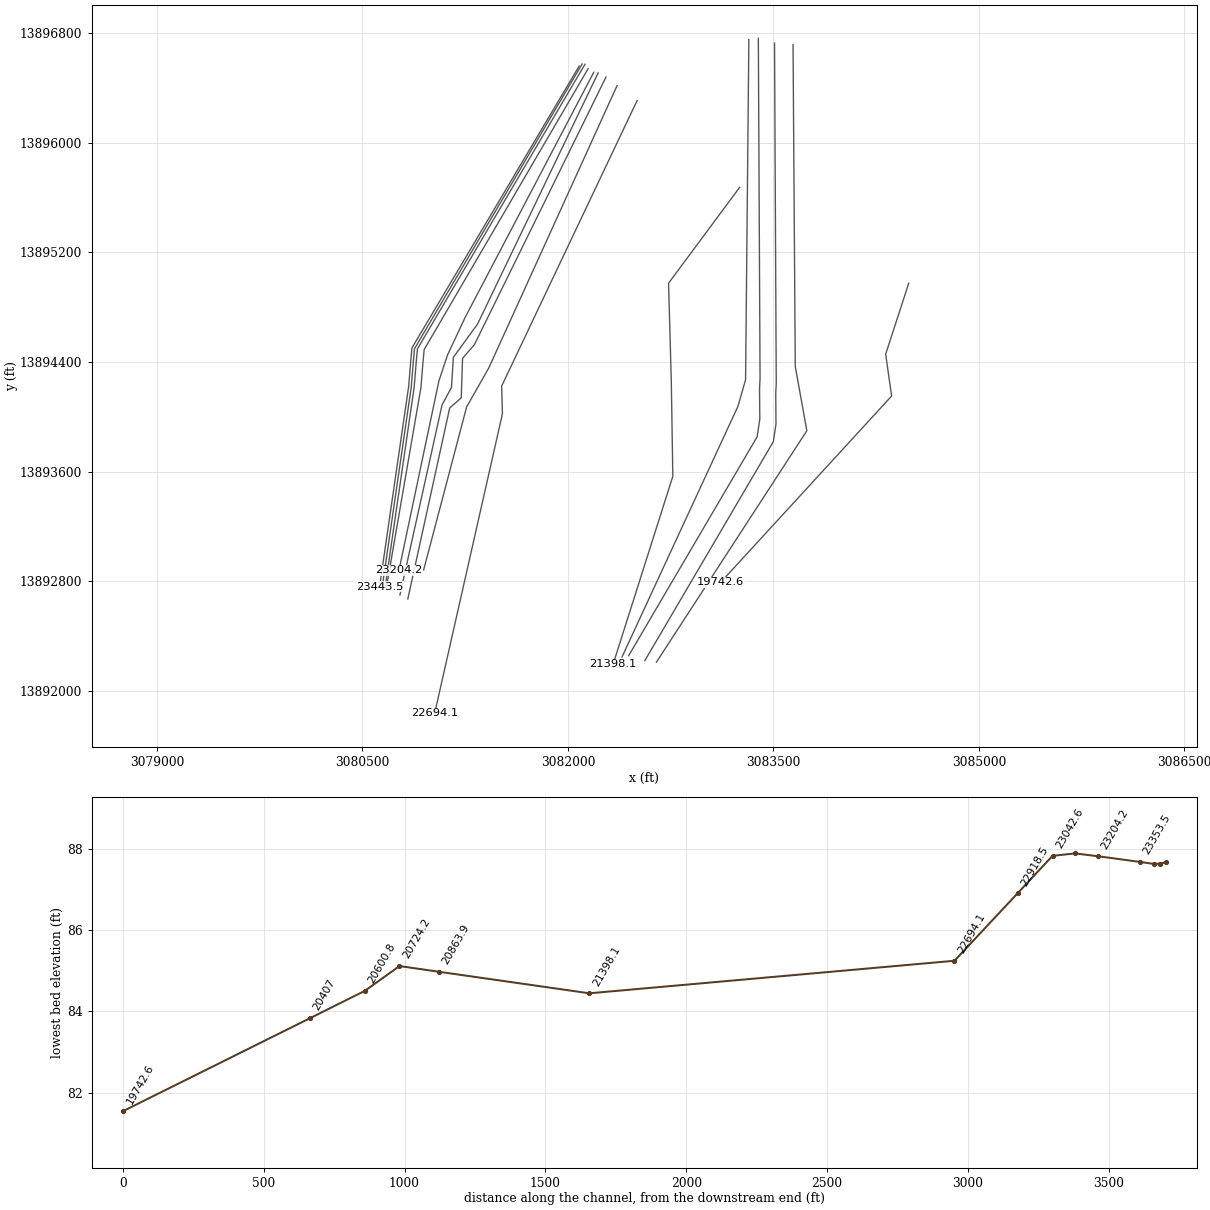
HEC-RAS study E121-00-00.prj: E121-00-00 LOMR

--- E121-00-00.g01 (geometry) --- (continued)

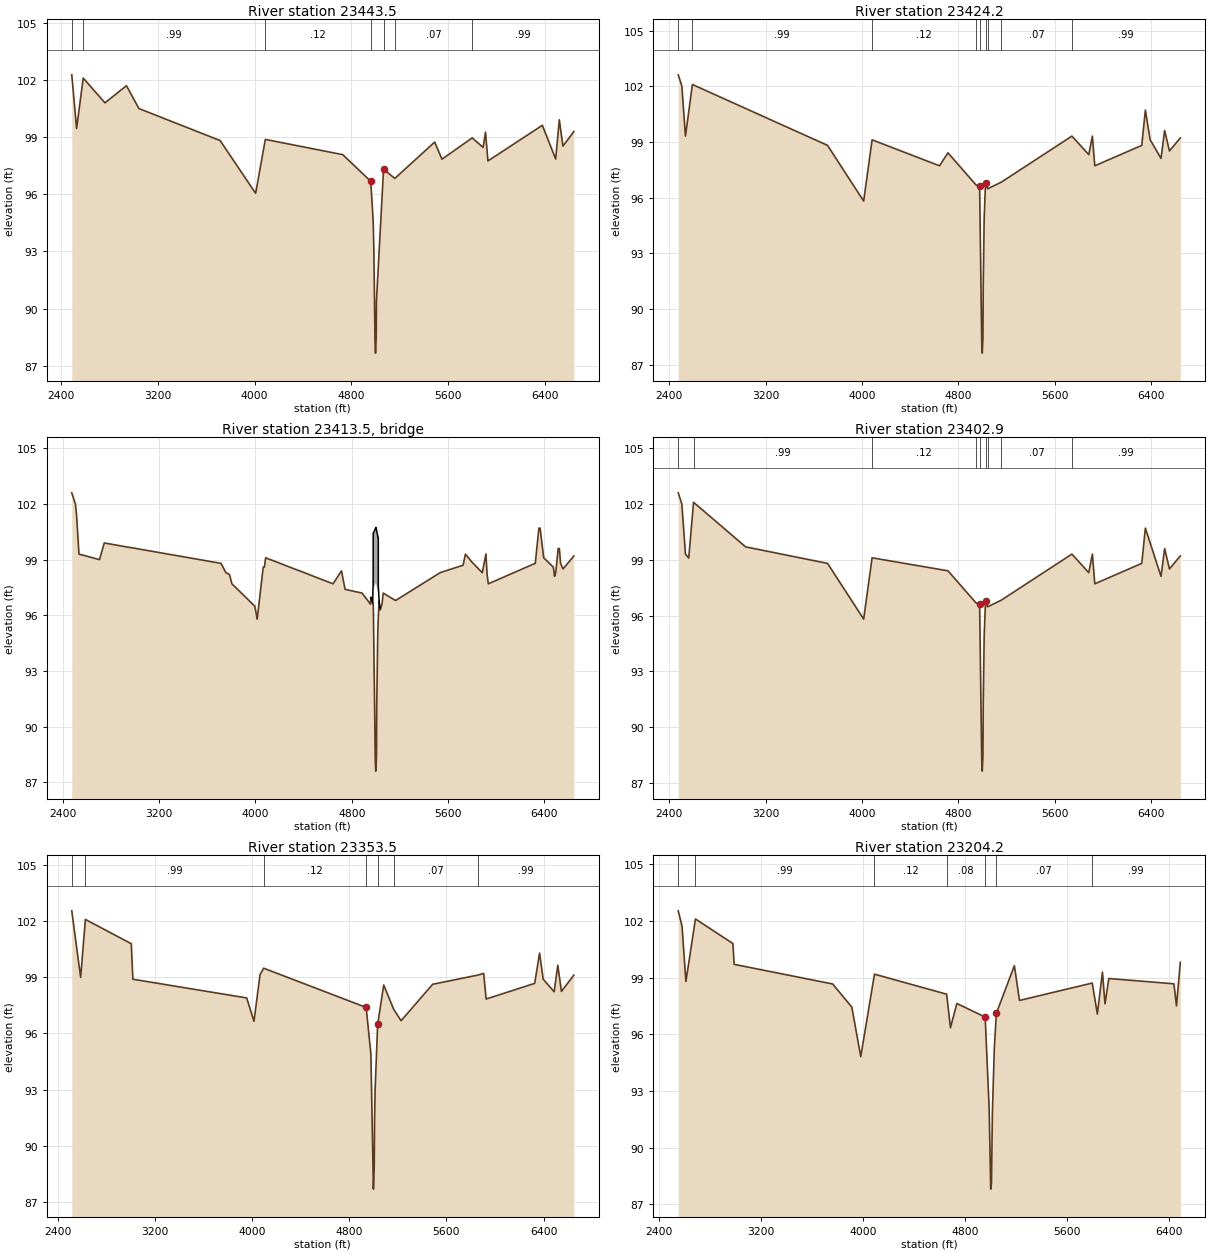
Type RM Length L Ch R = 1 ,23443.5 ,17,19,21
BEGIN DESCRIPTION:
Interpolated Channel - LIDAR overbanks
FOOT BRIDGE - XS 4
Cross-section stops at highest point.  The ground elevation decreases down to unknown trib.  Spill
EHRA Revised Cross-Section per NW Park Colony AsBuilt for LOMR dated March 2009
END DESCRIPTION:
XS GIS Cut Line= 5
      3082082.26     13896560.49      3080861.96     13894503.48
      3080851.49     13894388.32      3080838.38     13894225.99
      3080625.76     13892761.13
#Sta/Elev= 30
  2488.7  102.27  2528.7   99.45 2583.35   102.1  2763.2   100.8  2940.9   101.7
  3043.9   100.5  3714.9   98.82  4008.7   96.05  4088.7   98.88  4728.7   98.08
  4960.4   96.68  4980.4   94.58 4985.95   93.12 4995.24   88.33 4999.59   87.66
  5005.4   88.49 5007.15   90.38  5066.1   97.32  5158.9   96.83  5488.9   98.74
  5548.9   97.84  5798.9   98.96  5888.9   98.46  5908.9   99.26  5928.9   97.75
  6378.9   99.62  6488.9   97.85  6518.9   99.91  6548.9   98.53  6639.1   99.29
#Mann= 7 ,-1 , 0
  2488.7     .04       0 2583.35     .99       0  4088.7     .12       0
  4960.4     .04       0  5066.1     .12       0  5158.9     .07       0
  5798.9     .99       0
Bank Sta=4960.4,5066.1
XS Rating Curve= 0 ,0
Exp/Cntr=0.5,0.3

Type RM Length L Ch R = 1 ,23424.2 ,22,21,20
BEGIN DESCRIPTION:
Upstream Section of Bridge/Culvert/Weir;
FOOT BRIDGE - XS 3
Cross-section stops at highest point.  The ground elevation decreases down to unknown trib.  Spill
EHRA Revised Cross-Section per NW Park Colony AsBuilt for LOMR dated March 2009
END DESCRIPTION:
XS GIS Cut Line= 5
      3082103.72     13896575.63       3080880.8     13894497.83
      3080870.33     13894382.67      3080857.21     13894220.34
       3080644.6     13892755.48
#Sta/Elev= 30
  2474.9  102.62  2504.9  102.02  2534.9   99.32  2592.5   102.1  3714.9   98.82
  4014.9   95.82  4084.9   99.12  4644.9   97.72  4714.9   98.42  4948.1   96.69
  4977.9   96.62  4995.2   88.32  4999.5   87.63  5005.4   88.41  5007.9   91.23
  5015.7    94.9  5026.7   96.77  5044.7   96.48  5158.2   96.84  5744.4   99.32
  5884.4   98.32  5914.4   99.32  5934.4   97.72  6324.4   98.82  6354.4  100.72
  6394.4   99.12  6484.4   98.12  6514.4   99.62  6554.4   98.52  6644.6   99.22
#Mann= 9 ,-1 , 0
  2474.9     .04       0  2592.5     .99       0  4084.9     .12       0
  4948.1     .05       0  4977.9     .04       0  5026.7     .05       0
  5044.7     .12       0  5158.2     .07       0  5744.4     .99       0
#XS Ineff= 2 , 0
       0  4967.9   96.11  5036.7       0    96.3
Permanent Ineff=
       F       F
Bank Sta=4977.9,5026.7
XS Rating Curve= 0 ,0
Exp/Cntr=0.5,0.3

Type RM Length L Ch R = 3 ,23413.5 ,,,
BEGIN DESCRIPTION:
FOOT BRIDGE
Structure ID: E121-00-00-17
END DESCRIPTION:
Bridge Culvert--1,0,-1,-1, 0
Deck Dist Width WeirC Skew NumUp NumDn MinLoCord MaxHiCord MaxSubmerge Is_Ogee
9,3,2.6,0, 33, 33, , , 0.95, 0, ,,,
    4960  4974.6  4974.8 4977.01  4977.1  4977.6  4977.9 4977.99  4978.1 4978.21
    4980  4980.1    4986  4991.7  4994.2  4995.2  4999.5  5000.8  5005.4  5005.9
  5007.9  5015.7  5018.4  5018.5 5020.49  5020.6 5020.71  5021.3 5021.59  5021.7
  5026.7  5028.6  5034.6
   96.96   96.67   96.96   97.62   97.65    97.8   97.81   97.81  100.41  100.41
  100.44  100.44  100.52  100.61  100.64  100.66  100.72  100.74   100.6  100.59
  100.53  100.29  100.21  100.21  100.15  100.15   97.55   97.53    97.5   97.48
   96.89   96.66   96.38
   96.95   96.66   96.66   96.62   97.25    97.4   97.41   97.41   97.41   97.41
   97.44   97.44   97.52   97.61   97.64   97.66   97.72   97.74    97.6   97.59
   97.53   97.29   97.21   97.21   97.15   97.15   97.15   97.13    97.1   96.04
   96.75   96.66   96.37
    4960  4974.6  4974.8 4977.01  4977.1  4977.6  4977.9 4977.99  4978.1 4978.21
    4980  4980.1    4986  4991.7  4994.2  4995.2  4999.5  5000.8  5005.4  5005.9
  5007.9  5015.7  5018.4  5018.5 5020.49  5020.6 5020.71  5021.3 5021.59  5021.7
  5026.7  5028.6  5034.6
   96.96   96.67   96.96   97.62   97.65    97.8   97.81   97.81  100.41  100.41
  100.44  100.44  100.52  100.61  100.64  100.66  100.72  100.74   100.6  100.59
  100.53  100.29  100.21  100.21  100.15  100.15   97.55   97.53    97.5   97.48
   96.89   96.66   96.38
   96.95   96.66   96.66   96.62   97.25    97.4   97.41   97.41   97.41   97.41
   97.44   97.44   97.52   97.61   97.64   97.66   97.72   97.74    97.6   97.59
   97.53   97.29   97.21   97.21   97.15   97.15   97.15   97.13    97.1   96.04
   96.75   96.66   96.37
Abutment Skew #Up #Dn= , 2 , 2
  4976.9  4980.1
   97.25   96.22
  4976.9  4980.1
   97.25   96.22
Abutment Skew #Up #Dn= , 2 , 2
  5018.5 5021.79
   95.59    97.1
  5018.5 5021.79
   95.59    97.1
BR Coef= 1 , 1 , 0 ,1.25, 0 ,,,0.8,0,2,0,
WSPro=,,,, 1 ,,,, 0 ,,,, 0 ,,,,-1 ,-1 ,-1 , 0 , 0 , 0 , 0 , 0
BR U #Sta/Elev= 123
  2474.9   102.6  2476.4  102.57  2504.9     102  2514.9   101.4  2516.4  101.24
  2526.4  100.19  2534.9    99.3  2546.4   99.28  2556.4   99.26  2576.4   99.23
  2704.9      99  2744.9    99.9  2926.4   99.69  2966.4   99.65  3714.9    98.8
  3754.9    98.3  3784.9    98.2  3804.9    97.7  3986.4   96.55  3994.9    96.5
  4006.4    96.1  4014.9    95.8  4056.4   98.12  4064.9    98.6  4074.9    98.6
  4076.4   98.68  4084.9    99.1  4116.4   99.02  4146.4   98.95  4186.4   98.85
  4316.4   98.52  4336.4   98.47  4366.4    98.4  4556.4   97.92  4644.9    97.7
  4714.9    98.4  4736.4   97.68  4744.9    97.4  4885.9    97.2  4904.6   97.04
  4948.1   96.67  4954.6   96.61  4955.9    96.6  4957.2   96.97    4960   96.95
  4974.6   96.66  4974.8   96.66 4977.01   96.62  4977.1   96.62  4977.6   96.61
  4977.9    96.6 4977.99   96.59  4978.1   96.57 4978.21   96.55    4980   96.27
  4980.1   96.22    4986   93.14  4991.7    90.3  4994.2   88.79  4995.2    88.3
  4999.5   87.61  5000.8   87.78  5005.4   88.39  5005.9   88.86  5007.9   91.21
  5015.7   94.88  5018.4   95.56  5018.5   95.59 5020.49   95.87  5020.6   95.89
 5020.71    95.9  5021.3   95.99 5021.59   96.03  5021.7   96.04  5026.7   96.75
  5028.6   96.66  5034.6   96.37  5036.2   96.29  5037.6   96.31  5044.7   96.46
  5051.5    96.6  5061.5    97.2  5064.6   97.19  5084.6   97.11  5114.6   96.99
  5158.2   96.82  5164.4    96.8  5169.3   96.82  5534.4    98.3  5724.4    98.7
  5744.4    99.3  5794.4    98.9  5819.3   98.73  5879.3   98.33  5884.4    98.3
  5909.3   99.13  5914.4    99.3  5924.4    98.2  5929.3   97.95  5934.4    97.7
  5959.3   97.77  6319.3   98.79  6324.4    98.8  6349.3  100.38  6354.4   100.7
  6364.4   100.7  6369.3  100.44  6394.4    99.1  6399.3   99.07  6469.3   98.63
  6474.4    98.6  6484.4    98.1  6489.3    98.2  6494.4    98.3  6514.4    99.6
  6519.3    99.6  6524.4    99.6  6534.4    98.8  6539.3   98.73  6549.3   98.58
  6554.4    98.5  6607.8   98.91  6644.6    99.2
BR U #Mann= 8
  2474.9     .99  4084.9     .12  4948.1     .05  4977.9     .04  5026.7     .05
  5044.7     .12  5158.2     .07  5744.4     .99
BR U Banks=4977.9,5026.7
BR D #Sta/Elev= 123
  2474.9   102.6  2476.4  102.57  2504.9     102  2514.9   101.4  2516.4  101.24
  2526.4  100.19  2534.9    99.3  2546.4   99.28  2556.4   99.26  2576.4   99.23
  2704.9      99  2744.9    99.9  2926.4   99.69  2966.4   99.65  3714.9    98.8
  3754.9    98.3  3784.9    98.2  3804.9    97.7  3986.4   96.55  3994.9    96.5
  4006.4    96.1  4014.9    95.8  4056.4   98.12  4064.9    98.6  4074.9    98.6
  4076.4   98.68  4084.9    99.1  4116.4   99.02  4146.4   98.95  4186.4   98.85
  4316.4   98.52  4336.4   98.47  4366.4    98.4  4556.4   97.92  4644.9    97.7
  4714.9    98.4  4736.4   97.68  4744.9    97.4  4885.9    97.2  4904.6   97.04
  4948.1   96.67  4954.6   96.61  4955.9    96.6  4957.2   96.97    4960   96.95
  4974.6   96.66  4974.8   96.66 4977.01   96.62  4977.1   96.62  4977.6   96.61
  4977.9    96.6 4977.99   96.59  4978.1   96.57 4978.21   96.55    4980   96.27
  4980.1   96.22    4986   93.14  4991.7    90.3  4994.2   88.79  4995.2    88.3
  4999.5   87.61  5000.8   87.78  5005.4   88.39  5005.9   88.86  5007.9   91.21
  5015.7   94.88  5018.4   95.56  5018.5   95.59 5020.49   95.87  5020.6   95.89
 5020.71    95.9  5021.3   95.99 5021.59   96.03  5021.7   96.04  5026.7   96.75
  5028.6   96.66  5034.6   96.37  5036.2   96.29  5037.6   96.31  5044.7   96.46
  5051.5    96.6  5061.5    97.2  5064.6   97.19  5084.6   97.11  5114.6   96.99
  5158.2   96.82  5164.4    96.8  5169.3   96.82  5534.4    98.3  5724.4    98.7
  5744.4    99.3  5794.4    98.9  5819.3   98.73  5879.3   98.33  5884.4    98.3
  5909.3   99.13  5914.4    99.3  5924.4    98.2  5929.3   97.95  5934.4    97.7
  5959.3   97.77  6319.3   98.79  6324.4    98.8  6349.3  100.38  6354.4   100.7
  6364.4   100.7  6369.3  100.44  6394.4    99.1  6399.3   99.07  6469.3   98.63
  6474.4    98.6  6484.4    98.1  6489.3    98.2  6494.4    98.3  6514.4    99.6
  6519.3    99.6  6524.4    99.6  6534.4    98.8  6539.3   98.73  6549.3   98.58
  6554.4    98.5  6607.8   98.91  6644.6    99.2
BR D #Mann= 8
  2474.9     .99  4084.9     .12  4948.1     .05  4977.9     .04  5026.7     .05
  5044.7     .12  5158.2     .07  5744.4     .99
BR D Banks=4977.9,5026.7
BC Design=,, 0 ,, 0 ,,,,,,
BC HTab HWMax=102.62
BC Use User HTab Curves=0
BC User HTab FreeFlow(D)= 0

Type RM Length L Ch R = 1 ,23402.9 ,51,50,35
BEGIN DESCRIPTION:
Downstream Section of Bridge/Culvert/Weir;
FOOT BRIDGE - XS 2
Cross-section stops at highest point.  The ground elevation decreases down to unknown trib.  Spill
EHRA Revised Cross-Section per NW Park Colony AsBuilt for LOMR dated March 2009
END DESCRIPTION:
XS GIS Cut Line= 5
      3082124.42     13896573.39      3080902.07     13894496.56
       3080891.7     13894382.54      3080878.57     13894220.08
      3080665.94     13892755.06
#Sta/Elev= 30
  2474.9  102.61  2504.9  102.01  2534.9   99.31  2562.1    99.1  2602.2   102.1
  3034.5    99.7  3714.9   98.81  4014.9   95.81  4084.9   99.11  4714.9   98.41
  4948.1   96.68  4977.9   96.61  4995.2   88.31  4999.5   87.62  5005.4    88.4
  5007.9   91.22  5015.7   94.89  5026.7   96.76  5044.7   96.47  5158.2   96.83
  5744.4   99.31  5884.4   98.31  5914.4   99.31  5934.4   97.71  6324.4   98.81
  6354.4  100.71  6484.4   98.11  6514.4   99.61  6554.4   98.51  6644.6   99.21
#Mann= 9 ,-1 , 0
  2474.9     .04       0  2602.2     .99       0  4084.9     .12       0
  4948.1     .05       0  4977.9     .04       0  5026.7     .05       0
  5044.7     .12       0  5158.2     .07       0  5744.4     .99       0
#XS Ineff= 2 , 0
       0 4971.23   96.11 5033.37       0    96.3
Permanent Ineff=
       F       F
Bank Sta=4977.9,5026.7
XS Rating Curve= 0 ,0
Exp/Cntr=0.5,0.3

Type RM Length L Ch R = 1 ,23353.5 ,150,149,101
BEGIN DESCRIPTION:
Interpolated Channel - LIDAR overbanks
FOOT BRIDGE - XS 1
Cross-section stops at highest point.  The ground elevation decreases down to unknown trib.  Spill
EHRA Revised Cross-Section per NW Park Colony AsBuilt for LOMR dated March 2009
END DESCRIPTION:
XS GIS Cut Line= 5
      3082147.44     13896540.94      3080951.04     13894490.91
      3080940.68     13894376.89      3080927.55     13894214.43
      3080675.43     13892753.78
#Sta/Elev= 30
  2516.3  102.56  2589.3      99  2628.4   102.1  3006.4   100.8  3019.4    98.9
  3956.3    97.9  4016.3   96.65  4066.3   99.15  4096.3   99.49  4939.9   97.39
 4978.78    94.9 4999.59   87.67 5006.32   88.85 5009.18   91.38 5013.36   92.94
  5034.4   96.48  5084.4   98.59  5167.4   97.28  5227.4   96.68  5487.4   98.63
  5857.4   99.12  5907.4   99.21  5927.4   97.84  6327.4   98.68  6367.4   100.3
  6397.4    98.9  6487.4   98.23  6517.4   99.65  6547.4   98.25  6649.6   99.12
#Mann= 7 ,-1 , 0
  2516.3     .04       0  2628.4     .99       0  4096.3     .12       0
  4939.9     .04       0  5034.4     .12       0  5167.4     .07       0
  5857.4     .99       0
Bank Sta=4939.9,5034.4
XS Rating Curve= 0 ,0
Exp/Cntr=0.3,0.1

Type RM Length L Ch R = 1 ,23204.2 ,92,82,55
BEGIN DESCRIPTION:
Interpolated Channel - LIDAR overbanks
FENNEMORE - XS 4
EHRA Revised Cross-Section per NW Park Colony AsBuilt for LOMR dated March 2009
END DESCRIPTION:
XS GIS Cut Line= 5
      3082188.72     13896514.87       3081248.9     13894723.47
       3081120.5     13894449.31      3081058.44     13894261.28
       3080767.4      13892881.6
#Sta/Elev= 30
  2551.6  102.53  2581.6  101.71  2611.6   98.79  2686.5   102.1  2979.8   100.8
  2989.8    99.7  3761.6   98.66  3911.6   97.44  3981.6   94.82 4089.12   99.18
  4654.6   98.12  4684.6   96.35  4734.6   97.63 4956.47   96.91 4987.55    92.1
 4999.85   87.81 5005.66   88.12 5013.05   91.88 5028.06   95.27 5044.09   97.11
  5185.3   99.63  5225.3   97.79  5795.3   98.71  5835.3   97.07  5875.3   99.29
  5895.3   97.61  5925.3   98.95  6435.3   98.67  6455.3    97.5  6485.3   99.81
#Mann= 7 ,-1 , 0
  2551.6     .04       0  2686.5     .99       0 4089.12     .12       0
  4654.6     .08       0 4956.47     .04       0 5044.09     .07       0
  5795.3     .99       0
Bank Sta=4956.47,5044.09
XS Rating Curve= 0 ,0
Exp/Cntr=0.5,0.3

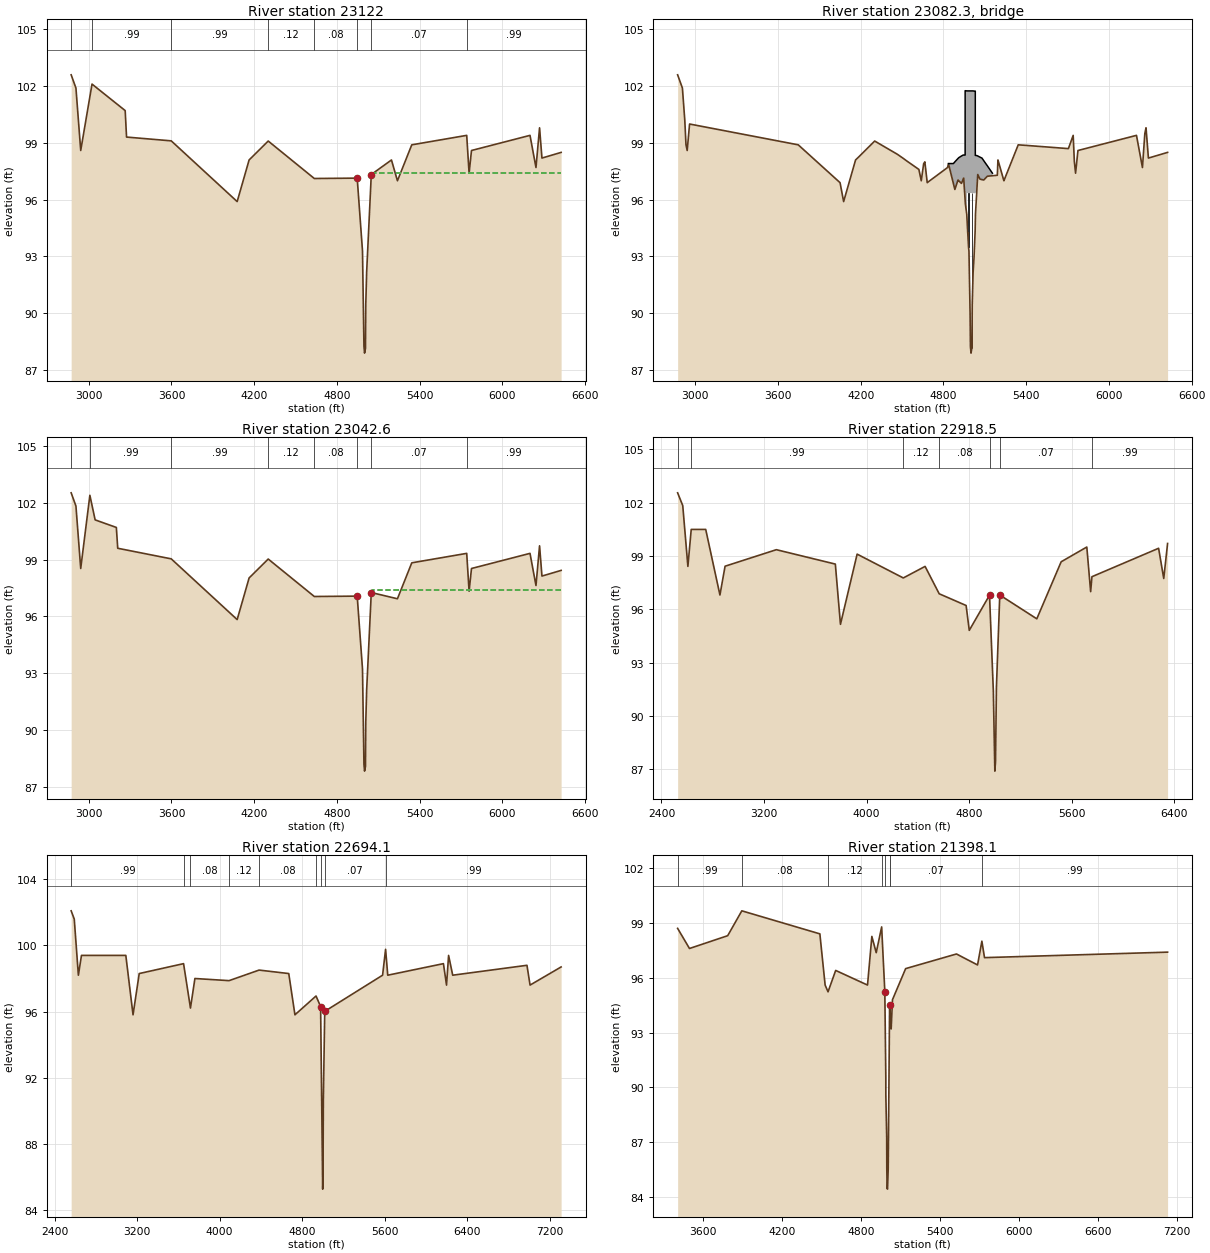
Type RM Length L Ch R = 1 ,23122   ,79,80,81
BEGIN DESCRIPTION:
Upstream Section of Bridge/Culvert/Weir;
FENNEMORE - XS 3
Cross-section stops at highest point.  The ground elevation decreases down to unknown trib.  Spill
EHRA Revised Cross-Section per NW Park Colony AsBuilt for LOMR dated March 2009
END DESCRIPTION:
XS GIS Cut Line= 6
      3082220.99     13896510.85       3081341.2     13894678.26
      3081164.18     13894434.82      3081150.74     13894216.08
      3081081.67     13894087.52      3080774.09     13892700.26
#Sta/Elev= 30
 2872.53  102.59 2907.17  101.89 2941.81   98.59  3023.8   102.1  3264.2   100.7
  3274.2    99.3 3598.17    99.1  4076.3   95.89  4162.9   98.09 4301.47   99.09
 4635.75   97.11 4946.74   97.13 4985.11   93.28 4995.67   88.24    5000   87.88
 5006.67   88.13 5008.84   90.45 5015.16   92.15 5048.85   97.32 5195.21   98.09
 5238.51   96.99 5342.43   98.89  5740.8   99.39 5758.12   97.39 5775.44   98.59
  6199.8   99.39  6243.1   97.69 6269.08   99.79  6286.4   98.19  6425.4   98.49
#Mann= 8 ,-1 , 0
 2872.53     .04       0  3023.8     .99       0 3598.17     .99       0
 4301.47     .12       0 4635.75     .08       0 4946.74     .04       0
 5048.85     .07       0  5740.8     .99       0
#XS Ineff= 2 , 0
       0 4940.97   96.315054.628       0    97.4
Permanent Ineff=
       F       F
Bank Sta=4946.74,5048.85
XS Rating Curve= 0 ,0
Skew Angle= 30
Exp/Cntr=0.5,0.3

Type RM Length L Ch R = 3 ,23082.3 ,,,
BEGIN DESCRIPTION:
FENNEMORE
Structure ID: E121-00-00-16
END DESCRIPTION:
Bridge Culvert--1,0,-1,-1, 0
Deck Dist Width WeirC Skew NumUp NumDn MinLoCord MaxHiCord MaxSubmerge Is_Ogee
18,43,2.6,30, 46, 46, , , 0.95, 0, ,,,
  4836.5 4872.01 4882.92 4905.78 4910.98 4930.81 4943.11 4946.74  4957.3  4957.4
 4957.49  4959.3 4969.09 4969.69 4969.79 4969.89 4969.95 4982.08 4985.11 4993.42
 4994.55 4995.67    5000 5005.46 5006.67 5007.37 5007.71 5008.84 5015.16 5021.66
 5029.71  5029.8 5030.91 5031.01  5031.1 5032.39 5042.78 5042.87 5042.96 5048.85
  5064.7 5079.42 5092.58 5118.39 5118.48 5155.28
   97.91   97.91      98   98.18   98.22   98.31   98.36   98.36   98.36  101.76
  101.76  101.76  101.75  101.75  101.75  101.75  101.75  101.75  101.75  101.75
  101.75  101.75  101.75  101.75  101.75  101.75  101.75  101.75  101.75  101.74
  101.74  101.74  101.74  101.74   98.34   98.34   98.33   98.33   98.33   98.31
   98.25    98.2   98.06   97.79   97.79    97.4
    97.9   96.86   96.54   97.04      97   96.86   97.08   97.14   95.98   95.97
   95.96   95.76   95.23   95.15   95.14   95.12   96.35   96.35   96.35   96.35
   96.35   96.35   96.35   96.35   96.35   96.35   96.35   96.35   96.35   96.34
   96.34   96.34   96.34   96.34   96.34   96.34   96.56   96.57   96.59   97.33
   97.09   97.06   97.04   97.24   97.24   97.27
  4836.5 4872.01 4882.92 4905.78 4910.98 4930.81 4943.11 4946.74  4957.3  4957.4
 4957.49  4959.3 4969.09 4969.69 4969.79 4969.89 4969.95 4982.08 4985.11 4993.42
 4994.55 4995.67    5000 5005.46 5006.67 5007.37 5007.71 5008.84 5015.16 5021.66
 5029.71  5029.8 5030.91 5031.01  5031.1 5032.39 5042.78 5042.87 5042.96 5048.85
  5064.7 5079.42 5092.58 5118.39 5118.48 5155.28
   97.91   97.91      98   98.18   98.22   98.31   98.36   98.36   98.36  101.76
  101.76  101.76  101.75  101.75  101.75  101.75  101.75  101.75  101.75  101.75
  101.75  101.75  101.75  101.75  101.75  101.75  101.75  101.75  101.75  101.74
  101.74  101.74  101.74  101.74   98.34   98.34   98.33   98.33   98.33   98.31
   98.25    98.2   98.06   97.79   97.79    97.4
    97.9   96.86   96.54   97.04      97   96.86   97.08   97.14   95.98   95.97
   95.96   95.76   95.23   95.15   95.14   95.12   96.35   96.35   96.35   96.35
   96.35   96.35   96.35   96.35   96.35   96.35   96.35   96.35   96.35   96.34
   96.34   96.34   96.34   96.34   96.34   96.34   96.56   96.57   96.59   97.33
   97.09   97.06   97.04   97.24   97.24   97.27
Pier Skew, UpSta & Num, DnSta & Num=  ,4982.078, 2 ,4982.078, 2 , 0 , 0 , 0 ,,
     1.3     1.3
   92.44   97.35
     1.3     1.3
   92.44   97.35
Pier Skew, UpSta & Num, DnSta & Num=  ,5006.673, 2 ,5006.673, 2 , 0 , 0 , 0 ,,
     1.3     1.3
   87.14   97.35
     1.3     1.3
   87.14   97.35
Abutment Skew #Up #Dn= , 2 , 2
4358.9654372.121
   94.33   96.56
4358.9654372.121
   94.33   96.56
BR Coef= 1 , 1 , 0 ,1.25, 0 ,,,0.8,-1,2,0,
WSPro=,,,, 1 ,,,, 0 ,,,, 0 ,,,,-1 ,-1 ,-1 , 0 , 0 , 0 , 0 , 0
BR U #Sta/Elev= 131
 2872.53   102.6 2907.17   101.9 2924.49   100.2 2933.15    98.9 2941.81    98.6
 2959.13     100 3598.17   99.11 3747.21    98.9 4031.18   97.03 4039.84   96.97
  4048.5   96.91 4050.32    96.9 4057.16   96.64 4065.82    96.3  4076.3    95.9
  4091.8   96.29  4162.9    98.1 4187.07   98.27 4239.03   98.65 4273.67    98.9
 4282.33   98.96 4301.38    99.1 4301.47    99.1 4308.31   99.07 4334.29   98.96
 4466.01    98.4  4507.5   98.19 4533.48   98.05 4602.76    97.7 4611.42   97.65
 4620.08   97.61  4621.9    97.6 4628.74   97.36 4635.75   97.12 4639.22      97
 4646.06   97.36 4656.54    97.9 4663.38   97.98  4665.2      98 4682.52    96.9
 4689.36   96.94 4829.74    97.7  4836.5    97.9 4872.01   96.86 4882.92   96.54
 4905.78   97.04 4910.98      97 4930.81   96.86 4943.11   97.08 4946.74   97.14
  4957.3   95.98  4957.4   95.97 4957.49   95.96  4959.3   95.76 4969.09   95.23
 4969.69   95.15 4969.79   95.14 4969.89   95.12 4969.95   95.11 4982.08   93.48
 4985.11   93.29 4993.42   89.94 4994.55   88.96 4995.67   88.25    5000   87.89
 5005.46   88.13 5006.67   88.14 5007.37   88.89 5007.71   89.26 5008.84   90.46
 5015.16   92.16 5021.66   92.93 5029.71    94.3  5029.8   94.33 5030.91   94.73
 5031.01   94.76  5031.1   94.79 5032.39   95.25 5042.78   96.56 5042.87   96.57
 5042.96   96.59 5048.85   97.33  5064.7   97.09 5079.42   97.06 5092.58   97.04
 5118.39   97.24 5118.48   97.24 5155.28   97.27 5158.57   97.27 5190.79   97.29
 5195.21    98.1 5200.49   97.97 5238.51      97 5243.79    97.1 5342.43    98.9
 5365.03   98.89 5399.68   98.87 5668.14   98.72  5676.8   98.72 5694.12   98.71
 5702.78    98.7 5706.16    98.7 5711.44   98.81  5720.1   98.98 5737.43   99.33
 5740.72    99.4  5740.8    99.4 5749.46      98 5758.12    97.4 5775.44    98.6
 5780.73   98.61 5988.57      99 5997.23   99.02 6023.21   99.07 6075.18   99.17
 6144.46    99.3 6196.42   99.39  6199.8    99.4 6213.74   98.85  6222.4   98.51
 6231.06   98.17 6239.72   97.83  6243.1    97.7 6248.38   98.25 6257.04   99.15
 6260.42    99.5  6265.7   99.68 6269.08    99.8  6286.4    98.2 6400.89   98.45
  6425.4    98.5
BR U #Mann= 7
 2872.53     .99 3598.17     .99 4301.47     .12 4635.75     .08 4946.74     .04
 5048.85     .07  5740.8     .99
BR U Banks=4946.74,5048.85
BR D #Sta/Elev= 131
 2872.53   102.6 2907.17   101.9 2924.49   100.2 2933.15    98.9 2941.81    98.6
 2959.13     100 3598.17   99.11 3747.21    98.9 4031.18   97.03 4039.84   96.97
  4048.5   96.91 4050.32    96.9 4057.16   96.64 4065.82    96.3  4076.3    95.9
  4091.8   96.29  4162.9    98.1 4187.07   98.27 4239.03   98.65 4273.67    98.9
 4282.33   98.96 4301.38    99.1 4301.47    99.1 4308.31   99.07 4334.29   98.96
 4466.01    98.4  4507.5   98.19 4533.48   98.05 4602.76    97.7 4611.42   97.65
 4620.08   97.61  4621.9    97.6 4628.74   97.36 4635.75   97.12 4639.22      97
 4646.06   97.36 4656.54    97.9 4663.38   97.98  4665.2      98 4682.52    96.9
 4689.36   96.94 4829.74    97.7  4836.5    97.9 4872.01   96.86 4882.92   96.54
 4905.78   97.04 4910.98      97 4930.81   96.86 4943.11   97.08 4946.74   97.14
  4957.3   95.98  4957.4   95.97 4957.49   95.96  4959.3   95.76 4969.09   95.23
 4969.69   95.15 4969.79   95.14 4969.89   95.12 4969.95   95.11 4982.08   93.48
 4985.11   93.29 4993.42   89.94 4994.55   88.96 4995.67   88.25    5000   87.89
 5005.46   88.13 5006.67   88.14 5007.37   88.89 5007.71   89.26 5008.84   90.46
 5015.16   92.16 5021.66   92.93 5029.71    94.3  5029.8   94.33 5030.91   94.73
 5031.01   94.76  5031.1   94.79 5032.39   95.25 5042.78   96.56 5042.87   96.57
 5042.96   96.59 5048.85   97.33  5064.7   97.09 5079.42   97.06 5092.58   97.04
 5118.39   97.24 5118.48   97.24 5155.28   97.27 5158.57   97.27 5190.79   97.29
 5195.21    98.1 5200.49   97.97 5238.51      97 5243.79    97.1 5342.43    98.9
 5365.03   98.89 5399.68   98.87 5668.14   98.72  5676.8   98.72 5694.12   98.71
 5702.78    98.7 5706.16    98.7 5711.44   98.81  5720.1   98.98 5737.43   99.33
 5740.72    99.4  5740.8    99.4 5749.46      98 5758.12    97.4 5775.44    98.6
 5780.73   98.61 5988.57      99 5997.23   99.02 6023.21   99.07 6075.18   99.17
 6144.46    99.3 6196.42   99.39  6199.8    99.4 6213.74   98.85  6222.4   98.51
 6231.06   98.17 6239.72   97.83  6243.1    97.7 6248.38   98.25 6257.04   99.15
 6260.42    99.5  6265.7   99.68 6269.08    99.8  6286.4    98.2 6400.89   98.45
  6425.4    98.5
BR D #Mann= 7
 2872.53     .99 3598.17     .99 4301.47     .12 4635.75     .08 4946.74     .04
 5048.85     .07  5740.8     .99
BR D Banks=4946.74,5048.85
BC Design=,, 0 ,, 0 ,,,,,,
BC HTab HWMax=102.59
BC Use User HTab Curves=0
BC User HTab FreeFlow(D)= 0

Type RM Length L Ch R = 1 ,23042.6 ,152,124,97
BEGIN DESCRIPTION:
Downstream Section of Bridge/Culvert/Weir;
FENNEMORE - XS 2
Cross-section stops at highest point.  The ground elevation decreases down to unknown trib.  Spill
EHRA Revised Cross-Section per NW Park Colony AsBuilt for LOMR dated March 2009
END DESCRIPTION:
XS GIS Cut Line= 6
      3082278.31     13896480.46      3081317.68     13894526.92
      3081231.33     13894427.14      3081221.74     13894139.32
      3081137.31     13894064.49      3080831.79       13892671.
#Sta/Elev= 30
 2872.53  102.53 2907.17  101.83 2941.81   98.53  3008.2   102.4  3046.4   101.1
  3200.2   100.7  3210.2    99.6 3598.17   99.04  4076.3   95.83  4162.9   98.03
 4301.47   99.03 4635.75   97.05 4946.74   97.07 4985.11   93.22 4995.67   88.18
    5000   87.82 5006.67   88.07 5008.84   90.39 5015.16   92.09 5048.85   97.26
 5238.51   96.93 5342.43   98.83  5740.8   99.33 5758.12   97.33 5775.44   98.53
  6199.8   99.33  6243.1   97.63 6269.08   99.73  6286.4   98.13  6425.4   98.43
#Mann= 8 ,-1 , 0
 2872.53     .04       0  3008.2     .99       0 3598.17     .99       0
 4301.47     .12       0 4635.75     .08       0 4946.74     .04       0
 5048.85     .07       0  5740.8     .99       0
#XS Ineff= 2 , 0
       0 4940.97   96.315054.625       0    97.4
Permanent Ineff=
       F       F
Bank Sta=4946.74,5048.85
XS Rating Curve= 0 ,0
Skew Angle= 30
Exp/Cntr=0.5,0.3

Type RM Length L Ch R = 1 ,22918.5 ,152,224,301
BEGIN DESCRIPTION:
Interpolated Channel - LIDAR overbanks
FENNEMORE - XS 1
EHRA Revised Cross-Section per NW Park Colony AsBuilt for LOMR dated March 2009
END DESCRIPTION:
XS GIS Cut Line= 4
      3082359.31      13896418.3      3081422.47     13894356.63
      3081261.02     13894072.59      3080947.36      13892883.2
#Sta/Elev= 30
    2526  102.56    2566  101.84    2606   98.42    2632   100.5  2745.1   100.5
    2856   96.81    2896   98.43    3296   99.36    3756   98.55    3796   95.16
    3926   99.11    4286   97.77    4456   98.42    4566   96.88    4776   96.22
  4800.5   94.82 4958.52    96.8 4988.43   91.39 5000.04    86.9 5005.29   87.43
 5012.29   91.61 5038.53   96.81  5327.3   95.47  5517.3   98.68  5717.3   99.51
  5747.3      97  5757.3   97.84  6277.3   99.44  6317.3   97.74  6347.3   99.71
#Mann= 7 ,-1 , 0
    2526     .04       0    2632     .99       0    4286     .12       0
    4566     .08       0 4958.52     .04       0 5038.53     .07       0
  5757.3     .99       0
Bank Sta=4958.52,5038.53
XS Rating Curve= 0 ,0
Exp/Cntr=0.3,0.1

Type RM Length L Ch R = 1 ,22694.1 ,936,1296,1409
BEGIN DESCRIPTION:
Cross Section X15;
Cross-section stops at highest point.  The ground elevation decreases down to unknown trib.  Spill
END DESCRIPTION:
XS GIS Cut Line= 4
      3082505.57     13896309.34      3081516.54     13894224.51
      3081522.16     13894022.21      3081027.64     13891836.23
#Sta/Elev= 30
    2561   102.1    2591   101.6    2631    98.2    2661    99.4    3091    99.4
    3161    95.8    3221    98.3    3651    98.9  3717.9   96.21    3761      98
    4092   97.87  4383.3   98.51    4671    98.3    4731    95.8  4935.5   96.94
  4979.8    96.3  5000.1   85.24  5003.7   86.62  5006.4   90.65  5019.9   96.01
  5580.9    98.2    5610   99.77  5630.9    98.2  6170.9    98.9  6200.9    97.6
  6220.9    99.4  6260.9    98.2  6980.9    98.8  7010.9    97.6  7312.1    98.7
#Mann= 9 ,-1 , 0
    2561     .99       0    3651     .12       0  3717.9     .08       0
    4092     .12       0  4383.3     .08       0  4935.5     .05       0
  4979.8     .06       0  5019.9     .07       0    5610     .99       0
Bank Sta=4979.8,5019.9
XS Rating Curve= 0 ,0
Exp/Cntr=0.3,0.1

Type RM Length L Ch R = 1 ,21398.1 ,580,534,233
BEGIN DESCRIPTION:
Cross Section X14;
Cross-section stops at highest point.  The ground elevation decreases down to unknown trib.  Spill
END DESCRIPTION:
XS GIS Cut Line= 6
      3083252.95     13895674.36      3082734.83     13894975.85
      3082754.96     13894254.94      3082758.09     13894059.14
      3082765.98     13893566.37      3082329.93     13892194.31
#Sta/Elev= 30
  3406.8    98.7  3496.8    97.6  3786.8    98.3  3894.1   99.66  4486.5    98.4
  4526.5    95.6  4548.5   95.23  4606.5    96.4  4848.2    95.6  4881.1   98.26
  4914.3   97.37  4955.5   98.78  4979.6   95.24  4987.2   90.55  4987.3   89.59
  4993.8   87.29  4994.6   85.56  4997.1   84.47  5000.2   84.44  5005.3   85.56
  5015.8   94.53  5022.3    93.8  5027.7    93.2  5037.7    94.8  5137.7    96.5
  5523.5    97.3  5683.5    96.7  5716.3      98  5736.3    97.1    7126    97.4
#Mann= 8 ,-1 , 0
  3406.8     .99       0  3894.1     .08       0  4548.5     .12       0
  4955.5     .05       0  4979.6     .06       0  5015.8     .05       0
  5022.3     .07       0  5716.3     .99       0
Bank Sta=4979.6,5015.8
XS Rating Curve= 0 ,0
Exp/Cntr=0.3,0.1

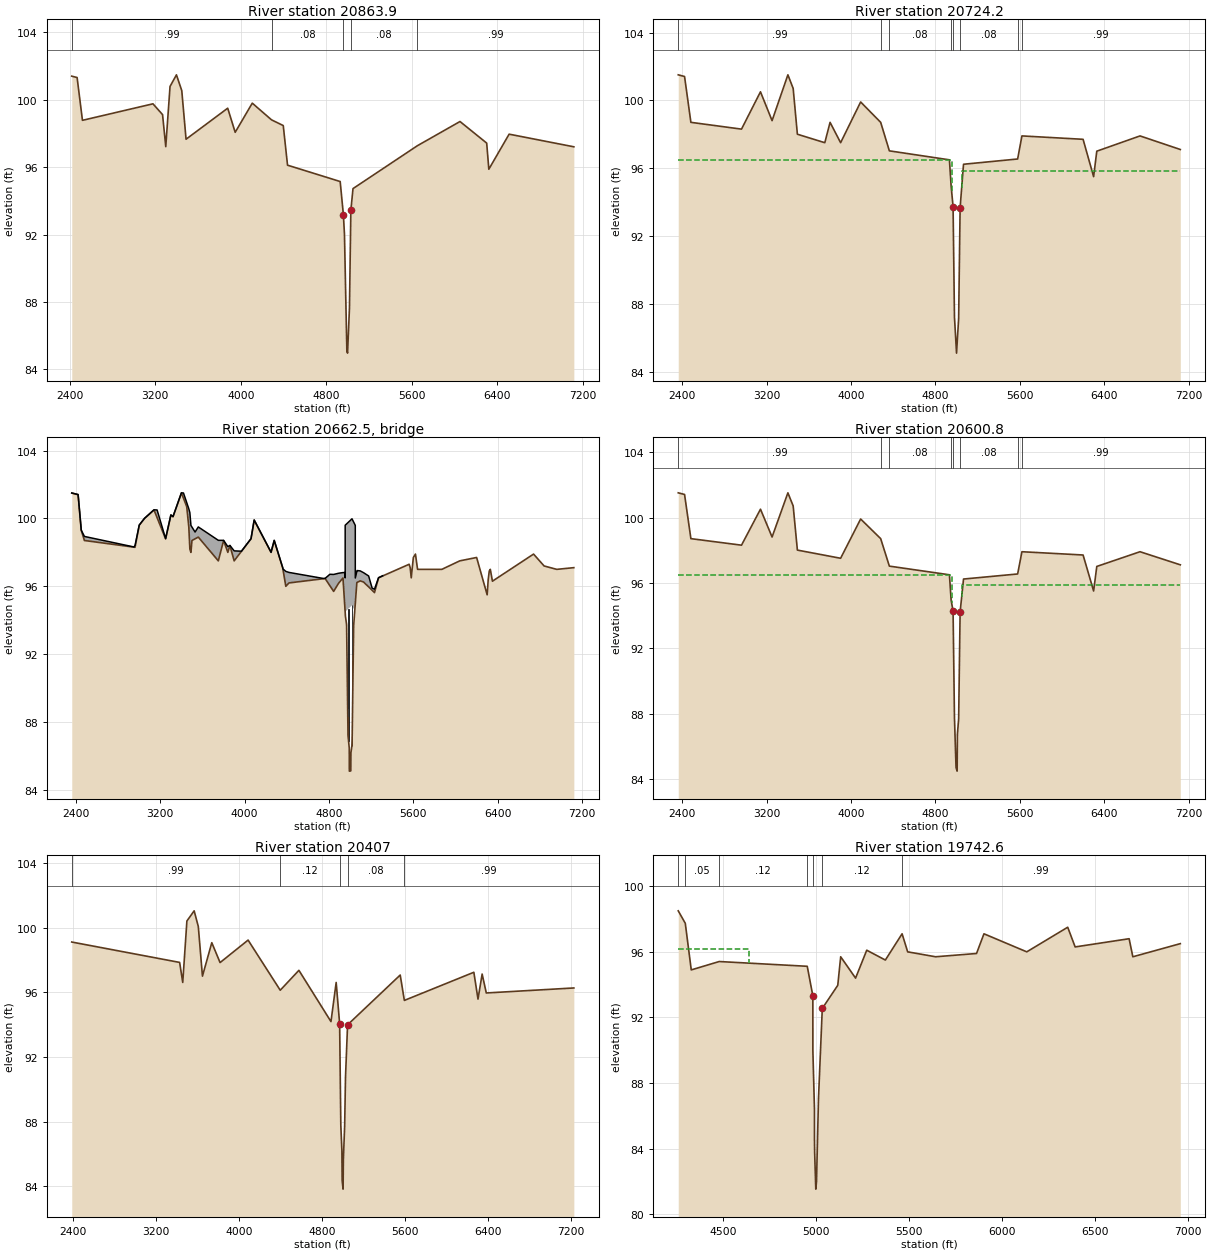
Type RM Length L Ch R = 1 ,20863.9 ,104,140,201
BEGIN DESCRIPTION:
Interpolated Channel - LIDAR overbanks
ANTOINE - XS 4
END DESCRIPTION:
XS GIS Cut Line= 4
      3083320.85     13896754.06      3083296.89     13894271.18
      3083241.26     13894077.27      3082394.99     13892247.62
#Sta/Elev= 30
    2418   101.4    2468  101.32    2518   98.78    3178   99.76    3268   99.12
    3298   97.22    3338  100.79    3398  101.48    3448  100.54    3488   97.66
    3878    99.5    3948   98.07    4108    99.8    4288   98.81    4398   98.47
    4438   96.12    4931   95.15    4961   93.18    4971   92.03 4993.59    85.1
 5000.04   84.97 5017.89   87.66    5031   93.45    5051   94.73  5652.7   97.27
  6052.7   98.71  6302.7   97.43  6322.7   95.88  6512.7   97.96  7118.6   97.21
#Mann= 5 ,-1 , 0
    2418     .99       0    4288     .08       0    4961     .04       0
    5031     .08       0  5652.7     .99       0
Bank Sta=4961,5031
XS Rating Curve= 0 ,0
Exp/Cntr=0.5,0.3

Type RM Length L Ch R = 1 ,20724.2 ,124,123,122
BEGIN DESCRIPTION:
Upstream Section of Bridge/Culvert/Weir;
ANTOINE - XS 3
Cross-section stops at highest point.  The ground elevation decreases down to unknown trib.  Spill
END DESCRIPTION:
XS GIS Cut Line= 6
      3083390.04     13896762.92      3083402.57     13894279.69
      3083398.87      13894204.6      3083400.68     13893982.74
      3083381.36     13893854.97      3082443.87     13892257.76
#Sta/Elev= 30
  2360.6  101.51  2420.6  101.41  2480.6   98.71  2960.6   98.31  3140.6  100.51
  3250.6   98.81  3400.6  101.51  3450.6  100.71  3490.6   98.01  3750.6   97.51
  3800.6   98.71  3900.6   97.51  4090.6   99.91  4280.6   98.71  4362.9   97.03
  4932.6    96.5  4948.8   94.94  4967.1   93.75  4980.3   87.24    5000   85.11
  5020.1   87.17  5033.9   93.68  5066.2   96.24  5579.5   96.55  5620.1   97.91
  6200.1   97.71  6300.1   95.51  6330.1   97.01  6740.1   97.91  7122.2   97.11
#Mann= 8 ,-1 , 0
  2360.6     .99       0  4280.6     .08       0  4362.9     .08       0
  4948.8     .05       0  4967.1     .04       0  5033.9     .08       0
  5579.5     .07       0  5620.1     .99       0
#XS Ineff= 2 , 0
       0  4953.5   96.48 5048.47       0   95.86
Permanent Ineff=
       F       F
Bank Sta=4967.1,5033.9
XS Rating Curve= 0 ,0
Exp/Cntr=0.5,0.3

Type RM Length L Ch R = 3 ,20662.5 ,,,
BEGIN DESCRIPTION:
ANTOINE
Structure ID: E121-00-00-15
END DESCRIPTION:
Bridge Culvert--1,0,-1,-1, 0
Deck Dist Width WeirC Skew NumUp NumDn MinLoCord MaxHiCord MaxSubmerge Is_Ogee
13,98,2.6,0, 59, 59, , , 0.95, 0, ,,,
  2360.6  2420.6  2450.6  2480.6  2949.9  2960.6  3000.6  3050.6  3140.6  3169.9
  3250.6  3300.6  3320.6  3400.6  3419.9  3450.6  3470.6  3480.6  3490.6  3500.6
  3529.9  3560.6  3750.6  3800.6  3840.6  3860.6  3900.6  3969.9  4060.6  4090.6
  4250.6  4280.6  4360.6  4362.9  4390.6  4420.6  4749.9  4763.3  4808.8  4844.3
    4890  4932.6  4950.7  4953.5  4953.6  5018.2  5040.8  5045.5  5049.4 5049.51
  5064.3  5066.2  5096.3  5129.1    5176  5208.8  5231.7  5270.1  5308.8
   101.5  101.41   99.31   98.94   98.32   98.41   99.61  100.01  100.51   100.5
   98.81  100.21  100.11  101.51   101.5  100.94  100.57  100.34   99.59   99.49
    99.2    99.5   98.71   98.71   98.34   98.41   98.09   98.07   98.81   99.91
   98.01   98.71   97.11   97.03   96.88   96.82   96.46   96.47   96.71    96.7
   96.77   96.81   96.81    96.5    99.6   99.98    99.7   99.64   99.59   96.49
   96.88   96.93   96.91    96.8   96.61    95.9   95.83   96.51   96.62
   101.5   101.4    99.3    98.7   98.31    98.3    99.6     100   100.5  100.05
    98.8   100.2   100.1   101.5  101.19   100.7    99.5    98.2      98    98.7
    98.8    98.9    97.5    98.7      98    98.4    97.5   98.06    98.8    99.9
      98    98.7    97.1   97.02      96    96.2   96.45   96.46   96.03    95.7
   96.17   96.49   94.75    94.5    94.5   94.88    94.6   94.68      95   95.01
   96.22   96.23   96.32   96.25   95.97   95.77   95.63    96.5   96.61
  2360.6  2420.6  2450.6  2480.6  2949.9  2960.6  3000.6  3050.6  3140.6  3169.9
  3250.6  3300.6  3320.6  3400.6  3419.9  3450.6  3470.6  3480.6  3490.6  3500.6
  3529.9  3560.6  3750.6  3800.6  3840.6  3860.6  3900.6  3969.9  4060.6  4090.6
  4250.6  4280.6  4360.6  4362.9  4390.6  4420.6  4749.9  4763.3  4808.8  4844.3
    4890  4932.6  4950.7  4953.5  4953.6  5018.2  5040.8  5045.5  5049.4 5049.51
  5064.3  5066.2  5096.3  5129.1    5176  5208.8  5231.7  5270.1  5308.8
   101.5  101.41   99.31   98.94   98.32   98.41   99.61  100.01  100.51   100.5
   98.81  100.21  100.11  101.51   101.5  100.94  100.57  100.34   99.59   99.49
    99.2    99.5   98.71   98.71   98.34   98.41   98.09   98.07   98.81   99.91
   98.01   98.71   97.11   97.03   96.88   96.82   96.46   96.47   96.71    96.7
   96.77   96.81   96.81    96.5    99.6   99.98    99.7   99.64   99.59   96.49
   96.88   96.93   96.91    96.8   96.61    95.9   95.83   96.51   96.62
   101.5   101.4    99.3    98.7   98.31    98.3    99.6     100   100.5  100.05
    98.8   100.2   100.1   101.5  101.19   100.7    99.5    98.2      98    98.7
    98.8    98.9    97.5    98.7      98    98.4    97.5   98.06    98.8    99.9
      98    98.7    97.1   97.02      96    96.2   96.45   96.46   96.03    95.7
   96.17   96.49   94.75    94.5    94.5   94.88    94.6   94.68      95   95.01
   96.22   96.23   96.32   96.25   95.97   95.77   95.63    96.5   96.61
Pier Skew, UpSta & Num, DnSta & Num=  ,4985.4, 2 ,4985.4, 2 , 0 , 0 , 0 ,,
     1.3     1.3
   85.86   95.69
     1.3     1.3
   86.44   96.27
Pier Skew, UpSta & Num, DnSta & Num=  ,5017.4, 2 ,5017.4, 2 , 0 , 0 , 0 ,,
     1.3     1.3
   85.58   95.88
     1.3     1.3
   86.16   96.46
Abutment Skew #Up #Dn= , 2 , 2
  4953.3  4980.4
    94.5   87.22
  4953.3  4980.4
   95.08    87.8
Abutment Skew #Up #Dn= , 2 , 2
  5020.2 5049.19
   87.21   94.97
  5020.2 5049.19
   87.79   95.55
BR Coef= 1 , 1 , 0 ,1.25, 0 ,,,0.8,0,2,0,
WSPro=,,,, 1 ,,,, 0 ,,,, 0 ,,,,-1 ,-1 ,-1 , 0 , 0 , 0 , 0 , 0
BR U #Sta/Elev= 134
  2360.6   101.5  2369.9  101.48  2389.9  101.45  2420.6   101.4  2439.9  100.05
  2450.6    99.3  2480.6    98.7  2949.9   98.31  2960.6    98.3  3000.6    99.6
  3050.6     100  3140.6   100.5  3169.9  100.05  3249.9   98.81  3250.6    98.8
  3299.9  100.18  3300.6   100.2  3319.9   100.1  3320.6   100.1  3329.9  100.26
  3339.9  100.44  3349.9  100.61  3400.6   101.5  3419.9  101.19  3450.6   100.7
  3470.6    99.5  3479.9   98.29  3480.6    98.2  3489.9   98.01  3490.6      98
  3500.6    98.7  3529.9    98.8  3559.9    98.9  3560.6    98.9  3750.6    97.5
  3800.6    98.7  3840.6      98  3860.6    98.4  3900.6    97.5  3969.9   98.06
  4060.6    98.8  4090.6    99.9  4250.6      98  4280.6    98.7  4360.6    97.1
  4362.9   97.02  4390.6      96  4420.6    96.2  4749.9   96.45  4763.3   96.46
  4808.8   96.03  4844.3    95.7  4858.7   95.85    4890   96.17    4902   96.26
  4932.6   96.49  4948.8   94.93  4950.7   94.75 4953.31    94.5 4953.39   94.49
  4953.5   94.48  4953.6   94.47 4953.71   94.46  4956.1   94.23  4967.1   93.74
  4980.3   87.23  4980.4   87.22  4992.3   86.47    4993   85.11    5000   85.11
    5007   85.13  5008.1   86.19  5017.4   86.61  5018.2   86.77  5020.1   87.16
  5020.2   87.21  5033.9   93.67  5040.8   94.24  5045.5   94.68 5048.99   94.97
 5049.19   94.98  5049.3   94.99  5049.4      95 5049.51   95.01  5064.3   96.22
  5066.2   96.23  5096.3   96.32  5109.2   96.29  5129.1   96.25  5151.6   96.11
    5176   95.97  5208.8   95.77  5231.7   95.63  5270.1    96.5  5308.8   96.61
  5518.8   97.19  5538.8   97.24  5548.8   97.27  5558.8    97.3  5560.1    97.3
  5568.8   97.13  5570.1    97.1  5579.5   96.54  5580.1    96.5  5588.8   97.02
  5598.8   97.62  5600.1    97.7  5620.1    97.9  5640.1      97  5688.8      97
  5870.1      97  6040.1    97.5  6178.8   97.67  6200.1    97.7  6208.8   97.51
  6218.8   97.29  6238.8   96.85  6268.8   96.19  6278.8   95.97  6288.8   95.75
  6300.1    95.5  6310.1    96.4  6320.1    96.9  6330.1      97  6338.8    96.7
  6350.1    96.3  6368.8   96.38  6488.8   96.87  6568.8    97.2  6740.1    97.9
  6840.1    97.2  6923.1   97.06  6960.1      97  7122.2    97.1
BR U #Mann= 8
  2360.6     .99  4280.6     .08  4362.9     .08  4948.8     .05  4967.1     .04
  5033.9     .08  5579.5     .07  5620.1     .99
BR U Banks=4967.1,5033.9
BR D #Sta/Elev= 136
  2360.6   101.5  2369.9  101.48  2389.9  101.45  2420.6   101.4  2439.9  100.05
  2450.6    99.3  2480.6    98.7  2949.9   98.31  2960.6    98.3  3000.6    99.6
  3050.6     100  3140.6   100.5  3169.9  100.05  3249.9   98.81  3250.6    98.8
  3299.9  100.18  3300.6   100.2  3319.9   100.1  3320.6   100.1  3329.9  100.26
  3339.9  100.44  3349.9  100.61  3400.6   101.5  3419.9  101.19  3450.6   100.7
  3470.6    99.5  3479.9   98.29  3480.6    98.2  3489.9   98.01  3490.6      98
  3500.6    98.7  3529.9    98.8  3559.9    98.9  3560.6    98.9  3750.6    97.5
  3800.6    98.7  3840.6      98  3860.6    98.4  3900.6    97.5  3969.9   98.06
  4060.6    98.8  4090.6    99.9  4250.6      98  4280.6    98.7  4360.6    97.1
  4362.9   97.02  4390.6      96  4420.6    96.2  4749.9   96.45  4763.3   96.46
  4808.8   96.03  4844.3    95.7  4858.7   95.85    4890   96.17    4902   96.26
  4932.6   96.49  4948.8   94.93  4950.7   94.75 4953.31    94.5 4953.39   94.49
  4953.5   94.48  4953.6   94.47 4953.71   94.46  4956.1   94.23  4967.1   94.32
  4980.3   87.81  4980.4    87.8  4992.3   87.05    4993   85.69  4995.2   84.75
  5000.7   84.59  5005.7   84.53    5007   85.71  5008.1   86.77  5017.4   87.19
  5018.2   87.35  5020.1   87.74  5020.2   87.79  5033.9   94.25  5040.8   94.24
  5045.5   94.68 5048.99   94.97 5049.19   94.98  5049.3   94.99  5049.4      95
 5049.51   95.01  5064.3   96.22  5066.2   96.23  5096.3   96.32  5109.2   96.29
  5129.1   96.25  5151.6   96.11    5176   95.97  5208.8   95.77  5231.7   95.63
  5270.1    96.5  5308.8   96.61  5518.8   97.19  5538.8   97.24  5548.8   97.27
  5558.8    97.3  5560.1    97.3  5568.8   97.13  5570.1    97.1  5579.5   96.54
  5580.1    96.5  5588.8   97.02  5598.8   97.62  5600.1    97.7  5620.1    97.9
  5640.1      97  5688.8      97  5870.1      97  6040.1    97.5  6178.8   97.67
  6200.1    97.7  6208.8   97.51  6218.8   97.29  6238.8   96.85  6268.8   96.19
  6278.8   95.97  6288.8   95.75  6300.1    95.5  6310.1    96.4  6320.1    96.9
  6330.1      97  6338.8    96.7  6350.1    96.3  6368.8   96.38  6488.8   96.87
  6568.8    97.2  6740.1    97.9  6840.1    97.2  6923.1   97.06  6960.1      97
  7122.2    97.1
BR D #Mann= 8
  2360.6     .99  4280.6     .08  4362.9     .08  4948.8     .05  4967.1     .04
  5033.9     .08  5579.5     .07  5620.1     .99
BR D Banks=4967.1,5033.9
BC Design=,, 0 ,, 0 ,,,,,,
BC HTab HWMax=101.51
BC Use User HTab Curves=0
BC User HTab FreeFlow(D)= 0

Type RM Length L Ch R = 1 ,20600.8 ,144,194,385
BEGIN DESCRIPTION:
Downstream Section of Bridge/Culvert/Weir
ANTOINE - XS 2
Cross-section stops at highest point.  The ground elevation decreases down to unknown trib.  Spill
END DESCRIPTION:
XS GIS Cut Line= 6
      3083508.21     13896728.61      3083520.74     13894245.24
      3083517.04     13894170.14      3083518.86     13893948.06
      3083499.32     13893818.93      3082561.35     13892220.89
#Sta/Elev= 30
  2360.6  101.51  2420.6  101.41  2480.6   98.71  2960.6   98.31  3140.6  100.51
  3250.6   98.81  3400.6  101.51  3450.6  100.71  3490.6   98.01  3900.6   97.51
  4090.6   99.91  4280.6   98.71  4362.9   97.03  4932.6    96.5  4948.8   94.94
  4967.1   94.29  4980.3   87.78  4995.2   84.72  5005.7    84.5  5008.1   86.74
  5020.1   87.71  5033.9   94.22  5066.2   96.24  5579.5   96.55  5620.1   97.91
  6200.1   97.71  6300.1   95.51  6330.1   97.01  6740.1   97.91  7122.2   97.11
#Mann= 8 ,-1 , 0
  2360.6     .99       0  4280.6     .08       0  4362.9     .08       0
  4948.8     .05       0  4967.1     .04       0  5033.9     .08       0
  5579.5     .07       0  5620.1     .99       0
#XS Ineff= 2 , 0
       0  4953.5   96.48 5048.47       0   95.86
Permanent Ineff=
       F       F
Bank Sta=4967.1,5033.9
XS Rating Curve= 0 ,0
Exp/Cntr=0.5,0.3

Type RM Length L Ch R = 1 ,20407   ,676,665,528
BEGIN DESCRIPTION:
Interpolated Channel - LIDAR overbanks
ANTOINE - XS 1
Cross-section stops at highest point.  The ground elevation decreases down to unknown trib.  Spill
END DESCRIPTION:
XS GIS Cut Line= 4
      3083643.36     13896717.87      3083659.52     13894368.69
      3083743.95     13893898.78      3082646.29     13892210.07
#Sta/Elev= 30
  2388.4   99.11  3428.4   97.85  3458.4   96.61  3498.4  100.41  3568.4  101.04
  3608.4  100.07  3648.4      97  3738.4   99.07  3818.4   97.84  4088.4   99.23
  4398.4   96.13  4578.4   97.36  4887.6   94.19  4937.6   96.61 4970.98   94.07
 4982.42   87.78 4992.82   86.23 4995.34   84.35 5004.44   83.83 5006.96   85.64
 5019.61   87.76  5027.6   90.75  5047.6   93.99  5555.1   97.07  5595.1    95.5
  6265.1   97.24  6305.1   95.58  6345.1   97.13  6385.1   95.96  7229.2   96.27
#Mann= 5 ,-1 , 0
  2388.4     .99       0  4398.4     .12       0 4970.98     .04       0
  5047.6     .08       0  5595.1     .99       0
Bank Sta=4970.98,5047.6
XS Rating Curve= 0 ,0
Exp/Cntr=0.3,0.1

Type RM Length L Ch R = 1 ,19742.6 ,1005,711,585
BEGIN DESCRIPTION:
Cross Section X13
END DESCRIPTION:
XS GIS Cut Line= 5
      3084487.81     13894975.86      3084319.42     13894458.22
      3084346.27     13894267.51      3084363.08     13894152.62
      3083115.75     13892793.03
#Sta/Elev= 30
  4260.9    98.5  4298.8   97.74  4330.9    94.9  4481.1   95.41  4954.2   95.12
  4984.3   93.32  4984.4   89.99  4992.9   86.44 4993.01   84.63    4994   83.76
  5000.1   81.54    5004      82  5014.6   87.05    5035   92.55  5118.2   93.96
  5133.9    95.7  5213.9    94.4  5273.9    96.1  5373.9    95.5  5463.9    97.1
  5493.9      96  5643.9    95.7  5863.9    95.9  5903.9    97.1  6133.9      96
  6353.9    97.5  6393.9    96.3  6683.9    96.8  6703.9    95.7    6959    96.5
#Mann= 7 ,-1 , 0
  4260.9     .08       0  4298.8     .05       0  4481.1     .12       0
  4954.2     .05       0  4984.3     .04       0    5035     .12       0
  5463.9     .99       0
#XS Ineff= 2 , 0
       0  4640.9    96.2               0
Permanent Ineff=
       F       F
Bank Sta=4984.3,5035
XS Rating Curve= 0 ,0
Exp/Cntr=0.3,0.1