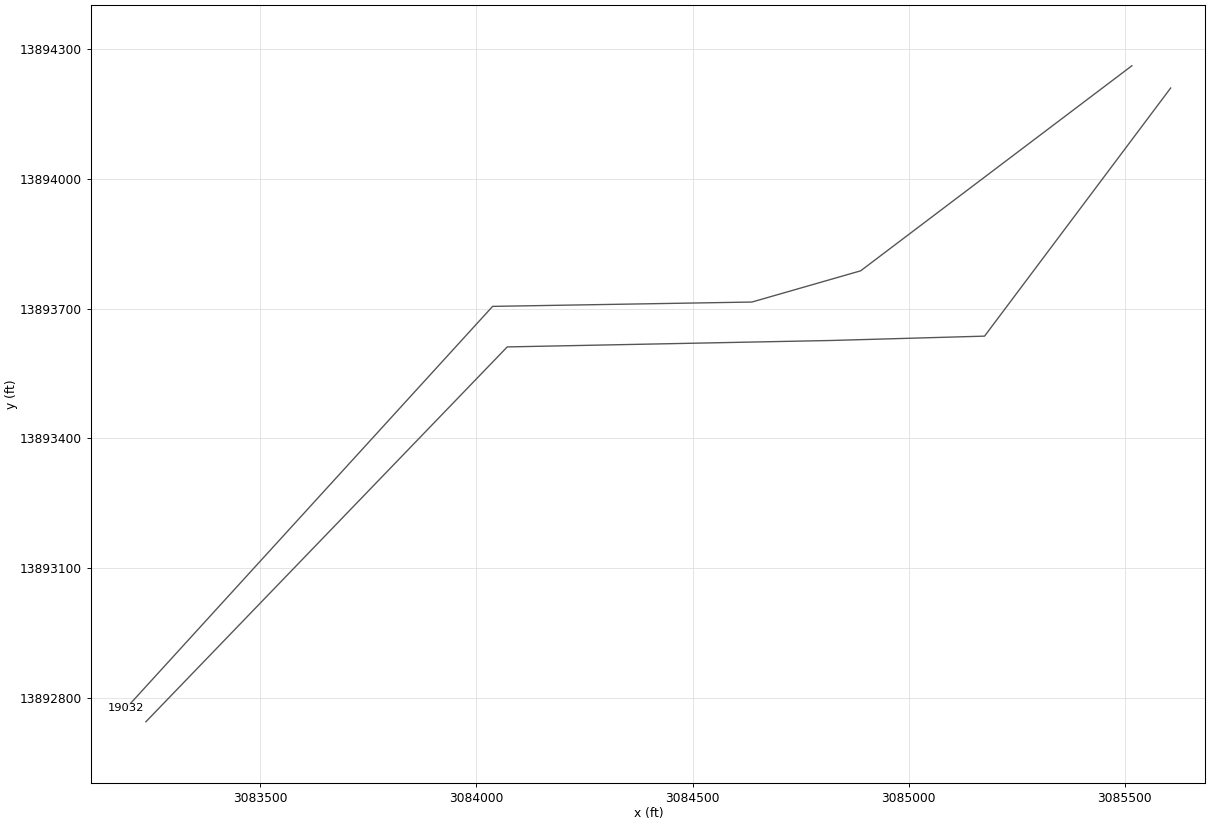
HEC-RAS study E121-00-00.prj: E121-00-00 LOMR

--- E121-00-00.g01 (geometry) --- (continued)

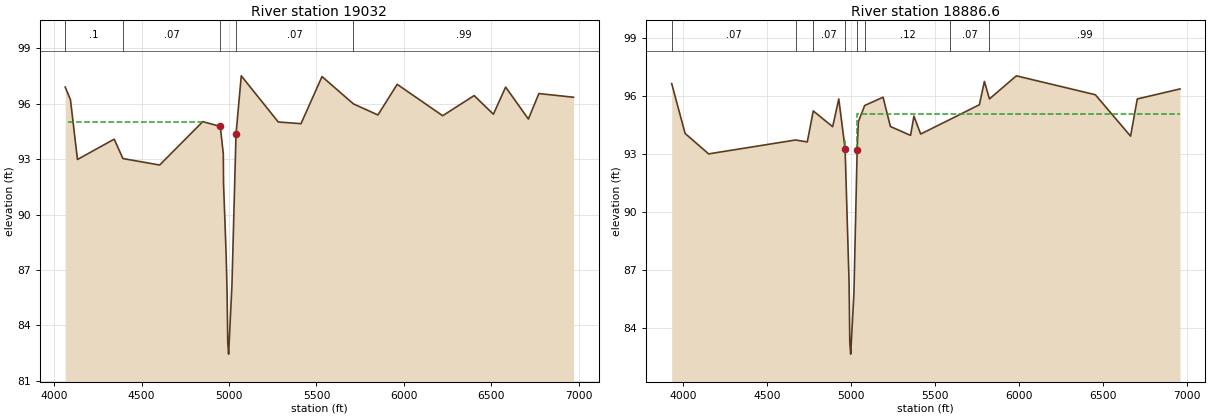
Type RM Length L Ch R = 1 ,19032   ,252,145,112
BEGIN DESCRIPTION:
Interpolated Channel - LIDAR overbanks
CHIPPEWA - XS 4
END DESCRIPTION:
XS GIS Cut Line= 5
      3085516.09      13894261.6      3084888.83     13893787.37
      3084637.38     13893715.19      3084037.71     13893705.16
      3083190.03     13892775.62
#Sta/Elev= 30
  4063.8    96.9  4093.8   96.22  4133.8   92.98  4343.8   94.08  4393.8   93.03
  4603.8   92.68  4850.2   95.03  4950.2   94.77 4967.53   93.29 4968.93   91.67
 4984.02   87.78 4989.17   85.79 4993.05   83.07 4997.83   82.44 5016.84   86.15
  5040.2   94.35  5070.2   97.51  5281.8   95.01  5411.8   94.92  5531.8   97.47
  5711.5   95.99  5851.5   95.39  5961.5   97.05  6221.5   95.35  6401.5   96.44
  6511.5   95.43  6581.5    96.9  6711.5   95.17  6771.5   96.55  6969.6   96.35
#Mann= 5 ,-1 , 0
  4063.8      .1       0  4393.8     .07       0  4950.2     .06       0
  5040.2     .07       0  5711.5     .99       0
#XS Ineff= 1 ,-1
 4080.44 4849.06   95.03
Permanent Ineff=
       F
Bank Sta=4950.2,5040.2
XS Rating Curve= 0 ,0
Exp/Cntr=0.5,0.3

Type RM Length L Ch R = 1 ,18886.6 ,82,83,84
BEGIN DESCRIPTION:
Upstream Section of Bridge/Culvert/Weir
CHIPPEWA - XS 3
END DESCRIPTION:
XS GIS Cut Line= 5
      3085605.78     13894210.12      3085175.45     13893636.35
      3084820.91      13893626.3      3084071.56     13893611.41
      3083235.85     13892744.51
#Sta/Elev= 30
  3931.9   96.66  4011.9   94.07  4151.9   93.01  4669.1   93.73  4739.1   93.63
  4774.6   95.24 4889.98   94.42  4926.5   95.86 4964.11   93.28 4987.86   86.33
 4992.12   83.22 4997.37   82.62 5016.68    85.8 5035.88   93.22 5043.05   94.68
 5080.66   95.52 5190.14   95.95  5233.8   94.43  5353.8   93.97  5373.8   94.97
  5413.8   94.04 5589.37    94.8  5763.3   95.56  5793.3   96.77  5823.3   95.86
  5983.3   97.06  6453.3   96.08  6663.3   93.93  6703.3   95.86  6957.4   96.38
#Mann= 8 ,-1 , 0
  3931.9     .07       0  4669.1     .05       0  4774.6     .07       0
 4964.11     .06       0 5035.88     .04       0 5080.66     .12       0
 5589.37     .07       0  5823.3     .99       0
#XS Ineff= 3 ,-1
 3949.22 4926.48   95.48 4957.96 4964.22    93.7 5035.88  6957.4    95.1
Permanent Ineff=
       F       F       F
Bank Sta=4964.11,5035.88
XS Rating Curve= 0 ,0
Skew Angle= 25
Exp/Cntr=0.5,0.3