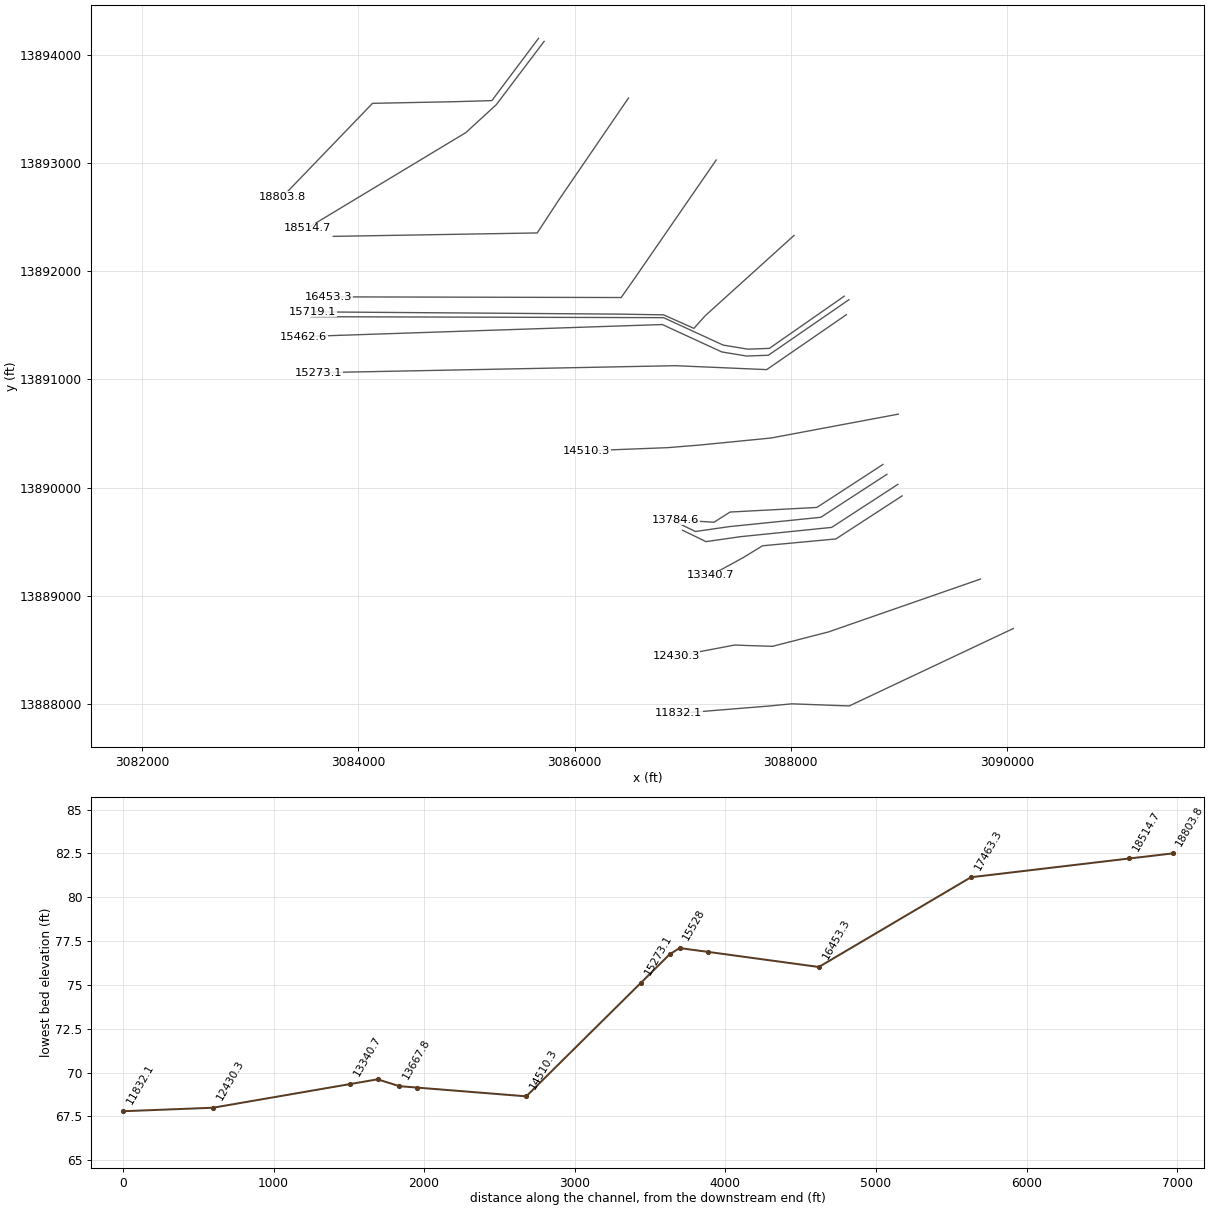
HEC-RAS study E121-00-00.prj: E121-00-00 LOMR

--- E121-00-00.g01 (geometry) --- (continued)

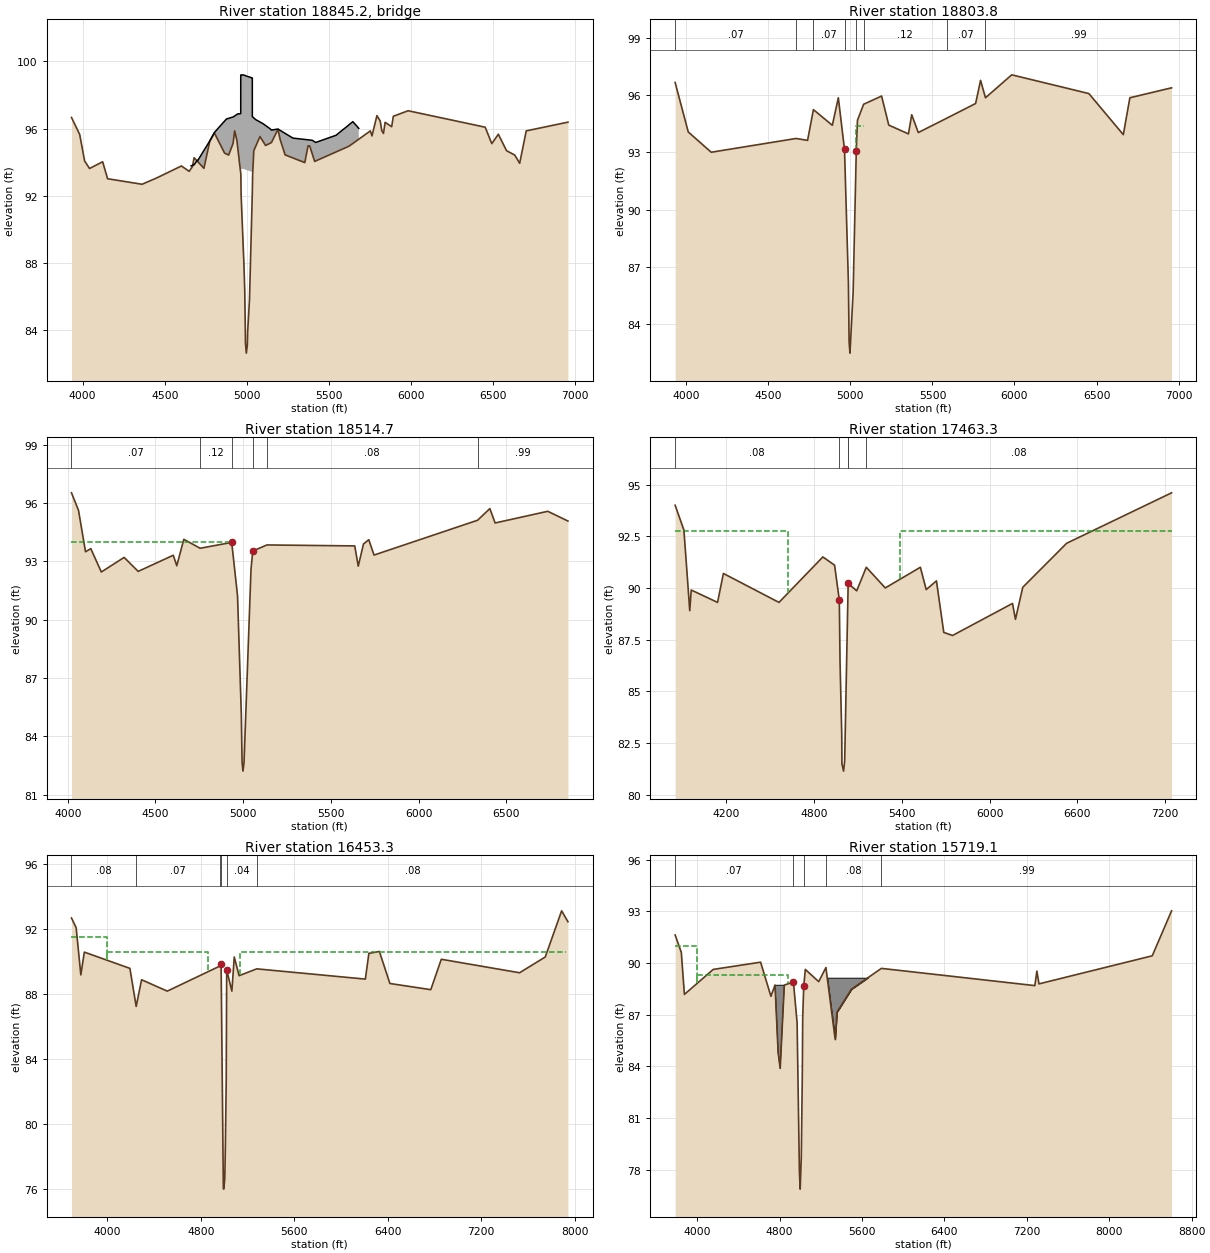
Type RM Length L Ch R = 3 ,18845.2 ,,,
BEGIN DESCRIPTION:
CHIPPEWA; skewed
Structure ID: E121-00-00-14
END DESCRIPTION:
Bridge Culvert--1,0,-1,-1, 0
Deck Dist Width WeirC Skew NumUp NumDn MinLoCord MaxHiCord MaxSubmerge Is_Ogee
11,61,2.6,25, 62, 62, 95.03, , 0.95, 0, ,,,
4661.311 4671.46 4679.44 4697.57 4699.654701.641  4774.6  4802.74837.771 4864.69
4876.561 4889.98 4916.624916.7994926.501 4940.28 4944.26  4956.54963.291 4963.39
 4963.49 4964.11 4964.21 4964.29 4965.654977.521 4982.694987.861 4991.48 4992.12
 4997.37 5003.63 5005.175006.441 5016.68 5033.62 5033.895033.991 5034.09 5035.88
5035.971 5036.07 5043.05 5055.01 5080.66 5100.69 5114.92 5141.75  5150.9 5190.14
 5254.49 5281.68  5399.5 5419.89 5544.515589.371 5589.83 5607.95 5635.14 5646.47
5671.391 5682.72
   93.78   93.81   93.84    94.1    94.1    94.1   95.26   95.76   96.15   96.44
   96.57   96.61   96.69   96.69   96.75   96.84   96.87   96.88   96.89   99.19
   99.19   99.19   99.19   99.19   99.19    99.2   99.18   99.17   99.15   99.15
   99.13   99.11   99.11    99.1   99.07   99.01   99.01   99.01   96.71   96.69
   96.69   96.69   96.63   96.53   96.39   96.28   96.18   95.99   95.91   95.97
   95.59   95.43    95.3   95.17    95.6   95.96   95.96    96.1   96.32   96.41
   96.14   96.01
                                                                                
                                                                   93.36   93.35
   93.34   93.29   93.21   93.59   93.59    93.6   93.58   93.57   93.55   93.55
   93.53   93.51   93.51    93.5   93.47   93.41   93.41   93.41   93.41   93.39
   93.39   93.27   94.69
                                                                                
                
4661.311 4671.46 4679.44 4697.57 4699.654701.641  4774.6  4802.74837.771 4864.69
4876.561 4889.98 4916.624916.7994926.501 4940.28 4944.26  4956.54963.291 4963.39
 4963.49 4964.11 4964.21 4964.29 4965.654977.521 4982.694987.861 4991.48 4992.12
 4997.37 5003.63 5005.175006.441 5016.68 5033.62 5033.895033.991 5034.09 5035.88
5035.971 5036.07 5043.05 5055.01 5080.66 5100.69 5114.92 5141.75  5150.9 5190.14
 5254.49 5281.68  5399.5 5419.89 5544.515589.371 5589.83 5607.95 5635.14 5646.47
5671.391 5682.72
   93.78   93.81   93.84    94.1    94.1    94.1   95.26   95.76   96.15   96.44
   96.57   96.61   96.69   96.69   96.75   96.84   96.87   96.88   96.89   99.19
   99.19   99.19   99.19   99.19   99.19    99.2   99.18   99.17   99.15   99.15
   99.13   99.11   99.11    99.1   99.07   99.01   99.01   99.01   96.71   96.69
   96.69   96.69   96.63   96.53   96.39   96.28   96.18   95.99   95.91   95.97
   95.59   95.43    95.3   95.17    95.6   95.96   95.96    96.1   96.32   96.41
   96.14   96.01
                                                                                
                                                                   93.36   93.35
   93.34   93.29   93.21   93.59   93.59    93.6   93.58   93.57   93.55   93.55
   93.53   93.51   93.51    93.5   93.47   93.41   93.41   93.41   93.41   93.39
   93.39   93.27
                                                                                
                
BR Coef= 1 , 1 , 0 ,1.25, 0 ,,,0.8,-1,2,0,
WSPro=,,,, 1 ,,,, 0 ,,,, 0 ,,,,-1 ,-1 ,-1 , 0 , 0 , 0 , 0 , 0
BR U #Sta/Elev= 84
3931.901   96.663981.901   95.65  4011.9   94.07  4041.9   93.62  4121.9   94.02
  4151.9   93.01  4361.9   92.68  4451.9   93.06  4601.9   93.77  4649.1   93.45
4669.101   93.734679.101   94.264739.101   93.63  4774.6   95.24  4802.7   95.74
4837.771   95.06 4864.69   94.544876.561   94.48 4889.98   94.42 4916.62   95.11
4916.799   95.124926.501   95.86 4940.28   95.27 4944.26   94.93  4956.5   93.89
4963.291   93.35 4963.38   93.34 4963.49   93.33 4964.11   93.28 4964.21    93.2
 4964.29   93.14 4965.65   92.074977.521   89.19 4982.69   87.944987.861   86.33
 4991.48   83.83 4992.12   83.22 4997.37   82.62 5003.63    83.1 5005.17   83.79
5006.441   84.06 5016.68    85.8 5033.62   92.08 5033.89   92.215033.991   92.26
 5034.09   92.31 5035.88   93.225035.971   93.24 5036.07   93.26 5043.05   94.68
 5055.01   94.95 5080.66   95.52 5100.69   95.21 5114.92   94.99 5141.75   95.12
  5150.9   95.17 5190.14   95.95  5203.8   95.34  5233.8   94.435353.801   93.97
  5373.8   94.97  5383.8   94.96  5413.8   94.045589.371    94.8  5623.8   94.95
 5646.47   95.11  5753.3   95.86  5763.3   95.56  5793.3   96.77  5813.3   96.45
5823.299   95.86  5833.3   95.71  5843.3   96.37  5883.3   96.11  5893.3   96.73
  5983.3   97.066453.301   96.08  6493.3    95.1  6533.3   95.66  6583.3   94.68
  6633.3   94.42  6663.3   93.93  6703.3   95.86  6957.4   96.38
BR U #Mann= 8
3931.901     .074669.101     .05  4774.6     .07 4964.11     .06 5035.88     .04
 5080.66     .125589.371     .075823.299     .99
BR D #Sta/Elev= 84
3931.901   96.663981.901   95.65  4011.9   94.07  4041.9   93.62  4121.9   94.02
  4151.9   93.01  4361.9   92.68  4451.9   93.06  4601.9   93.77  4649.1   93.45
4669.101   93.734679.101   94.264739.101   93.63  4774.6   95.24  4802.7   95.74
4837.771   95.06 4864.69   94.544876.561   94.48 4889.98   94.42 4916.62   95.11
4916.799   95.124926.501   95.86 4940.28   95.27 4944.26   94.93  4956.5   93.89
4963.291   93.35 4963.38   93.34 4963.49   93.33 4964.11   93.05 4964.21   92.97
 4964.29   92.91 4965.65   91.844977.521   88.96 4982.69   87.714987.861    86.1
 4991.48    83.6 4992.12   82.99 4997.37   82.39 5003.63   82.87 5005.17   83.56
5006.441   83.83 5016.68   85.57 5033.62   91.85 5033.89   91.985033.991   92.03
 5034.09   92.08 5035.88   92.995035.971   93.01 5036.07   93.03 5043.05   94.68
 5055.01   94.95 5080.66   95.52 5100.69   95.21 5114.92   94.99 5141.75   95.12
  5150.9   95.17 5190.14   95.95  5203.8   95.34  5233.8   94.435353.801   93.97
  5373.8   94.97  5383.8   94.96  5413.8   94.045589.371    94.8  5623.8   94.95
 5646.47   95.11  5753.3   95.86  5763.3   95.56  5793.3   96.77  5813.3   96.45
5823.299   95.86  5833.3   95.71  5843.3   96.37  5883.3   96.11  5893.3   96.73
  5983.3   97.066453.301   96.08  6493.3    95.1  6533.3   95.66  6583.3   94.68
  6633.3   94.42  6663.3   93.93  6703.3   95.86  6957.4   96.38
BR D #Mann= 8
3931.901     .074669.101     .05  4774.6     .07 4964.11     .06 5035.88     .04
 5080.66     .125589.371     .075823.299     .99
BC Design=,, 0 ,, 0 ,,,,,,
BC HTab HWMax=96.89
BC Use User HTab Curves=0
BC User HTab FreeFlow(D)= 0

Type RM Length L Ch R = 1 ,18803.8 ,57,289,371
BEGIN DESCRIPTION:
Downstream Section of Bridge/Culvert/Weir
CHIPPEWA - XS 2
END DESCRIPTION:
XS GIS Cut Line= 5
      3085666.69     13894152.92      3085234.91     13893577.22
      3084877.94      13893567.1      3084130.64     13893552.25
      3083296.36     13892686.84
#Sta/Elev= 30
  3931.9   96.66  4011.9   94.07  4151.9   93.01  4669.1   93.73  4739.1   93.63
  4774.6   95.24 4889.98   94.42  4926.5   95.86 4964.11   93.16 4987.86   86.21
 4992.12    83.1 4997.37    82.5 5016.68   85.68 5035.88    93.1 5043.05   94.68
 5080.66   95.52 5190.14   95.95  5233.8   94.43  5353.8   93.97  5373.8   94.97
  5413.8   94.04 5589.37    94.8  5763.3   95.56  5793.3   96.77  5823.3   95.86
  5983.3   97.06  6453.3   96.08  6663.3   93.93  6703.3   95.86  6957.4   96.38
#Mann= 8 ,-1 , 0
  3931.9     .07       0  4669.1     .05       0  4774.6     .07       0
 4964.11     .06       0 5035.88     .04       0 5080.66     .12       0
 5589.37     .07       0  5823.3     .99       0
#XS Ineff= 4 ,-1
 3988.89 4943.86    94.4 4963.77 4964.11    93.2 5035.88    5081    94.4
    5081  6957.4    95.5
Permanent Ineff=
       F       F       F       F
Bank Sta=4964.11,5035.88
XS Rating Curve= 0 ,0
Skew Angle= 25
Exp/Cntr=0.5,0.3

Type RM Length L Ch R = 1 ,18514.7 ,985,1051,1270
BEGIN DESCRIPTION:
Interpolated Channel - LIDAR overbanks
CHIPPEWA - XS 1
END DESCRIPTION:
XS GIS Cut Line= 4
      3085718.52     13894124.77      3085276.27     13893540.23
      3084995.53     13893282.57      3083526.48     13892398.06
#Sta/Elev= 30
  4021.3   96.52  4061.3   95.62  4101.3   93.49  4131.3   93.65  4191.3   92.45
  4321.3    93.2  4401.3   92.48  4601.3   93.31  4621.3   92.77  4661.3   94.13
  4754.3   93.67  4934.3   93.97 4967.48   91.22 4989.09   85.13 4993.24   82.68
 4998.35   82.21 5004.36   82.63  5044.3   92.59  5054.3   93.53  5135.3   93.84
  5635.3   93.79  5655.3   92.75  5685.3   93.89  5715.3   94.11  5745.3   93.32
  6335.3   95.11  6405.3   95.71  6435.3   94.97  6735.3   95.57  6850.1   95.07
#Mann= 6 ,-1 , 0
  4021.3     .07       0  4754.3     .12       0  4934.3     .06       0
  5054.3     .12       0  5135.3     .08       0  6335.3     .99       0
#XS Ineff= 2 , 0
       0 4935.68   93.97 5136.56       0   93.83
Permanent Ineff=
       F       F
Bank Sta=4934.3,5054.3
XS Rating Curve= 0 ,0
Exp/Cntr=0.3,0.1

Type RM Length L Ch R = 1 ,17463.3 ,1010,1010,978
BEGIN DESCRIPTION:
Cross Section X12
Ineffective flow boundaries per FP constriction upstream
END DESCRIPTION:
XS GIS Cut Line= 4
      3086499.38     13893601.61      3085851.74     13892655.25
      3085654.77     13892354.28      3083767.76     13892322.65
#Sta/Elev= 30
  3850.4      94  3910.4    92.8  3950.4    88.9  3960.4    89.9  4140.4    89.3
  4180.4    90.7  4560.4    89.3  4860.4    91.5  4940.4    91.1  4972.8   89.41
  4977.5   86.49  4989.3   82.93  4990.6   81.49  5001.9   81.14  5009.4   81.64
  5033.3   90.23  5035.2   90.21  5091.7   89.86  5157.1      91  5287.1      90
  5526.8      91  5566.8   89.92  5636.8   90.34  5686.8   87.85  5746.8    87.7
  6156.8   89.25  6176.8   88.48  6226.8   90.03  6526.8   92.16  7244.1    94.6
#Mann= 5 ,-1 , 0
  3850.4     .08       0  4972.8     .06       0  5033.3     .04       0
  5035.2     .05       0  5157.1     .08       0
#XS Ineff= 2 , 0
       0  4620.3   92.75  5385.8       0   92.75
Permanent Ineff=
       F       F
Bank Sta=4972.8,5033.3
XS Rating Curve= 0 ,0
Exp/Cntr=0.3,0.1

Type RM Length L Ch R = 1 ,16453.3 ,800,735,146
BEGIN DESCRIPTION:
Cross Section X11
Ineffective flow boundaries per FP constriction upstream
END DESCRIPTION:
XS GIS Cut Line= 4
      3087310.84     13893028.38      3086567.83     13891951.73
      3086431.54     13891757.34       3083727.5     13891763.55
#Sta/Elev= 30
  3693.2    92.7  3733.2    92.1  3773.2    89.2  3803.2    90.6  4193.2    89.6
    4247   87.26  4293.2    88.9  4513.2    88.2  4965.8   89.75    4974   89.84
  4993.2   76.05  4996.8   76.02  5005.6    76.7  5010.4   78.63  5017.8   82.75
  5021.7    89.5  5066.1    88.2  5086.5    90.3    5128   89.15  5278.8   89.57
  6208.8   88.94  6238.8   90.52  6328.8   90.64  6418.8   88.67  6768.8   88.29
  6858.8   90.16  7528.8   89.33  7748.8    90.3  7888.8   93.14  7942.8   92.47
#Mann= 6 ,-1 , 0
  3693.2     .08       0    4247     .07       0  4965.8     .04       0
    4974     .06       0  5021.7     .04       0  5278.8     .08       0
#XS Ineff= 3 ,-1
  3693.2    4000    91.5    4000    4860    90.6    5135    7925    90.6
Permanent Ineff=
       F       F       F
Bank Sta=4974,5021.7
XS Rating Curve= 0 ,0
Exp/Cntr=0.3,0.1

Type RM Length L Ch R = 1 ,15719.1 ,427,190,81
BEGIN DESCRIPTION:
Interpolated Channel - LIDAR overbanks
BREEN - XS 4
END DESCRIPTION:
XS GIS Cut Line= 6
      3088030.91     13892331.29      3087208.22     13891588.22
      3087104.77     13891472.23      3086823.82     13891597.28
      3086432.92     13891603.77      3083575.43     13891624.89
#Sta/Elev= 30
  3784.9   91.63  3844.9   90.62  3874.9   88.18  4154.9   89.63  4614.9   90.05
  4714.9   88.07  4754.9   88.72  4784.9   84.82  4804.9   83.89  4844.9   88.72
  4933.5    88.9 4969.26   86.53 4991.44   77.92 4998.87   76.88  5009.6   78.68
 5019.54   83.43  5023.5   86.84  5033.5   88.65  5048.9   89.63  5178.9   88.92
  5248.9   89.74  5338.9   85.57  5356.4   87.15  5496.4   88.48  5787.4   89.69
  7277.4   88.69  7297.4   89.53  7317.4   88.79  8417.4   90.42    8605   93.03
#Mann= 5 ,-1 , 0
  3784.9     .07       0  4933.5    .045       0  5033.5     .07       0
  5248.9     .08       0  5787.4     .99       0
#XS Ineff= 2 ,-1
  3784.9    4000      91    4000    4885    89.3
Permanent Ineff=
       F       F
#Block Obstruct= 2 ,-1
 4749.78 4866.08   88.71  5246.7 5711.89   89.15
Bank Sta=4933.5,5033.5
XS Rating Curve= 0 ,0
Exp/Cntr=0.5,0.3

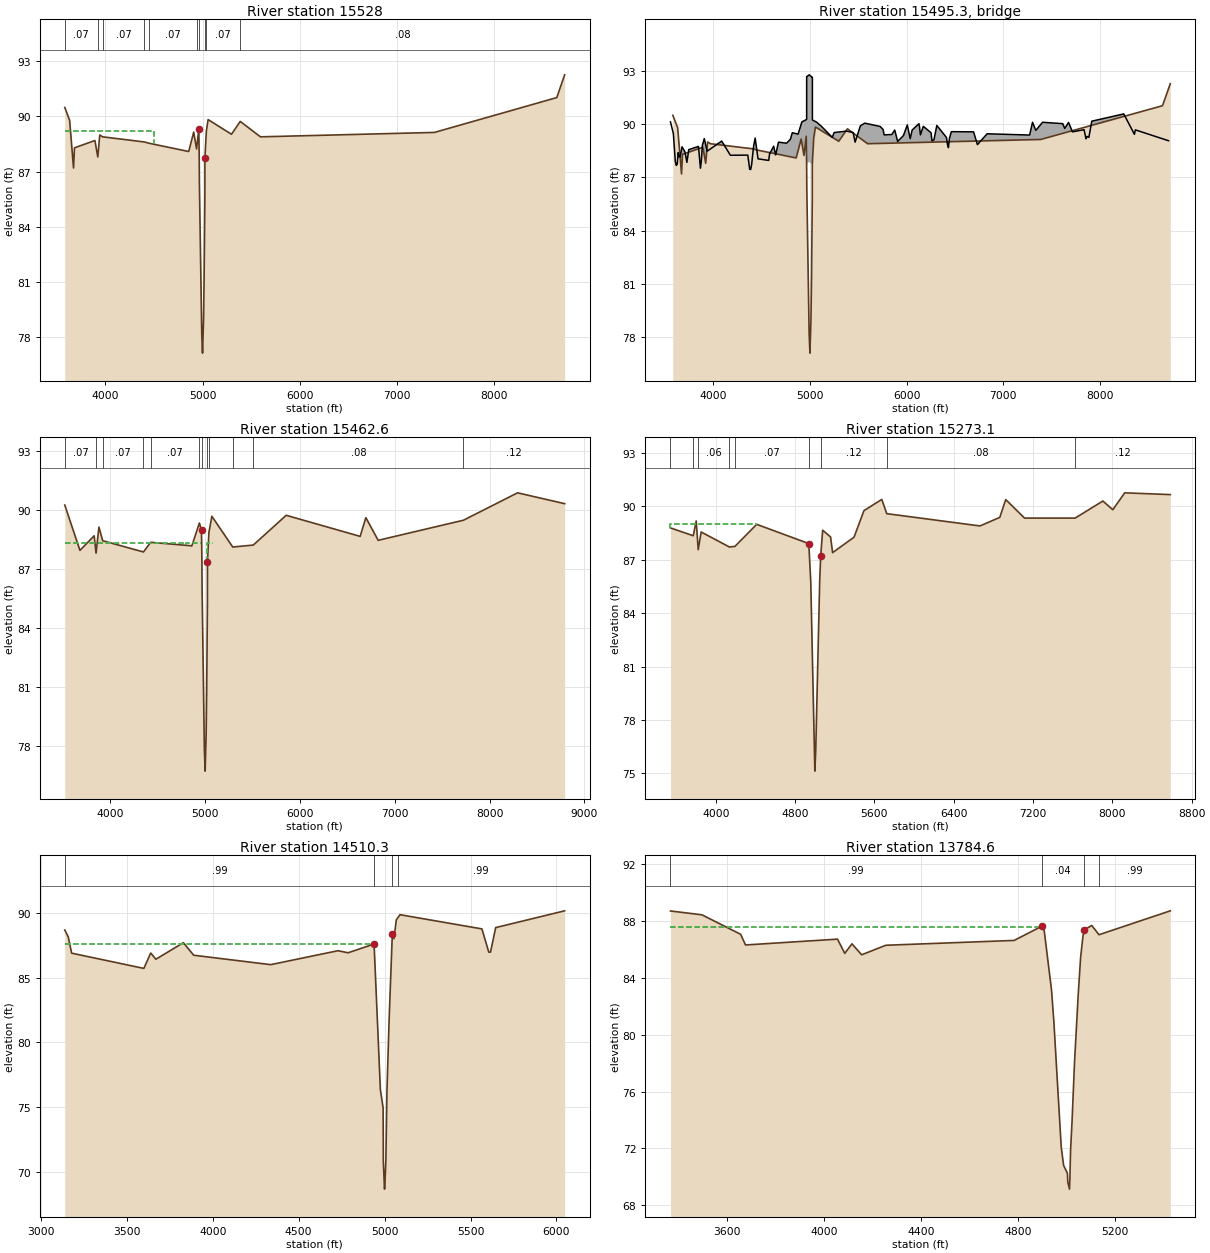
Type RM Length L Ch R = 1 ,15528   ,67,66,65
BEGIN DESCRIPTION:
Upstream Section of Bridge/Culvert/Weir;
BREEN - XS 3
Left overbank has a ditch near road that eventually spills to this creek.  The levee is not a FEMA certified flood control levee.  Expansion and contraction coefficients changed to 0.1 and 0.3 because channel underneath bridge structure is same size as channel upstream and downstream, there are no bridge piers, and no bridge abutments. - JJA 5/26/03
END DESCRIPTION:
XS GIS Cut Line= 6
      3088495.85     13891769.88      3087802.73     13891287.39
      3087602.73     13891280.19       3087374.5     13891317.88
      3086823.82     13891571.24      3083562.01     13891580.17
#Sta/Elev= 30
  3581.2   90.49  3631.2   89.79  3671.2   87.19  3681.2   88.29  3891.2   88.69
  3921.2   87.79  3941.2   88.99  3971.2   88.89  4401.1   88.61  4448.7   88.54
  4857.3   88.09  4908.6   89.15  4938.2   88.23    4961   89.31  4965.3   87.76
  4967.1   86.39  4991.3   78.17  4999.4    77.1  5010.1   78.97    5016   81.35
  5023.8   85.78 5023.89   87.72  5038.8    89.2  5056.8   89.83  5297.6   89.03
  5387.6   89.73  5595.7   88.89  7386.7   89.13  8646.7   91.03  8727.6   92.27
#Mann= 10 ,-1 , 0
  3581.2     .07       0  3921.2     .04       0  3971.2     .07       0
  4401.1     .08       0  4448.7     .07       0  4938.2     .04       0
  4965.3    .045       0 5023.89     .04       0  5038.8     .07       0
  5387.6     .08       0
#XS Ineff= 4 ,-1
    3519    4500    89.2    4500  4955.5    88.3 5023.89    5075   87.42
    5075  8791.1    89.2
Permanent Ineff=
       F       F       F       F
Bank Sta=4961,5023.89
XS Rating Curve= 0 ,0
Exp/Cntr=0.5,0.3

Type RM Length L Ch R = 3 ,15495.3 ,,,
BEGIN DESCRIPTION:
BREEN
Structure ID: E121-00-00-13
END DESCRIPTION:
Bridge Culvert--1,0,-1,-1, 0
Deck Dist Width WeirC Skew NumUp NumDn MinLoCord MaxHiCord MaxSubmerge Is_Ogee
12,41,2.6,0, 124, 124, , , 0.95, 0, ,,,
  3556.5  3586.5  3606.5  3616.5  3626.5  3636.5  3646.5  3656.5  3676.5  3706.5
  3726.5  3746.5  3846.5  3866.5  3876.5  3886.5  3906.5  3936.5  4086.5  4176.5
  4356.5  4376.5  4386.5  4396.5  4416.5  4432.8  4462.8  4572.8  4582.8  4584.5
  4624.5  4644.5  4674.5  4757.2  4797.2  4817.2    4877    4916  4922.3  4938.2
  4939.2  4959.1 4959.21  4959.3    4961  4965.3  4965.4 4965.49  4965.6 4965.71
  4967.1  4984.3  4989.9  4991.3  4991.8  4999.4  5007.6  5010.1    5016    5020
  5023.7  5023.8 5023.89 5023.99  5024.1 5024.89    5025 5025.11  5034.3  5038.8
  5056.8  5069.7  5096.7  5114.7  5230.2  5250.2  5376.5  5446.5  5466.5  5521.7
    5567  5726.8  5756.8  5766.8  5846.8  5876.8  5906.8  5966.8  6006.8  6036.8
  6056.8  6126.8  6132.3  6142.3  6172.3  6252.3  6262.3  6282.3  6312.3  6412.3
  6422.3  6432.3  6442.3  6462.3  6692.3  6732.3  6832.3  7272.3  7302.3  7336.1
  7406.1  7615.2  7635.2  7675.2  7715.2  7835.2  7855.2  7865.2  7885.2  7915.2
  8246.1  8356.1  8366.1  8708.7
   90.12   89.47   87.91   87.67   87.74   88.39   88.15   88.16   88.72   88.43
   87.84   88.56   88.74   87.51   87.94    88.8   89.18   88.47   89.04   88.24
   88.25   87.45   87.44   87.72   88.75   89.21   88.04   87.95   88.34   88.34
   88.75   88.26   88.98   88.92   89.14   89.51   89.43   90.12   90.14   90.18
   90.18   90.24   90.24   90.24   90.25   90.26   90.26   90.26   92.66   92.66
   92.67   92.74   92.76   92.77   92.77   92.73    92.7   92.69   92.66   92.64
   92.63   92.63   92.63   92.63   92.63   92.63   92.63   90.23    90.2   90.19
   90.14    90.1   89.97   89.89   89.25   89.52    89.6   89.52   88.98    89.9
   90.05   89.86   89.69   89.39   89.41   89.66   89.02   89.35   89.95   89.18
   89.66   90.02   89.88   89.39   89.87   89.51   89.05   89.11   89.92   89.24
   88.85   88.67   89.18   89.57   89.56   88.84   89.45   89.38    90.1   89.64
    90.1   90.02   89.75   90.09   89.56   89.68   89.17    89.3   89.25   90.16
   90.57   89.42   89.67   89.06
                                                                                
                                                                                
                                                                                
                                                                                
                                                   87.76   87.76   87.76   87.76
   87.77   87.84   87.86   87.87   87.87   87.83    87.8   87.79   87.76   87.74
   87.73   87.73   87.73
                                                                                
                                                                                
                                                                                
                                                                                
                                                                                
                                
  3556.5  3586.5  3606.5  3616.5  3626.5  3636.5  3646.5  3656.5  3676.5  3706.5
  3726.5  3746.5  3846.5  3866.5  3876.5  3886.5  3906.5  3936.5  4086.5  4176.5
  4356.5  4376.5  4386.5  4396.5  4416.5  4432.8  4462.8  4572.8  4582.8  4584.5
  4624.5  4644.5  4674.5  4757.2  4797.2  4817.2    4877    4916  4922.3  4938.2
  4939.2  4959.1 4959.21  4959.3    4961  4965.3  4965.4 4965.49  4965.6 4965.71
  4967.1  4984.3  4989.9  4991.3  4991.8  4999.4  5007.6  5010.1    5016    5020
  5023.7  5023.8 5023.89 5023.99  5024.1 5024.89    5025 5025.11  5034.3  5038.8
  5056.8  5069.7  5096.7  5114.7  5230.2  5250.2  5376.5  5446.5  5466.5  5521.7
    5567  5726.8  5756.8  5766.8  5846.8  5876.8  5906.8  5966.8  6006.8  6036.8
  6056.8  6126.8  6132.3  6142.3  6172.3  6252.3  6262.3  6282.3  6312.3  6412.3
  6422.3  6432.3  6442.3  6462.3  6692.3  6732.3  6832.3  7272.3  7302.3  7336.1
  7406.1  7615.2  7635.2  7675.2  7715.2  7835.2  7855.2  7865.2  7885.2  7915.2
  8246.1  8356.1  8366.1  8708.7
   90.12   89.47   87.91   87.67   87.74   88.39   88.15   88.16   88.72   88.43
   87.84   88.56   88.74   87.51   87.94    88.8   89.18   88.47   89.04   88.24
   88.25   87.45   87.44   87.72   88.75   89.21   88.04   87.95   88.34   88.34
   88.75   88.26   88.98   88.92   89.14   89.51   89.43   90.12   90.14   90.18
   90.18   90.24   90.24   90.24   90.25   90.26   90.26   90.26   92.66   92.66
   92.67   92.74   92.76   92.77   92.77   92.73    92.7   92.69   92.66   92.64
   92.63   92.63   92.63   92.63   92.63   92.63   92.63   90.23    90.2   90.19
   90.14    90.1   89.97   89.89   89.25   89.52    89.6   89.52   88.98    89.9
   90.05   89.86   89.69   89.39   89.41   89.66   89.02   89.35   89.95   89.18
   89.66   90.02   89.88   89.39   89.87   89.51   89.05   89.11   89.92   89.24
   88.85   88.67   89.18   89.57   89.56   88.84   89.45   89.38    90.1   89.64
    90.1   90.02   89.75   90.09   89.56   89.68   89.17    89.3   89.25   90.16
   90.57   89.42   89.67   89.06
                                                                                
                                                                                
                                                                                
                                                                                
                                                   87.76   87.76   87.76   87.76
   87.77   87.84   87.86   87.87   87.87   87.83    87.8   87.79   87.76   87.74
   87.73   87.73   87.73
                                                                                
                                                                                
                                                                                
                                                                                
                                                                                
                                
Abutment Skew #Up #Dn= , 2 , 2
  4959.1  4965.6
   89.23   87.54
  4959.1  4965.6
   88.95   87.26
BR Coef= 1 , 1 , 0 ,1.25, 0 ,,,0.8,-1,2,0,
WSPro=,,,, 1 ,,,, 0 ,,,, 0 ,,,,-1 ,-1 ,-1 , 0 , 0 , 0 , 0 , 0
BC Design=,, 0 ,, 0 ,,,,,,
BC HTab HWMax=93.89
BC Use User HTab Curves=0
BC User HTab FreeFlow(D)= 0

Type RM Length L Ch R = 1 ,15462.6 ,159,189,251
BEGIN DESCRIPTION:
Downstream Section of Bridge/Culvert/Weir;
BREEN - XS 2
 Levee placed to contain flow.  The levee is not a FEMA certified flood control levee. Expansion and contraction coefficients changed to 0.1 and 0.3 because channel underneath bridge structure is same size as channel upstream and downstream, there are no bridge piers, and no bridge abutments. - JJA 5/26/03
END DESCRIPTION:
XS GIS Cut Line= 6
      3088539.29     13891737.39      3087793.54     13891223.91
      3087591.57     13891216.64      3087362.38     13891254.49
      3086812.03     13891507.71      3083490.45     13891396.78
#Sta/Elev= 30
    3519   90.24  3678.9   87.94  3828.9   88.68  3848.9    87.8  3878.9   89.12
  3918.9   88.43  4348.9   87.86  4424.6   88.35    4859   88.17    4939   89.33
    4961   88.95  4965.3    87.4  4967.1   86.03  4991.3   77.81  4999.4   76.74
  5010.1   78.61    5016   80.99  5023.8   85.42 5023.89   87.36  5038.8   88.84
  5070.4   89.67  5290.4   88.11  5507.2   88.21  5854.5   89.72  6634.5   88.65
  6694.5    89.6  6824.5   88.45    7724   89.47  8294.5   90.86  8791.1   90.31
#Mann= 12 ,-1 , 0
    3519     .07       0  3848.9     .04       0  3918.9     .07       0
  4348.9     .04       0  4424.6     .07       0    4939     .04       0
  4965.3    .045       0 5023.89     .04       0  5038.8     .07       0
  5290.4     .12       0  5507.2     .08       0    7724     .12       0
#XS Ineff= 4 ,-1
    3519    4800    88.3    4800  4955.5    88.3 5023.89    5081    88.3
    5081  8791.1    88.3
Permanent Ineff=
       F       F       F       F
Bank Sta=4961,5023.89
XS Rating Curve= 0 ,0
Exp/Cntr=0.5,0.3

Type RM Length L Ch R = 1 ,15273.1 ,745,763,767
BEGIN DESCRIPTION:
Interpolated Channel - LIDAR overbanks
BREEN - XS 1
END DESCRIPTION:
XS GIS Cut Line= 4
      3088515.43      13891598.9      3087777.92      13891091.1
      3086932.35     13891127.39 3083632.924973313891062.8056183
#Sta/Elev= 30
  3542.9   88.79  3772.9   88.35  3802.9   89.18  3822.9   87.57  3852.9   88.56
    4137   87.72  4192.9   87.75  4412.9   88.99  4938.3   87.91  4958.3   85.75
 4999.36   75.13  5008.3   76.27  5048.3   85.81  5058.3   87.21  5078.3   88.66
  5158.3   88.28  5178.3    87.4  5394.7   88.27  5494.7   89.76  5674.7   90.39
  5724.7   89.59  6664.7    88.9  6864.7   89.38  6924.7   90.38  7114.7   89.34
  7624.7   89.34  7904.7    90.3  8004.7   89.81  8124.7   90.76  8584.7   90.66
#Mann= 9 ,-1 , 0
  3542.9     .07       0  3772.9     .04       0  3822.9     .06       0
    4137     .04       0  4192.9     .07       0  4938.3    .045       0
  5058.3     .12       0  5724.7     .08       0  7624.7     .12       0
#XS Ineff= 2 , 0
       0    4404      89               0
Permanent Ineff=
       F       F
Bank Sta=4938.3,5058.3
XS Rating Curve= 0 ,0
Exp/Cntr=0.3,0.1

Type RM Length L Ch R = 1 ,14510.3 ,690,726,750
BEGIN DESCRIPTION:
Cross Section X10;
END DESCRIPTION:
XS GIS Cut Line= 6
      3088995.36     13890679.44      3087817.67     13890458.87
      3087444.18     13890422.08      3087158.29     13890393.91
      3086863.02     13890369.87      3086112.26     13890340.87
#Sta/Elev= 30
  3139.2   88.71  3159.2   88.19  3179.2   86.92  3599.2   85.74  3639.2   86.93
  3669.2   86.45  3829.2   87.73  3889.2   86.76  4337.4   86.03  4728.4   87.11
  4787.5   86.95  4938.8   87.63  4975.4   76.35  4991.3   74.93  4992.6    70.8
  4999.2   68.64  5000.6   68.69  5007.4   70.86  5013.6    76.2  5026.1    81.7
  5044.8   88.39  5054.3   88.04  5068.2    89.5  5076.7   89.66  5089.9    89.9
  5566.2    88.8  5606.2      87  5616.2      87  5646.2    88.9  6047.5    90.2
#Mann= 4 ,-1 , 0
  3139.2     .99       0  4938.8     .04       0  5044.8     .04       0
  5076.7     .99       0
#XS Ineff= 2 , 0
         4932.47   87.66 5092.35           89.88
Permanent Ineff=
       F       F
#Block Obstruct= 2 , 0
         4936.56   87.63 5090.75            89.9
Bank Sta=4938.8,5044.8
XS Rating Curve= 0 ,0
Exp/Cntr=0.3,0.1

Type RM Length L Ch R = 1 ,13784.6 ,151,116,90
BEGIN DESCRIPTION:
Interpolated Channel - LIDAR overbanks
MOUNT HOUSTON - XS 4
END DESCRIPTION:
XS GIS Cut Line= 5
      3088854.15     13890214.68      3088242.15     13889817.31
      3087439.02     13889774.66      3087290.31     13889680.29
       3086936.5     13889703.42
#Sta/Elev= 30
  3365.3   88.69  3495.3   88.42  3655.3   87.05  3675.3    86.3  4055.3   86.71
  4085.3   85.71    4115   86.38    4155   85.61    4255   86.28    4785   86.62
  4899.3   87.62  4909.3   87.28  4939.3   83.13  4949.3   80.81  4979.3   72.11
  4989.3    70.8 5005.02   70.25 5006.41   69.64 5013.46   69.14 5015.23   69.87
 5017.89   71.86 5024.15   73.95 5034.31   78.07  5049.3   82.75  5059.3    85.4
  5069.3   86.94  5075.4   87.37  5105.4   87.67  5135.4   87.02  5429.9    88.7
#Mann= 4 ,-1 , 0
  3365.3     .99       0  4899.3     .04       0  5075.4      .1       0
  5135.4     .99       0
#XS Ineff= 2 , 0
         4894.24   87.59 5105.26           87.66
Permanent Ineff=
       F       F
#Block Obstruct= 2 , 0
         4896.48   87.61 5107.93           87.67
Bank Sta=4899.3,5075.4
XS Rating Curve= 0 ,0
Exp/Cntr=0.5,0.3

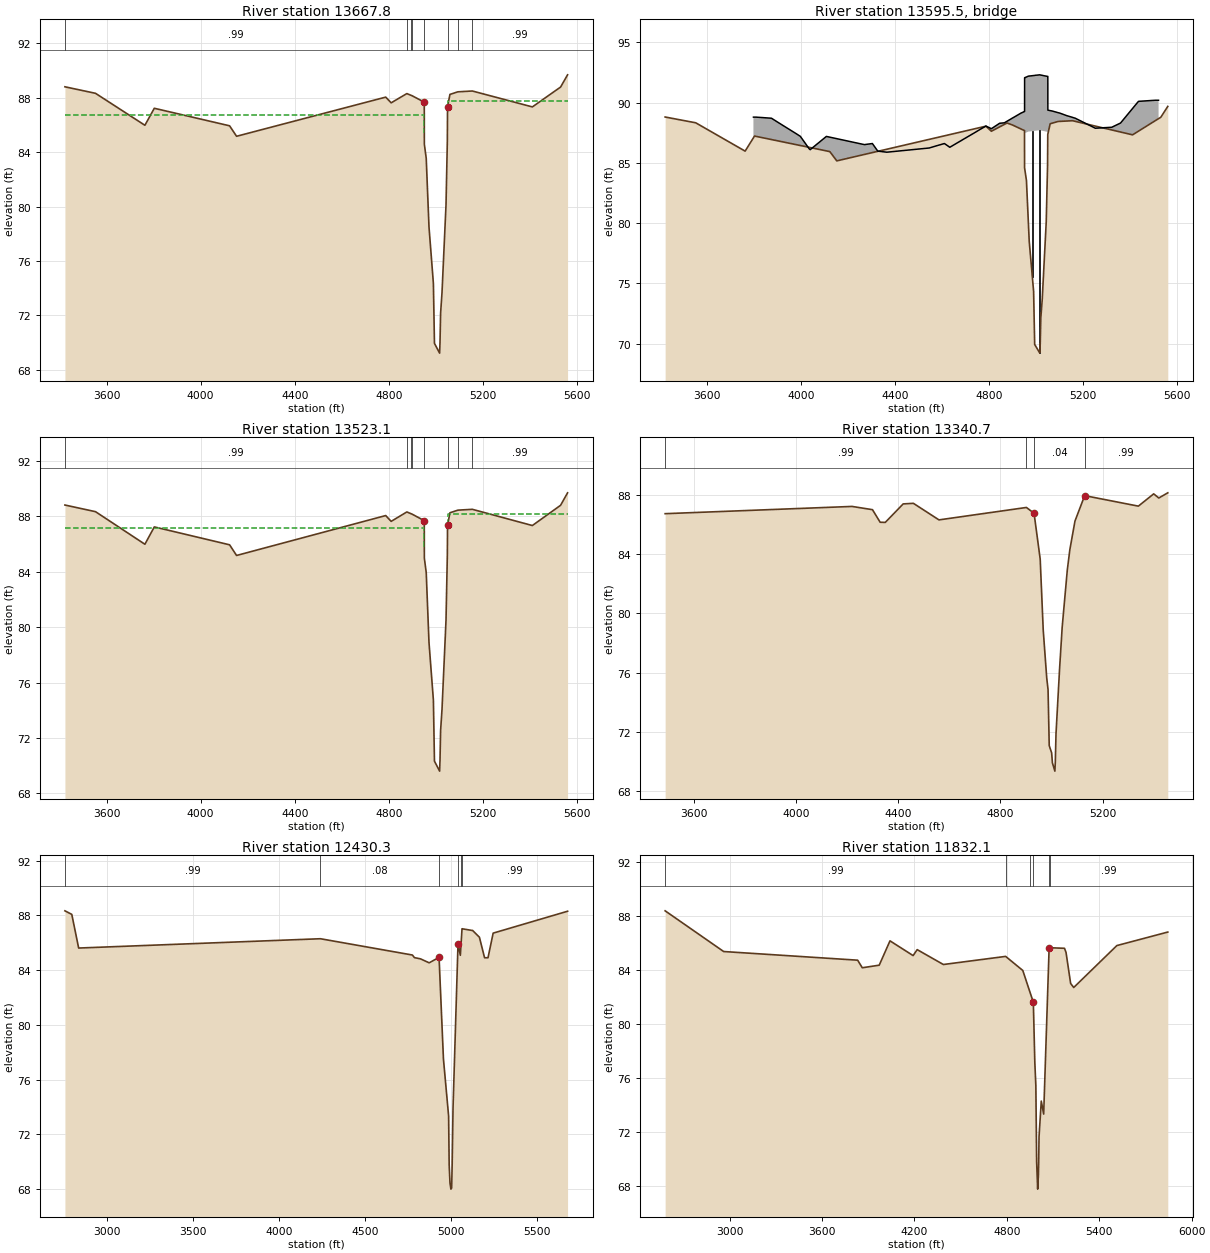
Type RM Length L Ch R = 1 ,13667.8 ,144,145,146
BEGIN DESCRIPTION:
Upstream Section of Bridge/Culvert/Weir;
MOUNT HOUSTON - XS 3
END DESCRIPTION:
XS GIS Cut Line= 5
      3088890.61     13890123.54      3088278.61     13889726.17
      3087434.79     13889640.32      3087118.79     13889594.97
       3086902.9      13889699.2
#Sta/Elev= 30
  3422.9   88.81  3552.9   88.33  3762.9   85.98  3802.9   87.23  4122.9   85.94
  4152.6   85.17 4786.62   88.05 4809.75   87.63  4876.4   88.31 4894.78   88.18
 4897.92   88.16 4950.55   87.68 4950.86   84.59 4958.83   83.55 4970.62    78.5
 4989.31   74.34 4993.83   69.94 5015.74   69.22 5017.43   70.01 5019.96   72.15
 5025.93   73.68 5042.94   80.11  5048.6   84.81 5049.45   87.35 5059.64   88.25
  5093.5   88.44 5154.93    88.5    5410   87.33    5530   88.79  5559.7   89.69
#Mann= 8 ,-1 , 0
  3422.9     .99       0  4876.4     .08       0 4894.78     .05       0
 4897.92     .04       0 4950.55     .04       0 5049.45     .04       0
  5093.5      .1       0 5154.93     .99       0
#XS Ineff= 2 , 0
       0 4950.78   86.74 5049.76       0   87.77
Permanent Ineff=
       F       F
Bank Sta=4950.55,5049.45
XS Rating Curve= 0 ,0
Skew Angle= 40
Exp/Cntr=0.5,0.3

Type RM Length L Ch R = 3 ,13595.5 ,,,
BEGIN DESCRIPTION:
MOUNT HOUSTON
Structure ID: E121-00-00-12
END DESCRIPTION:
Bridge Culvert--1,0,-1,-1, 0
Deck Dist Width WeirC Skew NumUp NumDn MinLoCord MaxHiCord MaxSubmerge Is_Ogee
18,109,2.6,40, 85, 85, , , 0.95, 0, ,,,
3798.271 3809.61 3874.87 3901.53 3978.14 3997.44 4035.74 4039.42 4108.364269.851
 4303.86 4326.84 4357.25 4364.914545.621 4576.26 4610.05 4633.03 4744.79 4752.45
 4759.04 4786.62 4809.754844.688 4865.064876.319  4876.4 4894.79 4897.934900.758
  4907.24936.919  4937.3 4948.72 4950.56 4950.64  4950.7 4950.78 4950.86 4950.94
 4951.01  4951.1 4958.834966.871 4970.62 4980.894984.109 4989.32 4993.84 4995.67
 5006.32 5014.52 5015.29 5015.74 5017.435019.959 5025.93 5032.525042.938 5048.53
 5048.61 5049.45 5049.525049.601 5049.67 5049.76 5049.84 5059.64 5065.23 5069.75
  5093.5  5099.7 5099.93 5130.65 5134.17 5154.935161.062 5166.355251.529  5321.4
 5358.78 5428.645435.149 5505.25 5520.34
    88.8    88.8   88.71   88.38   87.45   87.21   86.16    86.1    87.2   86.52
   86.61   85.98   85.91   85.89   86.24   86.42   86.61    86.3   87.58   87.67
   87.75   88.06   87.84   88.29   88.33   88.46   88.46   88.67   88.71   88.74
   88.81   89.15   89.15   89.25   89.27   89.27   89.27   89.27   89.27   92.07
   92.07   92.07   92.13    92.2   92.21   92.23   92.24   92.25   92.26   92.27
   92.29   92.31   92.31   92.31    92.3   92.29   92.27   92.24    92.2   92.18
   92.18   92.18   92.18   92.18   92.18   92.18   89.38   89.34   89.32    89.3
   89.17   89.14   89.14   88.92    88.9   88.78   88.74   88.71   87.88   87.96
   88.31   89.96   90.11    90.2    90.2
                                                                                
                                                                                
                                                                                
                                                   86.21   85.36   84.59   84.58
   87.47   87.47   87.53    87.6   87.61   87.63   87.64   87.65   87.66   87.67
   87.69   87.71   87.71   87.71    87.7   87.69   87.67   87.64    87.6   87.58
   87.58   87.58   87.58   87.36   87.37   87.38   87.38
                                                                                
                                        
3798.271 3809.61 3874.87 3901.53 3978.14 3997.44 4035.74 4039.42 4108.364269.851
 4303.86 4326.84 4357.25 4364.914545.621 4576.26 4610.05 4633.03 4744.79 4752.45
 4759.04 4786.62 4809.754844.688 4865.064876.319  4876.4 4894.79 4897.934900.758
  4907.24936.919  4937.3 4948.72 4950.56 4950.64  4950.7 4950.78 4950.86 4950.94
 4951.01  4951.1 4958.834966.871 4970.62 4980.894984.109 4989.32 4993.84 4995.67
 5006.32 5014.52 5015.29 5015.74 5017.435019.959 5025.93 5032.525042.938 5048.53
 5048.61 5049.45 5049.525049.601 5049.67 5049.76 5049.84 5059.64 5065.23 5069.75
  5093.5  5099.7 5099.93 5130.65 5134.17 5154.935161.062 5166.355251.529  5321.4
 5358.78 5428.645435.149 5505.25 5520.34
    88.8    88.8   88.71   88.38   87.45   87.21   86.16    86.1    87.2   86.52
   86.61   85.98   85.91   85.89   86.24   86.42   86.61    86.3   87.58   87.67
   87.75   88.06   87.84   88.29   88.33   88.46   88.46   88.67   88.71   88.74
   88.81   89.15   89.15   89.25   89.27   89.27   89.27   89.27   89.27   92.07
   92.07   92.07   92.13    92.2   92.21   92.23   92.24   92.25   92.26   92.27
   92.29   92.31   92.31   92.31    92.3   92.29   92.27   92.24    92.2   92.18
   92.18   92.18   92.18   92.18   92.18   92.18   89.38   89.34   89.32    89.3
   89.17   89.14   89.14   88.92    88.9   88.78   88.74   88.71   87.88   87.96
   88.31   89.96   90.11    90.2    90.2
                                                                                
                                                                                
                                                                                
                                                   86.21   85.36   84.59   84.58
   87.47   87.47   87.53    87.6   87.61   87.63   87.64   87.65   87.66   87.67
   87.69   87.71   87.71   87.71    87.7   87.69   87.67   87.64    87.6   87.58
   87.58   87.58   87.58   87.36   87.37   87.38   87.38
                                                                                
                                        
Pier Skew, UpSta & Num, DnSta & Num=  ,4984.104, 2 ,4984.104, 2 , 0 , 0 , 0 ,,
       2       2
   74.05   88.64
       2       2
   74.45   89.04
Pier Skew, UpSta & Num, DnSta & Num=  ,5015.283, 2 ,5015.283, 2 , 0 , 0 , 0 ,,
       2       2
    67.5   88.71
       2       2
    67.9   89.11
BR Coef= 1 , 1 , 0 ,1.25, 0 ,,,0.8,-1,2,0,
WSPro=,,,, 1 ,,,, 0 ,,,, 0 ,,,,-1 ,-1 ,-1 , 0 , 0 , 0 , 0 , 0
BR D #Sta/Elev= 66
3422.899   88.813552.899   88.33  3762.9   85.98  3782.9   86.45  3802.9   87.23
4122.898   85.94  4152.6   85.17 4744.79   87.57 4752.45   87.66 4759.04   87.74
 4786.62   88.05 4809.75   87.63 4844.68   88.28 4865.06    88.34876.319   88.31
  4876.4   88.31 4894.78   88.184897.918   88.164900.758   88.144907.188    88.1
4936.919   88.11  4937.3   88.11 4948.71   87.56 4950.55   87.68 4950.64   86.83
  4950.7   86.21 4950.78   85.36 4950.86   84.59 4950.94   84.58 4951.01   84.57
  4951.1   84.56 4958.83   83.954966.871   80.51 4970.62    78.9 4980.89   76.44
  4984.1   75.57 4989.31   74.74 4993.83   70.34 5015.74   69.62 5017.43   70.41
5019.959   72.55 5025.93   74.08 5032.52   76.785042.938   80.51 5048.53   85.15
  5048.6   85.21 5049.45   87.35 5049.52   87.365049.601   87.36 5049.67   87.37
 5049.75   87.38 5049.84   87.38 5059.64   88.25 5065.23   88.35 5069.75   88.43
  5093.5   88.44  5099.7   88.44 5099.93   88.44 5130.65   88.34 5134.17   88.36
 5154.93    88.55161.062   88.21    5320   87.51    5410   87.33    5530   88.79
  5559.7   89.69
BR D #Mann= 8
3422.899     .99  4876.4     .08 4894.78     .054897.918     .04 4950.55     .04
 5049.45     .04  5093.5      .1 5154.93     .99
BR D Banks=4950.55,5049.45
BC Design=,, 0 ,, 0 ,,,,,,
BC HTab HWMax=90.2
BC Use User HTab Curves=0
BC User HTab FreeFlow(D)= 0

Type RM Length L Ch R = 1 ,13523.1 ,148,183,206
BEGIN DESCRIPTION:
Downstream Section of Bridge/Culvert/Weir;
MOUNT HOUSTON - XS 2
END DESCRIPTION:
XS GIS Cut Line= 5
      3088992.19     13890030.89      3088379.18     13889632.86
      3087534.26      13889546.9      3087216.85     13889501.35
      3086999.59     13889606.24
#Sta/Elev= 30
  3422.9   88.81  3552.9   88.33  3762.9   85.98  3802.9   87.23  4122.9   85.94
  4152.6   85.17 4786.62   88.05 4809.75   87.63  4876.4   88.31 4894.78   88.18
 4897.92   88.16 4950.55   87.68 4950.86   84.98 4958.83   83.94 4970.62   78.89
 4989.31   74.73 4993.83   70.33 5015.74   69.61 5017.43    70.4 5019.96   72.54
 5025.93   74.07 5042.94    80.5  5048.6    85.2 5049.45   87.35 5059.64   88.25
  5093.5   88.44 5154.93    88.5    5410   87.33    5530   88.79  5559.7   89.69
#Mann= 8 ,-1 , 0
  3422.9     .99       0  4876.4     .08       0 4894.78     .05       0
 4897.92     .04       0 4950.55     .04       0 5049.45     .04       0
  5093.5      .1       0 5154.93     .99       0
#XS Ineff= 2 , 0
       0 4950.78   87.13 5049.76       0   88.16
Permanent Ineff=
       F       F
Bank Sta=4950.55,5049.45
XS Rating Curve= 0 ,0
Skew Angle= 40
Exp/Cntr=0.5,0.3

Type RM Length L Ch R = 1 ,13340.7 ,938,910,869
BEGIN DESCRIPTION:
Interpolated Channel - LIDAR overbanks
MOUNT HOUSTON - XS 1
END DESCRIPTION:
XS GIS Cut Line= 5
      3089031.26     13889924.12      3088418.24     13889526.09
      3087739.31     13889462.93        3087562.     13889354.26
       3087259.1      13889188.9
#Sta/Elev= 30
  3489.1   86.75    4220   87.24    4300   87.02    4330   86.17    4350   86.16
    4420   87.41    4460   87.45    4560   86.33  4901.9   87.17  4931.9   86.78
 4955.89   83.68 4967.79   78.87  4981.4   75.65 4986.66   74.84 4991.22   71.06
 5000.64   70.58 5003.69    69.9 5013.34   69.34 5015.09      70 5017.72   71.87
  5031.9   76.31  5041.9   79.08  5061.9   82.94  5071.9   84.32  5091.9   86.25
  5129.8   87.97  5339.8   87.26  5399.8   88.09  5419.8   87.81  5454.9   88.16
#Mann= 4 ,-1 , 0
  3489.1     .99       0  4901.9     .05       0  4931.9     .04       0
  5129.8     .99       0
Bank Sta=4931.9,5129.8
XS Rating Curve= 0 ,0
Exp/Cntr=0.3,0.1

Type RM Length L Ch R = 1 ,12430.3 ,587,598,599
BEGIN DESCRIPTION:
Cross Section X09
END DESCRIPTION:
XS GIS Cut Line= 6
      3089755.73     13889155.06      3088350.61     13888666.91
      3087832.02     13888533.72      3087606.37     13888540.87
      3087482.03     13888545.72      3086938.61      13888442.5
#Sta/Elev= 29
  2754.3   88.33  2794.3   88.07  2834.3   85.61  4241.8   86.29  4777.2    85.1
    4789   84.91  4824.3   84.82  4874.9   84.53  4932.5   84.93    4958    77.5
  4988.1   73.33  4991.3   69.77    4996   68.45  5001.4   67.99  5005.7   68.07
  5008.7   69.75  5013.8   73.92  5042.8   85.93  5056.4   85.08  5062.2   86.24
    5066      87  5066.1   87.02    5123    86.9  5127.4    86.9  5167.4    86.4
  5197.4    84.9  5217.4    84.9  5247.4    86.7  5680.6    88.3
#Mann= 6 ,-1 , 0
  2754.3     .99       0  4241.8     .08       0  4932.5     .04       0
  5042.8     .04       0  5062.2     .08       0    5066     .99       0
Bank Sta=4932.5,5042.8
XS Rating Curve= 0 ,0
Exp/Cntr=0.3,0.1

Type RM Length L Ch R = 1 ,11832.1 ,502,494,493
BEGIN DESCRIPTION:
Cross Section X08
END DESCRIPTION:
XS GIS Cut Line= 5
      3090060.17      13888698.3      3088541.75      13887982.5
      3088010.01     13888002.28      3087799.01     13887981.82
      3086960.95     13887913.93
#Sta/Elev= 30
  2581.3   88.37  2961.3   85.36  3831.3   84.72  3861.3   84.16  3971.3   84.35
  4041.3   86.15  4191.3   85.06  4217.9    85.5  4387.9    84.4  4792.2      85
  4903.5   83.96  4951.2   82.32    4972   81.61  4981.7   77.13  4988.3   75.46
  4993.5   69.79  5000.1   67.79  5004.8   68.81  5006.6   69.68    5009   71.66
  5023.5    74.3  5039.1   73.34  5074.6   85.65  5079.1   85.64  5174.2    85.6
  5184.2    85.3  5214.2      83  5234.2    82.7  5514.2    85.8    5845    86.8
#Mann= 6 ,-1 , 0
  2581.3     .99       0  4792.2     .07       0  4951.2     .04       0
    4972     .04       0  5074.6     .04       0  5079.1     .99       0
Bank Sta=4972,5074.6
XS Rating Curve= 0 ,0
Exp/Cntr=0.3,0.1