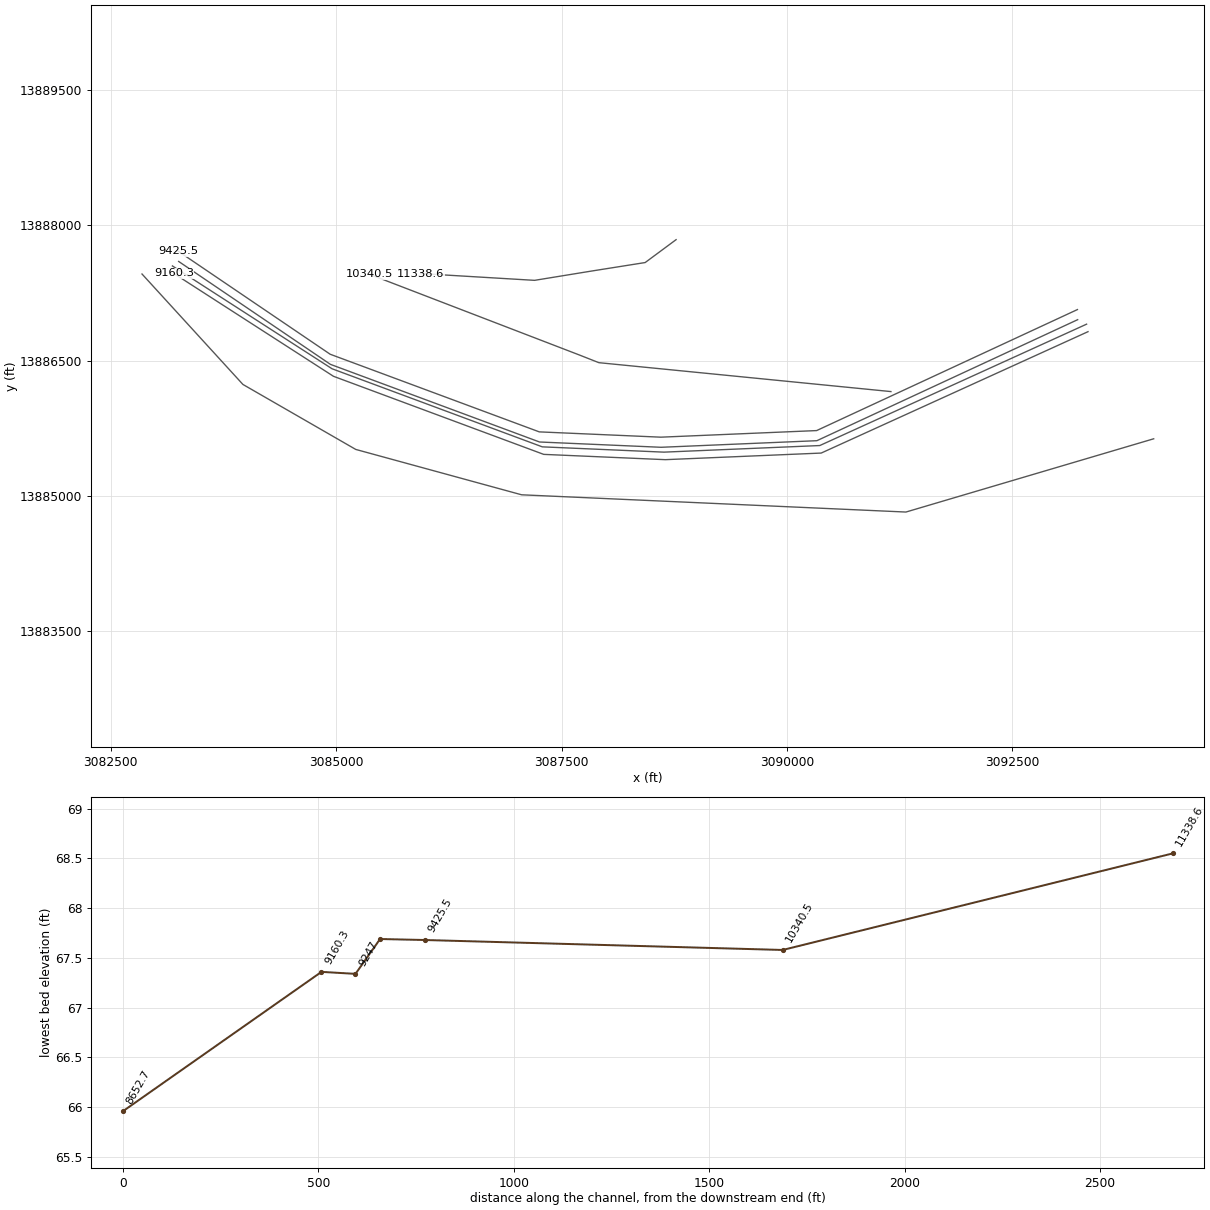
HEC-RAS study E121-00-00.prj: E121-00-00 LOMR

--- E121-00-00.g01 (geometry) --- (continued)

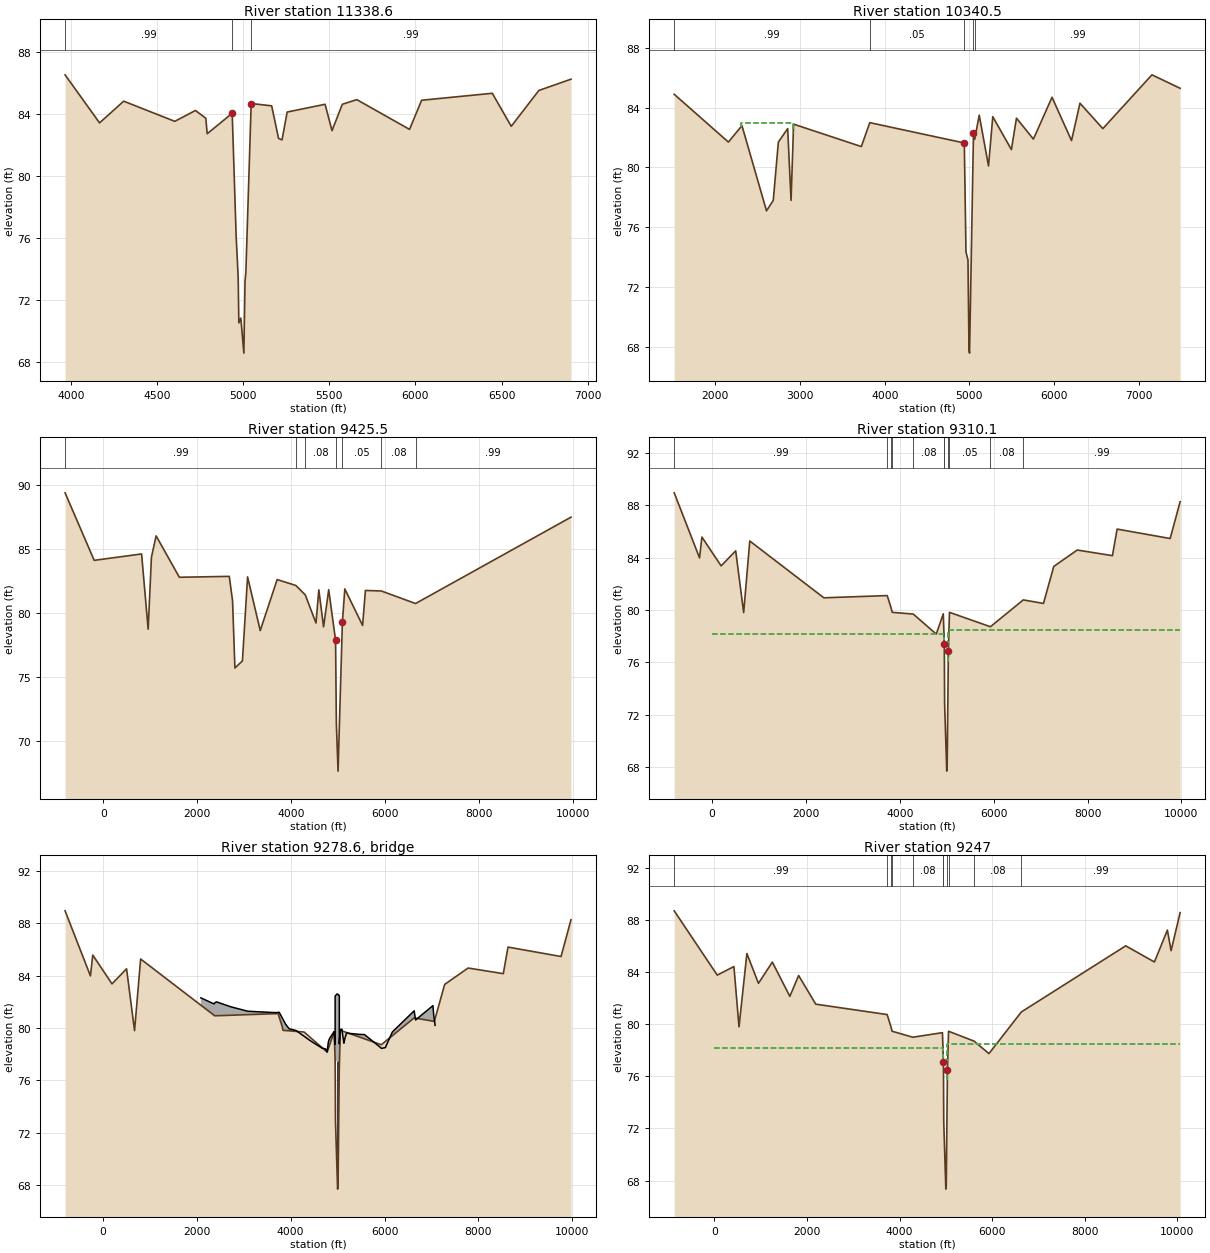
Type RM Length L Ch R = 1 ,11338.6 ,1131,998,897
BEGIN DESCRIPTION:
Cross Section X07; Ineffective islands on left and right overbank
END DESCRIPTION:
XS GIS Cut Line= 5
      3088769.99     13887839.48      3088427.16     13887586.08
      3087832.51     13887491.86      3087200.91     13887388.95
      3085936.54     13887464.26
#Sta/Elev= 30
  3967.4    86.5  4167.4    83.4  4307.4    84.8  4603.7    83.5  4723.7    84.2
  4783.7    83.7  4791.8    82.7  4936.9   84.02  4959.9   76.06  4971.6   73.43
  4975.3    70.5  4986.9   70.81  5004.6   68.55  5011.3    73.2    5016   73.73
    5047   84.65  5165.8    84.5  5205.8    82.4  5225.8    82.3  5255.8    84.1
  5475.8    84.6  5515.8    82.9  5575.8    84.6  5659.8    84.9  5965.7   82.98
  6035.7   84.86  6445.7   85.31  6555.7   83.18  6715.7   85.49  6902.3   86.22
#Mann= 3 ,-1 , 0
  3967.4     .99       0  4936.9     .04       0    5047     .99       0
Bank Sta=4936.9,5047
XS Rating Curve= 0 ,0
Exp/Cntr=0.3,0.1

Type RM Length L Ch R = 1 ,10340.5 ,757,915,1024
BEGIN DESCRIPTION:
Cross Section X06
END DESCRIPTION:
XS GIS Cut Line= 4
      3091152.26       13886157.      3087913.87     13886477.16
      3087692.22     13886564.29       3085374.4     13887454.22
#Sta/Elev= 30
  1513.5    84.9  2153.6    81.7  2313.6    82.8  2603.6    77.1  2683.6    77.8
  2743.6    81.7  2853.6    82.6  2893.6    77.8  2923.6    82.9  3723.6    81.4
  3823.6      83  4939.7   81.64  4959.7   74.35  4983.1   73.81  4995.2   67.82
  5001.7   67.58  5048.3   82.34  5062.5   81.88  5115.9    83.5  5225.9    80.1
  5275.9    83.4  5495.9    81.2  5555.9    83.3  5755.9    81.9  5975.9    84.7
  6205.9    81.8  6305.9    84.3  6575.9    82.6  7155.9    86.2  7488.7    85.3
#Mann= 5 ,-1 , 0
  1513.5     .99       0  3823.6     .05       0  4939.7     .04       0
  5048.3     .04       0  5062.5     .99       0
#XS Ineff= 1 ,-1
    2300    2920      83
Permanent Ineff=
       F
Bank Sta=4939.7,5048.3
XS Rating Curve= 0 ,0
Exp/Cntr=0.3,0.1

Type RM Length L Ch R = 1 ,9425.5  ,116,115,109
BEGIN DESCRIPTION:
Interpolated Channel - LIDAR overbanks
GULF BANK - XS 4
END DESCRIPTION:
XS GIS Cut Line= 6
      3093220.19     13887065.34      3090328.51     13885725.08
       3088601.6     13885652.04      3087253.18     13885710.67
      3084934.51     13886570.48      3083251.93     13887710.06
#Sta/Elev= 30
  -815.3    89.4  -195.3   84.13   814.7   84.63   954.7   78.76  1024.7   84.38
  1124.7   86.04  1619.1   82.81    2683   82.88    2753   80.97    2803   75.73
    2963   76.28    3073   82.84    3343   78.65    3703   82.63  4101.4   82.17
  4301.4   81.44  4530.7   79.24  4590.7   81.83  4691.8   78.94  4801.8   81.84
  4947.7   77.89  4964.8   71.35 5000.72   67.68  5093.1   79.31  5144.7    81.9
  5523.9   79.05  5583.9   81.78  5922.2   81.74  6652.2   80.76  9963.8    87.5
#Mann= 7 ,-1 , 0
  -815.3     .99       0  4101.4     .05       0  4301.4     .08       0
  4947.7     .04       0  5093.1     .05       0  5922.2     .08       0
  6652.2     .99       0
Bank Sta=4947.7,5093.1
XS Rating Curve= 0 ,0
Exp/Cntr=0.5,0.3

Type RM Length L Ch R = 1 ,9310.1  ,64,63,62
BEGIN DESCRIPTION:
Upstream Section of Bridge/Culvert/Weir
GULF BANK - XS 3
END DESCRIPTION:
XS GIS Cut Line= 6
      3093222.79     13886953.36      3090331.12      13885613.1
      3088604.21     13885540.06      3087255.78     13885598.69
      3084937.12      13886458.5      3083254.53     13887598.08
#Sta/Elev= 30
  -805.9   88.95  -265.9   83.98  -215.9   85.57   194.1   83.37   504.1   84.52
   674.1    79.8   804.1   85.27  2382.4   80.93  3732.6    81.1  3811.8    80.2
  3839.4   79.82  4286.7   79.69  4777.7   78.16  4927.3   79.71    4943   78.03
  4948.7   77.42  4955.3   72.87  5000.6   67.69  5009.4   67.91  5035.6   76.84
  5059.1   79.82  5931.6   78.72  6631.6   80.77  7061.6    80.5  7281.6   83.33
  7781.6   84.58  8531.1   84.15  8631.1   86.18  9761.1   85.46  9973.2   88.27
#Mann= 11 ,-1 , 0
  -805.9     .99       0  3732.6     .12       0  3811.8     .08       0
  3839.4     .05       0  4286.7     .08       0    4943     .04       0
  4948.7     .04       0  5035.6     .04       0  5059.1     .05       0
  5931.6     .08       0  6631.6     .99       0
#XS Ineff= 2 , 0
       0  4948.7   78.17 5033.29       0   78.46
Permanent Ineff=
       F       F
Bank Sta=4948.7,5035.6
XS Rating Curve= 0 ,0
Exp/Cntr=0.5,0.3

Type RM Length L Ch R = 3 ,9278.6  ,,,
BEGIN DESCRIPTION:
GULF BANK
Structure ID: E121-00-00-11
END DESCRIPTION:
Bridge Culvert--1,0,-1,-1, 0
Deck Dist Width WeirC Skew NumUp NumDn MinLoCord MaxHiCord MaxSubmerge Is_Ogee
14,35,2.6,0, 87, 87, 78.65, , 0.95, 0, ,,,
  2086.4  2366.9  2380.7  2382.6  2416.9  2732.6  3086.9  3692.6  3732.5  3732.6
  3756.2  3772.6  3811.8  3812.6  3839.4  3862.6  3892.6  3966.2    4111  4147.3
  4286.7  4390.2  4429.9  4653.1  4661.3  4743.9  4777.7  4789.3  4802.1  4825.7
  4825.8  4865.9  4886.1  4923.5  4927.3    4943 4943.21  4943.3 4947.59  4947.7
 4947.81  4948.7  4948.8  4955.3  4968.3  4977.5  4982.8  4989.4  4989.8  4991.8
  5000.6  5007.6  5009.4  5010.7  5011.1  5018.7  5024.5 5033.29  5033.4  5035.6
 5036.99  5037.1 5037.21  5042.9  5059.1  5060.3  5084.3  5091.6  5133.7  5137.1
  5157.8  5190.3  5240.7  5414.6  5463.4  5570.7  5610.2  5917.7  5931.8  6017.7
  6167.7  6631.7  6631.8  6661.8  7031.8  7047.7  7077.7
    82.3   81.84   81.91   81.91      82   81.61   81.28   81.17   81.19   81.19
    81.2   81.09   80.83   80.82   80.65   80.49   80.29   79.94   79.81   79.72
   79.37    79.1      79    78.5   78.47    78.4   78.17   78.52   78.91   79.18
   79.18    79.4   79.51    79.7   79.72   78.74   78.74   78.74   78.74   82.44
   82.44   82.44   82.44   82.47   82.52   82.56   82.58   82.61   82.61    82.6
   82.58   82.56   82.56   82.55   82.55   82.53   82.51   82.49   82.49   82.48
   82.48   82.48   78.78   79.22   79.83   79.88   79.91   79.92   78.84    78.9
   79.23   79.61   79.59   79.53   79.51    79.5   79.39    78.5   78.44    78.5
    79.7   81.31   81.31   80.61   81.71      81    80.2
                                                                                
                                                                                
                                                                                
                                                                                
                   77.34   77.37   77.42   77.46   77.48   77.51   77.51    77.5
   77.48   77.46   77.46   77.45   77.45   77.43   77.41   77.39
                                                                                
                                                                                
                                                        
  2086.4  2366.9  2380.7  2382.6  2416.9  2732.6  3086.9  3692.6  3732.5  3732.6
  3756.2  3772.6  3811.8  3812.6  3839.4  3862.6  3892.6  3966.2    4111  4147.3
  4286.7  4390.2  4429.9  4653.1  4661.3  4743.9  4777.7  4789.3  4802.1  4825.7
  4825.8  4865.9  4886.1  4923.5  4927.3    4943 4943.21  4943.3 4947.59  4947.7
 4947.81  4948.7  4948.8  4955.3  4968.3  4977.5  4982.8  4989.4  4989.8  4991.8
  5000.6  5007.6  5009.4  5010.7  5011.1  5018.7  5024.5 5033.29  5033.4  5035.6
 5036.99  5037.1 5037.21  5042.9  5059.1  5060.3  5084.3  5091.6  5133.7  5137.1
  5157.8  5190.3  5240.7  5414.6  5463.4  5570.7  5610.2  5917.7  5931.8  6017.7
  6167.7  6631.7  6631.8  6661.8  7031.8  7047.7  7077.7
    82.3   81.84   81.91   81.91      82   81.61   81.28   81.17   81.19   81.19
    81.2   81.09   80.83   80.82   80.65   80.49   80.29   79.94   79.81   79.72
   79.37    79.1      79    78.5   78.47    78.4   78.17   78.52   78.91   79.18
   79.18    79.4   79.51    79.7   79.72   78.74   78.74   78.74   78.74   82.44
   82.44   82.44   82.44   82.47   82.52   82.56   82.58   82.61   82.61    82.6
   82.58   82.56   82.56   82.55   82.55   82.53   82.51   82.49   82.49   82.48
   82.48   82.48   78.78   79.22   79.83   79.88   79.91   79.92   78.84    78.9
   79.23   79.61   79.59   79.53   79.51    79.5   79.39    78.5   78.44    78.5
    79.7   81.31   81.31   80.61   81.71      81    80.2
                                                                                
                                                                                
                                                                                
                                                                                
                   77.34   77.37   77.42   77.46   77.48   77.51   77.51    77.5
   77.48   77.46   77.46   77.45   77.45   77.43   77.41   77.39
                                                                                
                                                                                
                                                        
Pier Skew, UpSta & Num, DnSta & Num=  ,4977.5, 2 ,4977.5, 2 , 0 , 0 , 0 ,,
     1.2     1.2
   69.43   78.46
     1.2     1.2
   69.08   78.11
Pier Skew, UpSta & Num, DnSta & Num=  ,5007.6, 2 ,5007.6, 2 , 0 , 0 , 0 ,,
     1.2     1.2
   66.74   78.46
     1.2     1.2
   66.39   78.11
BR Coef= 1 , 1 , 0 ,1.25, 0 ,,,0.8,0,2,0,
WSPro=,,,, 1 ,,,, 0 ,,,, 0 ,,,,-1 ,-1 ,-1 , 0 , 0 , 0 , 0 , 0
BR D #Sta/Elev= 160
  -867.4   88.72  -827.4   88.95  -767.4   88.76  -747.4   87.82  -717.4   87.45
  -277.4   85.04  -227.4   85.78     2.6   84.38    62.6   83.78   112.6    84.2
   142.6    83.7   212.6   84.62   422.6   84.44   462.6   82.89   492.6   81.18
   532.6   79.81   702.6   85.44   742.6   84.96   782.6   83.98   872.6   84.31
   952.6   83.15   992.6   84.37  1042.6   84.54  1072.6   84.05  1102.6   84.66
  1212.6   84.33  1252.6   84.78  1356.4   83.65  1360.7   83.95  1416.4   83.66
  1446.4    83.5  1476.4   83.34  1530.7   83.05  1560.7   83.85  1596.4    83.4
  1600.7   83.35  1630.7   82.15  1646.4   82.28  1820.7   83.75  1846.4   83.53
  1890.7   83.15  2036.4   83.32  2060.7   83.35  2086.4   82.99  2190.7   81.55
  2320.7   81.85  2340.7   81.35  2366.9   81.48  2380.7   81.55  2382.6   81.55
  2416.9   81.52  2732.6   81.25  3086.9   80.92  3692.6   80.35  3732.5   80.75
  3732.6   80.75  3756.2    80.1  3772.6   79.65  3811.8   79.85  3812.6   79.85
  3839.4   79.47  3862.6   79.15  3892.6   79.65  3966.2   79.58    4111   79.45
  4147.3   79.36  4286.7   79.01  4390.2   78.75  4429.9   78.62  4653.1   77.88
  4661.3   77.85  4743.9   78.04  4777.7   77.81  4789.3   78.16  4802.1   78.55
  4825.7   78.82  4825.8   78.82  4865.9   79.04  4886.1   79.15  4923.5   79.34
  4927.3   79.36    4943   77.68 4943.21   77.66  4943.3   77.65 4947.59   77.19
  4947.7   77.18 4947.81   77.17  4948.7   77.07  4948.8    76.2  4955.3   72.52
  4968.3   70.09  4977.5   70.08  4982.8   70.33  4989.4   68.41  4989.8   68.29
  4991.8   67.68  5000.6   67.34  5007.6    67.4  5009.4   67.56  5010.7   68.48
  5011.1   69.39  5018.7   70.01  5024.5   72.12 5033.29   75.58  5033.4   75.62
  5035.6   76.49 5036.99   76.94  5037.1   76.98 5037.21   77.01  5042.9   78.86
  5059.1   79.47  5060.3   79.52  5084.3   79.55  5091.6   79.56  5133.7   78.48
  5137.1   78.54  5157.8   78.87  5190.3   79.25  5240.7   79.23  5414.6   79.17
  5463.4   79.15  5570.7   78.83  5610.2   78.71  5917.7   77.79  5931.8   77.75
  6017.7   78.14  6167.7   78.83  6631.7   80.95  6631.8   80.95  6661.8   80.25
  7031.8   81.35  7047.7   80.99  7071.8   80.45  7077.7   80.49  7151.8   80.95
  7157.7   81.03  7277.7   82.75  7291.8   82.95  7437.7   82.66  7441.8   82.65
  7487.7   82.92  7661.8   83.95  7677.7   83.73  7741.8   82.85  7757.7   83.41
  7781.8   84.25  8020.8   84.05    8074   84.85  8196.7    84.8  8576.7   85.19
  8606.7   84.19  8886.7   86.03  9456.7   86.42  9506.7   84.79  9566.7   85.15
  9786.7   87.24  9836.7   86.36  9866.7   85.66  9956.7   88.23 10061.7   88.58
BR D #Mann= 11
  -867.4     .99  3732.6     .12  3811.8     .08  3839.4     .05  4286.7     .08
    4943     .04  4948.7     .04  5035.6     .04  5059.1     .05  5610.2     .08
  6631.8     .99
BC Design=,, 0 ,, 0 ,,,,,,
BC HTab HWMax=88.95
BC Use User HTab Curves=0
BC User HTab FreeFlow(D)= 0

Type RM Length L Ch R = 1 ,9247    ,88,87,83
BEGIN DESCRIPTION:
Downstream Section of Bridge/Culvert/Weir
GULF BANK - XS 2
END DESCRIPTION:
XS GIS Cut Line= 6
      3093321.98     13886903.77      3090363.43     13885559.36
      3088635.18     13885486.27      3087286.43     13885544.91
      3084955.36     13886409.59       3083185.1     13887548.48
#Sta/Elev= 30
  -867.4   88.72    62.6   83.78   422.6   84.44   532.6   79.81   702.6   85.44
   952.6   83.15  1252.6   84.78  1630.7   82.15  1820.7   83.75  2190.7   81.55
  3732.6   80.75  3811.8   79.85  3839.4   79.47  4286.7   79.01  4927.3   79.36
    4943   77.68  4948.7   77.07  4955.3   72.52  5000.6   67.34  5009.4   67.56
  5035.6   76.49  5059.1   79.47  5610.2   78.71  5931.8   77.75  6631.8   80.95
  8886.7   86.03  9506.7   84.79  9786.7   87.24  9866.7   85.66 10061.7   88.58
#Mann= 11 ,-1 , 0
  -867.4     .99       0  3732.6     .12       0  3811.8     .08       0
  3839.4     .05       0  4286.7     .08       0    4943     .04       0
  4948.7     .04       0  5035.6     .04       0  5059.1     .05       0
  5610.2     .08       0  6631.8     .99       0
#XS Ineff= 2 , 0
       0  4948.7   78.17 5033.29       0   78.46
Permanent Ineff=
       F       F
Bank Sta=4948.7,5035.6
XS Rating Curve= 0 ,0
Exp/Cntr=0.5,0.3

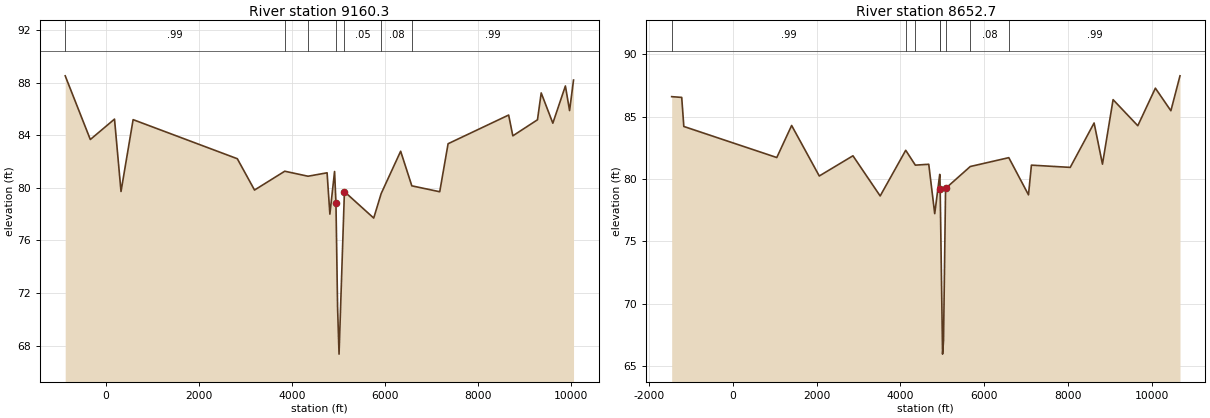
Type RM Length L Ch R = 1 ,9160.3  ,498,508,491
BEGIN DESCRIPTION:
Interpolated Channel - LIDAR overbanks
GULF BANK - XS 1
END DESCRIPTION:
XS GIS Cut Line= 6
       3093337.6     13886820.44      3090379.06     13885476.03
       3088650.8     13885402.93      3087302.06     13885461.58
      3084970.98     13886326.26      3083200.73     13887465.15
#Sta/Elev= 30
  -869.7   88.51  -329.7   83.67   190.3   85.22   330.3   79.72   590.3   85.18
  2830.7   82.21  3200.7   79.83  3850.7   81.26  4350.5   80.88  4760.8   81.14
  4820.8      78  4921.6   81.24  4951.6   78.84 4986.65   70.89 5017.92   67.36
  5133.4   79.71  5763.3    77.7  5923.3   79.56  6342.5   82.78  6582.5   80.15
  7182.5    79.7  7362.5   83.35  8664.4   85.53  8754.4   83.95  9284.4   85.17
  9364.4   87.21  9614.4   84.91  9884.4   87.74  9974.4   85.87 10059.4   88.19
#Mann= 7 ,-1 , 0
  -869.7     .99       0  3850.7     .05       0  4350.5     .08       0
  4951.6     .04       0  5133.4     .05       0  5923.3     .08       0
  6582.5     .99       0
Bank Sta=4951.6,5133.4
XS Rating Curve= 0 ,0
Exp/Cntr=0.3,0.1

Type RM Length L Ch R = 1 ,8652.7  ,201,188,178
BEGIN DESCRIPTION:
Cross Section X05
END DESCRIPTION:
XS GIS Cut Line= 6
      3094065.88     13885634.18       3091318.5     13884822.84
      3087057.32     13885013.85      3085218.03     13885516.31
      3083966.86     13886236.06      3082847.87     13887459.22
#Sta/Elev= 30
   -1463    86.6   -1223   86.54   -1173   84.21    1047   81.72  1401.7   84.29
  2061.7   80.24  2865.8   81.86  3515.8   78.64  4125.8    82.3  4355.8   81.11
  4675.8   81.18  4818.6   77.22    4938   80.37  4941.6   80.28 4948.56   79.17
 5005.75   65.96  5028.7   67.04 5077.48   79.24  5667.5      81  6587.5   81.71
  7057.5   78.73  7127.5   81.11  8054.2   80.93  8624.2   84.49  8824.2   81.19
  9077.6   86.36  9667.6   84.27 10087.6   87.28 10457.6   85.47 10675.4   88.27
#Mann= 9 ,-1 , 0
   -1463     .99       0  4125.8     .05       0  4355.8     .08       0
    4938     .04       0  4941.6     .04       0 4948.56    .045       0
 5077.48     .05       0  5667.5     .08       0  6587.5     .99       0
Bank Sta=4948.56,5077.48
XS Rating Curve= 0 ,0
Exp/Cntr=0.3,0.1