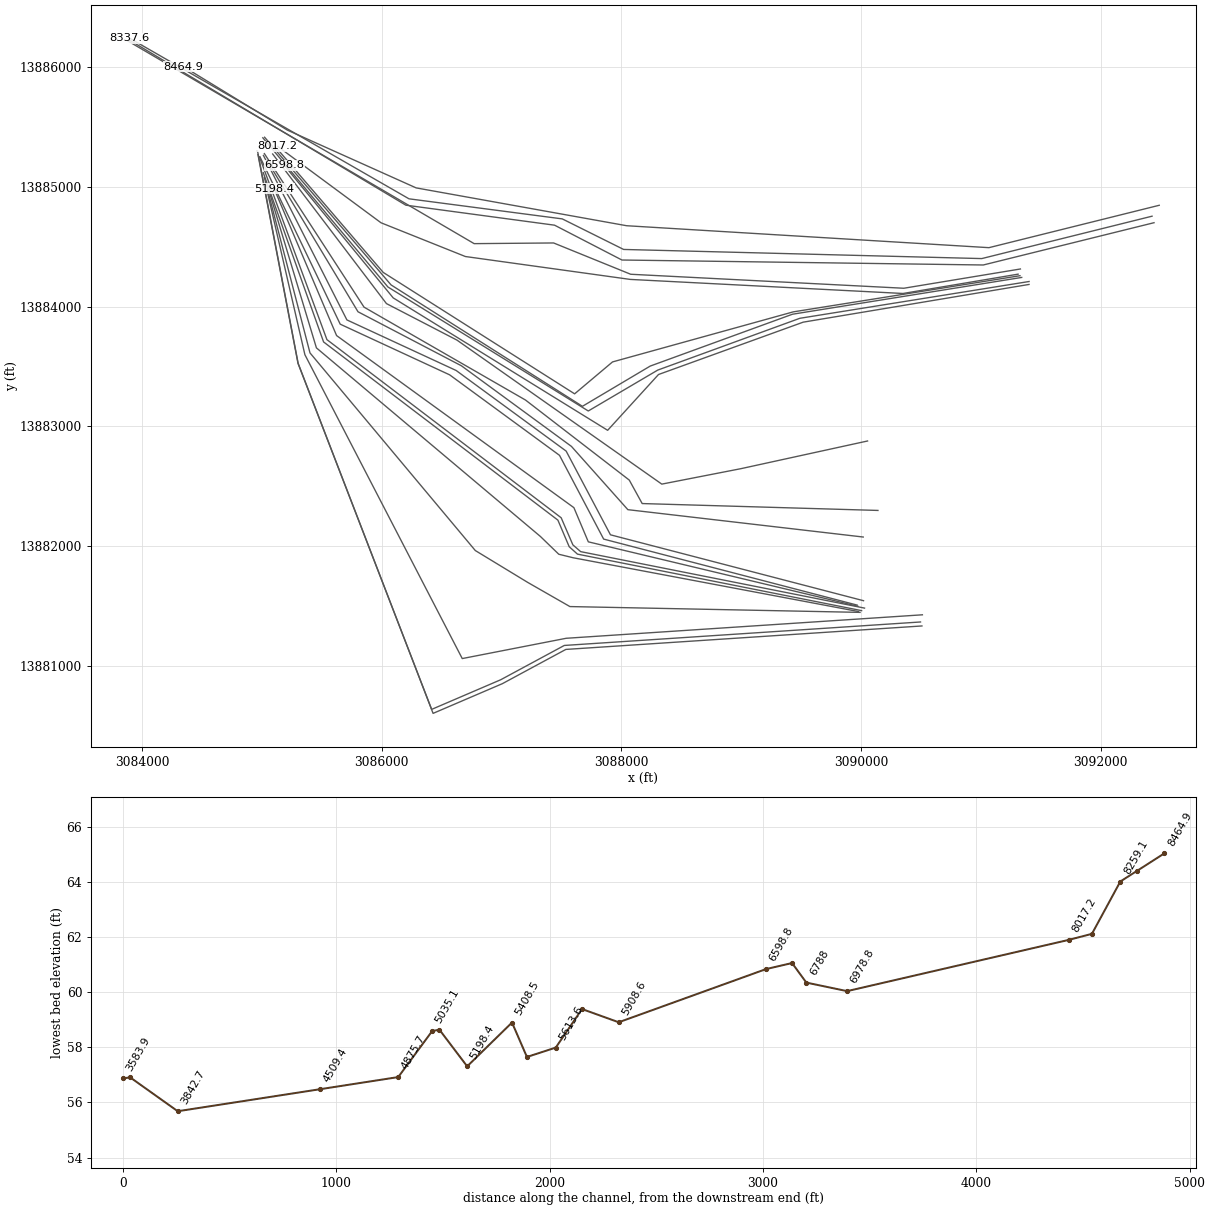
HEC-RAS study E121-00-00.prj: E121-00-00 LOMR

--- E121-00-00.g01 (geometry) --- (continued)

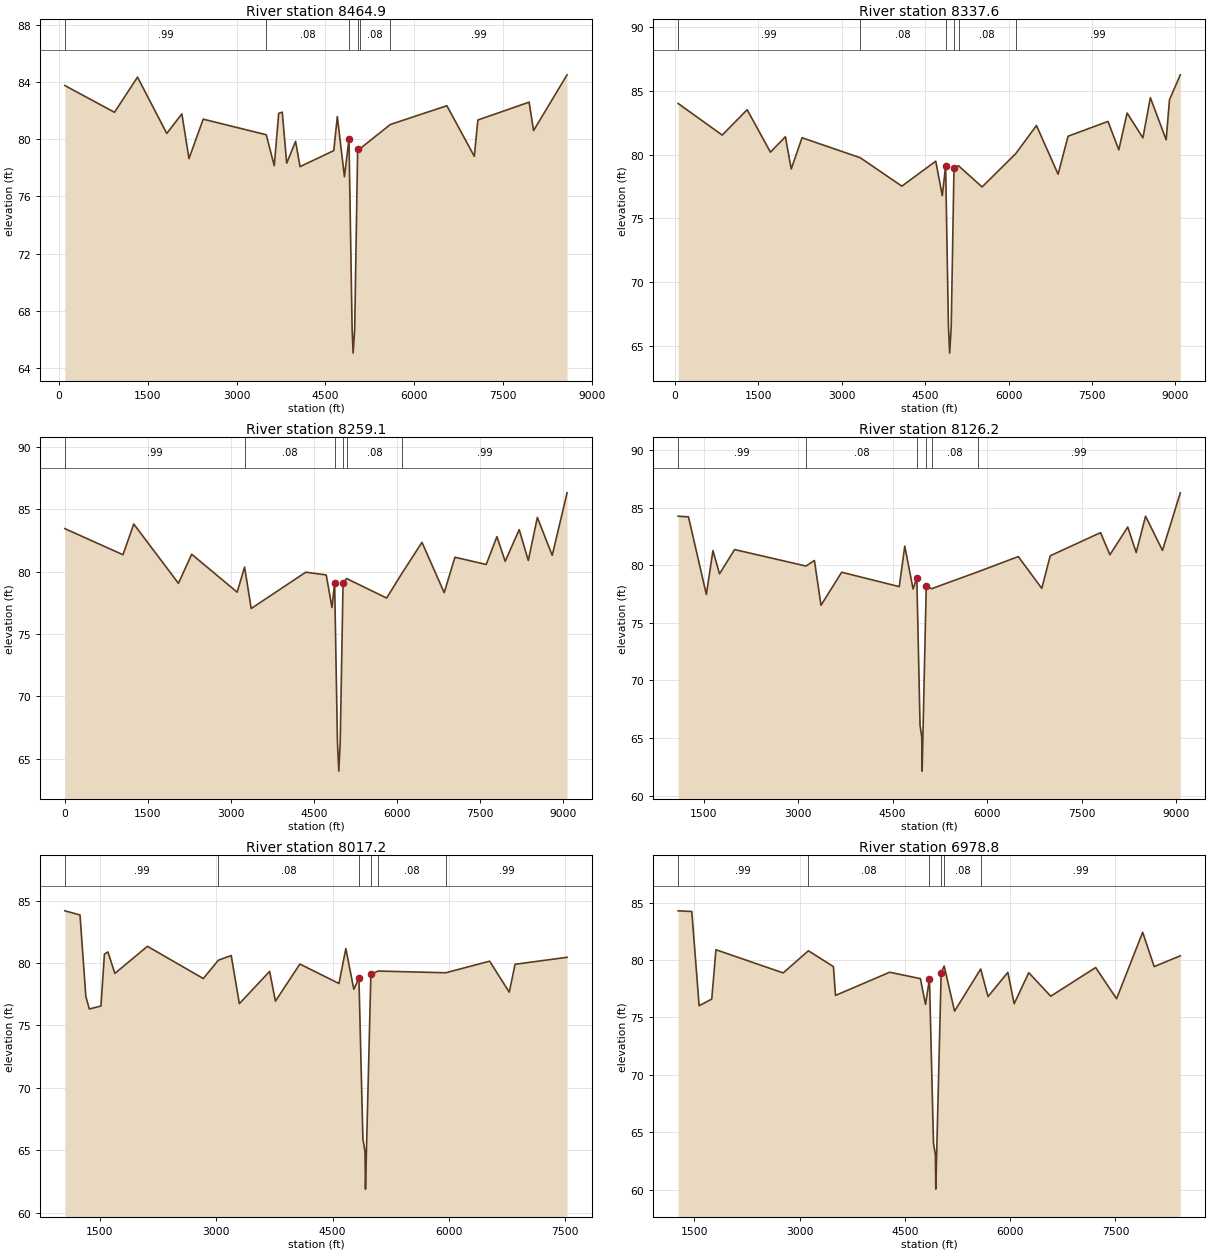
Type RM Length L Ch R = 1 ,8464.9  ,137,127,120
Node Photo=Sta 8464 Looking US.JPG
XS GIS Cut Line= 6
3092488.85000002      13884846.73091067.24000002     13884492.62
3088043.5930630613884675.92064263086286.69000004     13884991.85
3085210.07999998     13885475.37      3084345.98     13886004.14
#Sta/Elev= 30
   101.2   83.75  938.37   81.88 1327.05   84.34 1821.17    80.4 2076.11   81.77
 2196.07   78.64 2436.01    81.4 3500.73   80.31  3635.7   78.14 3710.68    81.8
 3770.66   81.89 3845.64   78.32 3995.61   79.85 4070.59   78.08  4640.4    79.2
 4700.33   81.58  4820.2   77.38 4896.95   79.99 4950.12   66.71 4967.05   65.04
 4993.16   66.71 5043.51   79.29 5074.92   79.31 5596.32   81.03 6549.94   82.34
 7013.06    78.8 7072.82   81.34 7938.27   82.59 8012.76    80.6 8578.87    84.5
#Mann= 6 ,-1 , 0
   101.2     .99       0 3500.73     .08       0 4896.95    .045       0
 5043.51     .04       0 5074.92     .08       0 5596.32     .99       0
Bank Sta=4896.95,5043.51
XS Rating Curve= 0 ,0
Exp/Cntr=0.3,0.1

Type RM Length L Ch R = 1 ,8337.6  ,80,79,78
XS GIS Cut Line= 6
3092428.96000002     13884755.563091007.34000002     13884401.48
3088018.2290267913884477.76410943087506.1925452113884732.9897241
3086226.79000004     13884900.713083897.07000002     13886241.05
#Sta/Elev= 30
   60.76   84.01  853.08   81.53 1301.57   83.52 1720.17   80.19 1989.27    81.4
 2093.93   78.87 2288.28   81.32 3334.81   79.75 4082.34   77.52 4691.93   79.48
 4809.29   76.77 4869.17   79.12 4919.76   66.48  4941.9   64.41 4969.76   66.48
 5019.69   78.96    5101   79.12 5524.83   77.46 6130.96   80.08  6502.2   82.28
 6890.84   78.46 7070.21   81.44 7787.64    82.6 7981.89   80.37 8131.32   83.26
 8415.22   81.31  8549.7   84.46 8833.61   81.16 8893.38   84.31 9087.63   86.26
#Mann= 6 ,-1 , 0
   60.76     .99       0 3334.81     .08       0 4869.17    .045       0
 5019.69     .04       0    5101     .08       0 6130.96     .99       0
Bank Sta=4869.17,5019.69
XS Rating Curve= 0 ,0
Exp/Cntr=0.3,0.1

Type RM Length L Ch R = 1 ,8259.1  ,137,133,134
XS GIS Cut Line= 6
3092445.44000003     13884701.163091020.14999999     13884347.99
3088004.22596513   13884389.51843087442.04000001     13884680.43
       3086200.5     13884847.613083890.20000005     13886228.57
#Sta/Elev= 30
     .19   83.45 1049.04   81.36 1243.83   83.82 2050.92   79.07 2289.83    81.4
 3111.07   78.36 3245.45   80.37 3364.91   77.05  4350.4   79.96 4720.31   79.74
 4823.36   77.13 4871.39    79.1 4922.46   66.33 4947.02   64.02 4972.46   66.33
 5023.46   79.08 5088.33   79.45 5810.68   77.89 6092.66   79.91 6448.97   82.35
 6850.45   78.32 7043.75   81.16  7608.8   80.58 7802.56   82.81 7951.61   80.83
 8204.99   83.37 8368.94    80.9 8532.88   84.35 8801.16   81.31 9069.44   86.32
#Mann= 6 ,-1 , 0
     .19     .99       0 3245.45     .08       0 4871.39    .045       0
 5023.46     .04       0 5088.33     .08       0 6092.66     .99       0
Bank Sta=4871.39,5023.46
XS Rating Curve= 0 ,0
Exp/Cntr=0.3,0.1

Type RM Length L Ch R = 1 ,8126.2  ,102,109,119
Node Photo=Sta 8126 Looking US.JPG
XS GIS Cut Line= 6
3091330.06000003     13884314.65      3090356.73      13884153.7
3088077.1500522513884270.57588953087434.04000005     13884531.96
3086770.74000001     13884526.28      3083879.28      13886219.7
#Sta/Elev= 30
 1091.86   84.27 1256.28   84.21 1540.29   77.47 1644.92   81.28 1749.56   79.26
 1988.72   81.37 3122.73   79.94 3256.99   80.42 3361.42   76.53 3689.64    79.4
 4604.32   78.15 4692.25   81.67 4824.14   77.94 4883.56   78.92 4934.88   66.09
 4961.91   65.09 4967.85   62.12  5033.4   78.22 5117.58   77.97 5855.82   79.44
 6495.47   80.76 6868.37      78 7002.61   80.83 7801.87   82.84 7950.94   80.92
 8234.19   83.33 8368.36   81.12 8517.44   84.27 8785.78    81.3 9069.02    86.3
#Mann= 6 ,-1 , 0
 1091.86     .99       0 3122.73     .08       0 4883.56    .045       0
  5033.4     .04       0 5117.58     .08       0 5855.82     .99       0
Bank Sta=4883.56,5033.4
XS Rating Curve= 0 ,0
Exp/Cntr=0.3,0.1

Type RM Length L Ch R = 1 ,8017.2  ,989,1038,1119
Node Photo=Sta 8017 Looking DS.JPG
XS GIS Cut Line= 6
      3091310.89      13884271.43090350.29000004       13884110.
3088073.4506298313884227.52806543086697.61000003     13884418.68
3085993.31999999     13884700.57      3085130.77     13885338.74
#Sta/Elev= 30
 1048.82   84.18 1243.63   83.85 1318.56   77.34 1363.52   76.32 1513.37   76.56
 1558.33   80.71 1603.29   80.89  1693.2   79.17 2112.88   81.34 2832.84   78.76
 3027.83   80.23 3192.82    80.6 3297.81   76.75 3687.79   79.33 3762.79   76.95
 4077.78   79.92 4582.01   78.36  4670.2   81.16 4773.08    77.9 4838.87   78.78
 4890.39    65.9 4917.39    64.9 4923.39    61.9 4993.17    79.1 5086.26   79.36
 5958.23   79.22 6523.57   80.15 6776.91   77.67 6851.43    79.9 7522.03   80.46
#Mann= 6 ,-1 , 0
 1048.82     .99       0 3027.83     .08       0 4838.87    .045       0
 4993.17     .04       0 5086.26     .08       0 5958.23     .99       0
Bank Sta=4838.87,4993.17
XS Rating Curve= 0 ,0
Exp/Cntr=0.3,0.1

Type RM Length L Ch R = 1 ,6978.8  ,201,191,188
Node Photo=Sta 6978 Looking US .JPG
XS GIS Cut Line= 6
3091326.51000001     13884258.393089433.93999998     13883956.41
3087925.6311627213883538.34175623087609.33000003     13883271.79
      3086012.13     13884285.663085120.35999998     13885325.72
#Sta/Elev= 30
 1267.17   84.29 1461.82   84.23 1566.62   76.02  1746.3    76.6 1806.19    80.9
 2764.44   78.88 3123.79   80.81 3480.55   79.43 3510.23   76.92 4282.08   78.94
 4720.09   78.38 4793.18   76.14 4849.37   78.36 4906.65   64.04 4933.65   63.04
 4939.65   60.04 5016.06   78.89 5059.09   79.48 5207.19   75.55 5579.59   79.22
 5683.87   76.82 5966.89   78.93 6056.27   76.19 6264.81    78.9 6577.63   76.85
 7218.11   79.35 7515.94   76.63 7888.23   82.42 8052.03   79.43 8424.32   80.37
#Mann= 6 ,-1 , 0
 1267.17     .99       0 3123.79     .08       0 4849.37    .045       0
 5016.06     .04       0 5059.09     .08       0 5579.59     .99       0
Bank Sta=4849.37,5016.06
XS Rating Curve= 0 ,0
Exp/Cntr=0.5,0.3

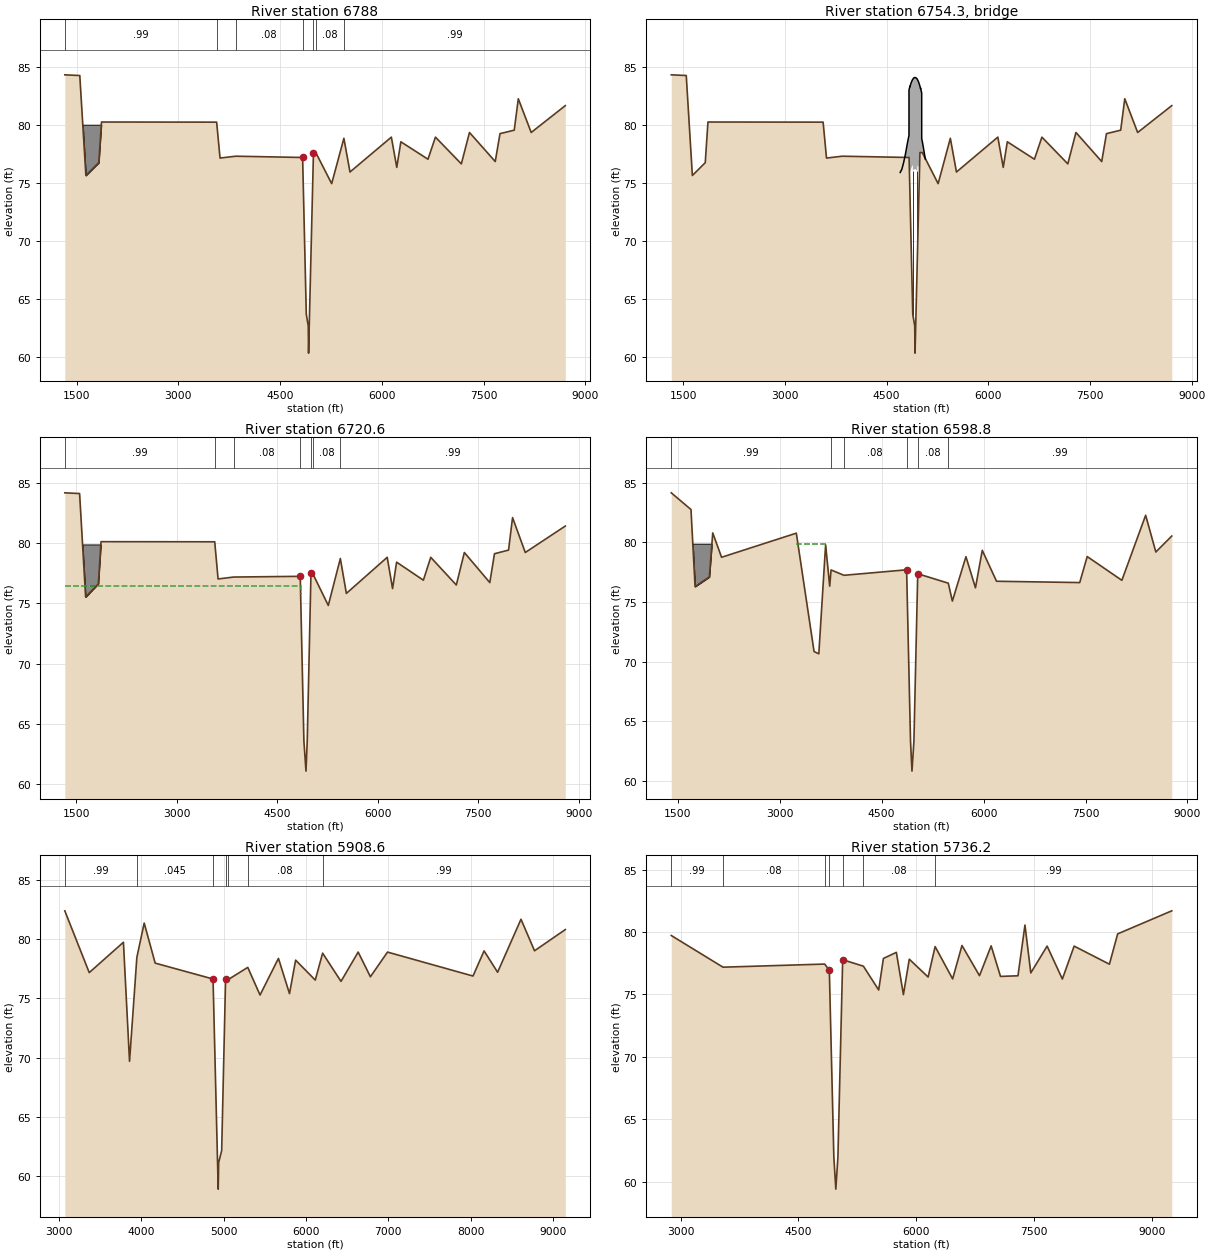
Type RM Length L Ch R = 1 ,6788    ,66,67,66
BEGIN DESCRIPTION:
Upstream Section of Bridge/Culvert/Weir
LONG CREEK DRIVE - XS 3
END DESCRIPTION:
XS GIS Cut Line= 6
      3091341.06       13884244.      3089427.58     13883936.71
      3088240.21     13883503.67      3087674.44     13883167.62
      3086077.23      13884181.5      3085021.59      13885415.2
#Sta/Elev= 30
  1326.3   84.29  1547.1   84.23  1637.1   75.63  1827.1   76.73  1867.1   80.23
  3565.1   80.22  3615.1   77.13  3846.7   77.29 4832.83   77.18  4886.8   63.69
  4915.8   62.69 4920.48   60.35 4992.46    77.6    5027    77.6  5261.1   74.93
  5441.1   78.83  5531.1   75.93  6141.1   78.93  6221.1   76.33  6281.1   78.53
  6681.1   77.03  6791.1   78.93    7173   76.63    7293   79.33    7673   76.83
    7743   79.23    7953   79.53    8013   82.23    8203   79.33  8705.9   81.64
#Mann= 7 ,-1 , 0
  1326.3     .99       0  3565.1    .045       0  3846.7     .08       0
 4832.83    .045       0 4992.46     .04       0    5027     .08       0
  5441.1     .99       0
#XS Ineff= 2 , 0
       0 4831.29   76.78 5015.57       0   74.93
Permanent Ineff=
       F       F
#Block Obstruct= 2 , 0
       0    1900      80               0
Bank Sta=4832.83,4992.46
XS Rating Curve= 0 ,0
Exp/Cntr=0.5,0.3

Type RM Length L Ch R = 3 ,6754.3  ,,,
Node Photo=Long Creek US Face.JPG
BEGIN DESCRIPTION:
LONG CREEK DRIVE
Structure ID: E121-00-00-08
END DESCRIPTION:
Bridge Culvert--1,0,-1,-1, 0
Deck Dist Width WeirC Skew NumUp NumDn MinLoCord MaxHiCord MaxSubmerge Is_Ogee
14,42,2.6,0, 35, 35, , , 0.95, 0, ,,,
 4701.67 4726.67 4751.67 4776.67 4791.67 4801.67 4811.67 4821.67 4831.19 4831.29
 4845.29 4845.39 4861.67 4871.67 4881.67 4888.62 4888.63 4901.67 4911.67 4921.48
 4931.67 4951.67  4954.8 4954.81 4971.67 4991.67 5001.57 5001.67 5018.57 5018.67
 5031.67 5041.67 5051.67 5061.67 5071.67
   75.89   76.18   76.73   77.41   77.88   78.21   78.53   78.82   79.08   82.98
   83.31   83.27   83.58   83.73   83.86   83.92   83.92   84.02   84.06   84.05
   84.05   83.93    83.9    83.9   83.69   83.34   83.12   83.16   82.73   78.82
   78.43    78.1   77.75    77.4   77.06
   50.89   51.18   51.73   52.41   52.88   53.21   53.53   53.82   54.08   57.98
   75.89   75.89    76.2   76.35   76.48   76.55   76.05   76.14   76.18   76.17
   76.17   76.05   76.02   76.52   76.31   75.96   75.75   58.16   57.73   53.82
   53.43    53.1   52.75    52.4   52.06
 4709.12 4734.12 4759.12 4784.12 4799.12 4809.12 4819.12 4829.12 4838.64 4838.74
 4852.74 4852.84 4869.12 4879.12 4889.12 4896.07 4896.08 4909.12 4919.12 4928.93
 4939.12 4959.12 4962.25 4962.26 4979.12 4999.12 5009.02 5009.12 5026.02 5026.12
 5039.12 5049.12 5059.12 5069.12 5079.12
   75.89   76.18   76.73   77.41   77.88   78.21   78.53   78.82   79.08   82.98
   83.31   83.27   83.58   83.73   83.86   83.92   83.92   84.02   84.06   84.05
   84.05   83.93    83.9    83.9   83.69   83.34   83.12   83.16   82.73   78.82
   78.43    78.1   77.75    77.4   77.06
   50.89   51.18   51.73   52.41   52.88   53.21   53.53   53.82   54.08   57.98
   75.89   75.89    76.2   76.35   76.48   76.55   76.05   76.14   76.18   76.17
   76.17   76.05   76.02   76.52   76.31   75.96   75.75   58.16   57.73   53.82
   53.43    53.1   52.75    52.4   52.06
Pier Skew, UpSta & Num, DnSta & Num=  ,4888.63, 4 ,4896.08, 4 , 3 , 3 , 0 ,,
     2.5     2.5    2.75    2.75
   52.45   72.45   72.55   77.05
     2.5     2.5    2.75    2.75
   52.45   72.45   72.55   77.05
Pier Skew, UpSta & Num, DnSta & Num=  ,4954.8, 4 ,4962.25, 4 , 3 , 3 , 0 ,,
     2.5     2.5    2.75    2.75
   52.42   72.42   72.52   77.02
     2.5     2.5    2.75    2.75
   52.42   72.42   72.52   77.02
BR Coef= 1 , 0 , 0 ,0.9, 0 ,,,0.8,-1,1.2,0,
WSPro=,,,, 1 ,,,, 0 ,,,, 0 ,,,,-1 ,-1 ,-1 , 0 , 0 , 0 , 0 , 0
BC Design=,, 0 ,, 0 ,,,,,,
BC HTab HWMax=84.33
BC Use User HTab Curves=0
BC User HTab FreeFlow(D)= 0

Type RM Length L Ch R = 1 ,6720.6  ,104,122,139
BEGIN DESCRIPTION:
Downstream Section of Bridge/Culvert/Weir
LONG CREEK DRIVE - XS 2
END DESCRIPTION:
XS GIS Cut Line= 6
      3091402.51     13884210.05       3089489.5     13883902.84
      3088303.15     13883470.18      3087723.36     13883128.62
      3086050.79     13884164.41       3085006.8     13885410.53
#Sta/Elev= 30
  1326.3   84.19  1547.1   84.13  1637.1   75.53  1827.1   76.63  1867.1   80.13
  3565.1   80.12  3615.1   77.03  3846.7   77.19    4842   77.25 4896.75   63.57
 4927.93   61.06 4946.75   63.57 5002.48    77.5    5027    77.5  5261.1   74.83
  5441.1   78.73  5531.1   75.83  6141.1   78.83  6221.1   76.23  6281.1   78.43
  6681.1   76.93  6791.1   78.83    7173   76.53    7293   79.23    7673   76.73
    7743   79.13    7953   79.43    8013   82.13    8203   79.23  8800.6   81.43
#Mann= 7 ,-1 , 0
  1326.3     .99       0  3565.1    .045       0  3846.7     .08       0
    4842    .045       0 5002.48     .04       0    5027     .08       0
  5441.1     .99       0
#XS Ineff= 2 , 0
       0 4847.74  76.475 5014.02       0   74.93
Permanent Ineff=
       F       F
#Block Obstruct= 2 , 0
       0    1900    79.9               0
Bank Sta=4842,5002.48
XS Rating Curve= 0 ,0
Exp/Cntr=0.5,0.3

Type RM Length L Ch R = 1 ,6598.8  ,785,690,603
BEGIN DESCRIPTION:
Interpolated Channel - LIDAR overbanks
LONG CREEK DRIVE - XS 1
END DESCRIPTION:
XS GIS Cut Line= 6
        3091402.      13884185.5      3089517.25      13883870.5
      3088309.34     13883433.16      3087885.01     13882967.18
      3086095.06     13884073.27      3085184.99     13885181.82
#Sta/Elev= 30
    1405   84.16    1695   82.76    1755    76.3    1965   77.11    2015    80.8
    2145   78.76    3245   80.78  3505.9   70.86  3575.9   70.67  3675.9   79.81
  3735.9   76.34  3755.9    77.7  3945.9   77.25 4867.75   77.71 4925.19   63.35
  4946.6   60.84 4975.19   63.35 5031.32   77.38  5480.8   76.59  5540.8   75.09
  5740.8   78.81  5880.8    76.2  5980.8   79.34  6190.8   76.75  7414.9   76.64
  7524.9   78.82  8034.9   76.83  8384.9   82.28  8534.9    79.2  8769.2   80.54
#Mann= 6 ,-1 , 0
    1405     .99       0  3755.9    .045       0  3945.9     .08       0
 4867.75    .045       0 5031.32     .08       0  5480.8     .99       0
#XS Ineff= 1 ,-1
    3245    3675   79.91
Permanent Ineff=
       F
#Block Obstruct= 2 , 0
       0    2000    79.9               0
Bank Sta=4867.75,5031.32
XS Rating Curve= 0 ,0
Exp/Cntr=0.3,0.1

Type RM Length L Ch R = 1 ,5908.6  ,205,172,140
Node Photo=Sta 5908 Looking DS.JPG
XS GIS Cut Line= 6
3090054.33000001     13882877.983088996.86000003     13882646.66
3088336.8857875913882517.76732193086627.64000003     13883720.34
3086038.69000001     13884025.55      3085089.06     13885274.91
#Sta/Elev= 30
 3072.29   82.38 3368.86   77.17 3784.05   79.73  3858.2   69.69 3947.17   78.45
 4036.14   81.35 4169.71   77.97 4872.33   76.63    4935   58.91 4940.82   61.16
 4977.05   62.16 5024.57   76.61  5057.6   76.59 5294.02   77.61 5443.04   75.28
 5666.58   78.37  5800.7    75.4 5875.21   78.22 6113.64   76.54 6203.03   78.81
 6426.25   76.43 6634.58    78.9 6783.39   76.82 6991.03    78.9 8029.03   76.88
 8163.54      79 8327.95    77.2 8611.92   81.67 8776.32   79.01 9149.97    80.8
#Mann= 7 ,-1 , 0
 3072.29     .99       0 3947.17    .045       0 4872.33    .045       0
 5024.57     .04       0  5057.6    .045       0 5294.02     .08       0
 6203.03     .99       0
Bank Sta=4872.33,5024.57
XS Rating Curve= 0 ,0
Exp/Cntr=0.3,0.1

Type RM Length L Ch R = 1 ,5736.2  ,127,123,119
XS GIS Cut Line= 6
3090141.0292810813882297.91065373088173.2156828813882355.4035659
3088065.52999999     13882551.373087199.48999999     13883219.85
3085851.51000002     13883996.013085019.79000004     13885278.24
#Sta/Elev= 30
 2882.27   79.73 3541.03   77.19 4836.06   77.44 4895.28   76.95 4952.89   61.95
 4977.99   59.39 5004.55   61.95 5065.29   77.79 5329.31   77.27 5524.13   75.36
 5584.08   77.89 5748.93   78.38 5838.85   74.99 5913.78   77.83 6153.57    76.4
 6242.91   78.84 6465.97   76.25 6584.93   78.93 6807.99   76.51  6956.6    78.9
 7075.37   76.45 7298.07    76.5 7387.15   80.57 7461.39   76.73 7669.24   78.88
 7863.48   76.24 8013.32   78.88 8462.84   77.43 8567.73   79.86 9256.98   81.71
#Mann= 7 ,-1 , 0
 2882.27     .99       0 3541.03     .08       0 4836.06    .045       0
 4895.28    .045       0 5065.29    .045       0 5329.31     .08       0
 6242.91     .99       0
Bank Sta=4895.28,5065.29
XS Rating Curve= 0 ,0
Exp/Cntr=0.3,0.1

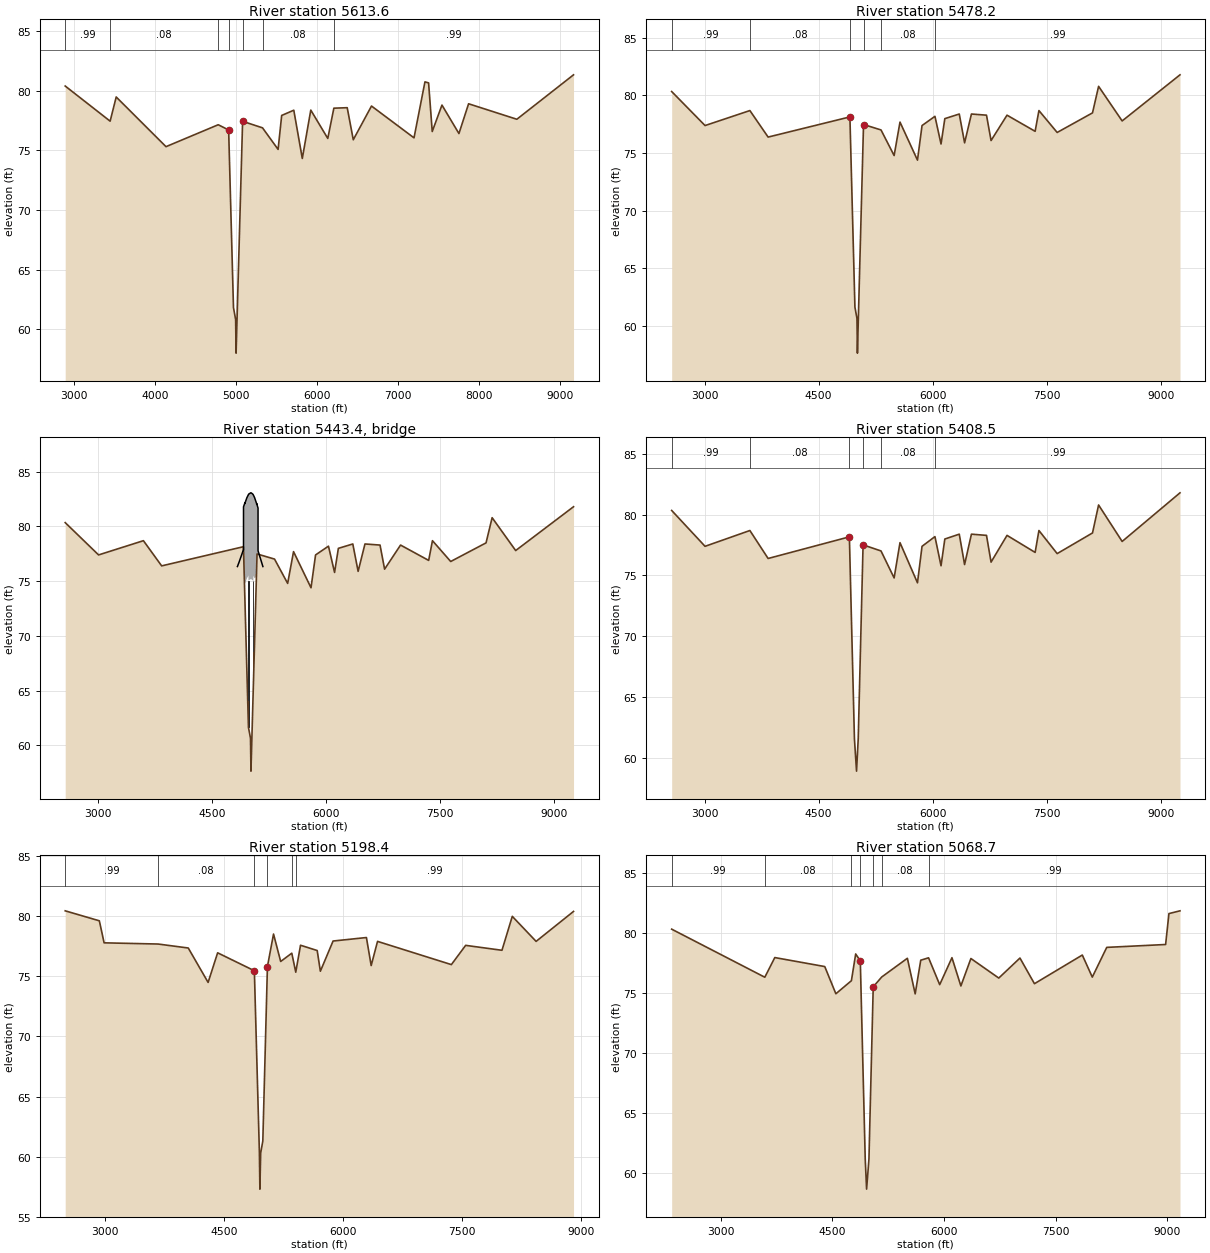
Type RM Length L Ch R = 1 ,5613.6  ,163,135,139
XS GIS Cut Line= 6
3090018.26999998     13882075.823088053.71000004     13882304.33
3087582.88000003     13882832.673086664.79000002     13883505.82
3085801.29000002     13883957.29      3085050.09     13885207.47
#Sta/Elev= 30
 2889.95   80.41 3444.33   77.46 3519.25   79.49 4133.57   75.32 4777.86   77.16
 4906.54   76.72 4966.19   61.81 4992.76   60.81 4998.39   57.99  5078.8   77.45
  5324.5    76.9 5516.67   75.09 5561.01   77.94 5710.41   78.38 5815.27   74.33
 5920.12   78.39 6129.83   76.01 6204.73   78.55  6369.5   78.59 6444.39    75.9
 6669.08   78.73 7193.71   76.06 7328.63   80.76  7373.6   80.67 7418.57   76.59
  7538.5   78.81 7748.05   76.42 7867.11   78.92 8462.42   77.62 9161.91   81.35
#Mann= 7 ,-1 , 0
 2889.95     .99       0 3444.33     .08       0 4777.86    .045       0
 4906.54    .045       0  5078.8    .045       0  5324.5     .08       0
 6204.73     .99       0
Bank Sta=4906.54,5078.8
XS Rating Curve= 0 ,0
Exp/Cntr=0.5,0.3

Type RM Length L Ch R = 1 ,5478.2  ,74,70,65
BEGIN DESCRIPTION:
Upstream Section of Bridge/Culvert/Weir
MAPLE TREE - XS 3
END DESCRIPTION:
XS GIS Cut Line= 6
      3090020.65     13881543.96      3087908.39     13882094.37
       3087538.6      13882793.6      3086620.52     13883466.76
      3085708.54     13883889.26      3085011.89      13885263.3
#Sta/Elev= 30
  2566.1   80.34  3005.4   77.39  3595.4   78.69  3835.4   76.39 4911.67   78.14
 4977.61   61.65 5004.61   60.65 5010.61   57.65 5090.93   77.48    5321   77.01
  5493.6   74.79  5570.9   77.69  5800.9   74.39  5860.9   77.39  6030.8   78.19
  6110.9   75.79  6160.9   77.99  6350.9   78.39  6420.9   75.89  6510.9   78.39
  6709.3   78.29  6769.3   76.09  6979.3   78.29  7349.3   76.89  7399.3   78.69
  7639.3   76.79  8104.4   78.49  8184.4   80.79  8494.4   77.79  9255.7   81.79
#Mann= 6 ,-1 , 0
  2566.1     .99       0  3595.4     .08       0 4911.67    .045       0
 5090.93    .045       0    5321     .08       0  6030.8     .99       0
#XS Ineff= 2 , 0
       0 4916.52   76.89 5099.82       0   76.89
Permanent Ineff=
       F       F
Bank Sta=4911.67,5090.93
XS Rating Curve= 0 ,0
Exp/Cntr=0.5,0.3

Type RM Length L Ch R = 3 ,5443.4  ,,,
BEGIN DESCRIPTION:
MAPLE TREE; inverted slope
Structure ID: E121-00-00-06
END DESCRIPTION:
Bridge Culvert--1,0,-1,-1, 0
Deck Dist Width WeirC Skew NumUp NumDn MinLoCord MaxHiCord MaxSubmerge Is_Ogee
14,38,2.6,0, 27, 27, , , 0.95, 0, ,,,
 4832.44 4857.44 4882.44 4907.44 4912.42 4912.52 4929.52 4929.62 4932.44 4957.44
 4977.37 4977.47 4982.44 5007.44 5012.44 5032.44 5042.22 5042.32 5057.44 5082.44
 5086.82 5086.92 5103.82 5103.92 5107.44 5157.44 5167.44
   76.33   76.79   77.29   77.78   77.88   81.78   82.12   82.08   82.14   82.62
    82.9    82.9   82.95   83.06   83.06   82.96   82.86   82.86   82.64   82.13
   82.02   82.06   81.67   77.77   77.69   76.56   76.33
   51.33   51.79   52.29   52.78   52.88   56.78    74.7    74.7   74.76   75.24
   75.52   75.02   75.07   75.18   75.18   75.08   74.98   75.48   75.26   74.75
   74.65   57.06   56.67   52.77   52.69   51.56   51.33
 4819.96 4844.96 4869.96 4894.96 4899.94 4900.04 4917.04 4917.14 4919.96 4944.96
 4964.89 4964.99 4969.96 4994.96 4999.96 5019.96 5029.74 5029.84 5044.96 5069.96
 5074.34 5074.44 5091.34 5091.44 5094.96 5144.96 5154.96
   76.33   76.79   77.29   77.78   77.88   81.78   82.12   82.08   82.14   82.62
    82.9    82.9   82.95   83.06   83.06   82.96   82.86   82.86   82.64   82.13
   82.02   82.06   81.67   77.77   77.69   76.56   76.33
   51.33   51.79   52.29   52.78   52.88   56.78    74.7    74.7   74.76   75.24
   75.52   75.02   75.07   75.18   75.18   75.08   74.98   75.48   75.26   74.75
   74.65   57.06   56.67   52.77   52.69   51.56   51.33
Pier Skew, UpSta & Num, DnSta & Num=  ,4977.47, 4 ,4964.99, 4 , 3 , 3 , 0 ,,
     2.5     2.5    2.75    2.75
   51.42   71.42   71.52   76.02
     2.5     2.5    2.75    2.75
   51.42   71.42   71.52   76.02
Pier Skew, UpSta & Num, DnSta & Num=  ,5042.22, 4 ,5029.74, 4 , 3 , 3 , 0 ,,
     2.5     2.5    2.75    2.75
   51.38   71.38   71.48   75.98
     2.5     2.5    2.75    2.75
   51.38   71.38   71.48   75.98
BR Coef= 1 , 0 , 0 ,0.9, 0 ,,,0.8,0,1.2,0,
WSPro=,,,, 1 ,,,, 0 ,,,, 0 ,,,,-1 ,-1 ,-1 , 0 , 0 , 0 , 0 , 0
BC Design=,, 0 ,, 0 ,,,,,,
BC HTab HWMax=81.69
BC Use User HTab Curves=0
BC User HTab FreeFlow(D)= 0

Type RM Length L Ch R = 1 ,5408.5  ,181,210,210
BEGIN DESCRIPTION:
Downstream Section of Bridge/Culvert/Weir
MAPLE TREE - XS 2
END DESCRIPTION:
XS GIS Cut Line= 6
      3089967.48     13881507.25      3087851.68     13882058.58
      3087483.24     13882758.07      3086566.06     13883430.56
       3085652.9     13883853.61      3084982.74      13885251.7
#Sta/Elev= 30
  2566.1   80.34  3005.4   77.39  3595.4   78.69  3835.4   76.39 4904.77   78.17
 4971.21   61.56 4998.96    58.9 5021.21   61.56    5085   77.51    5321   77.01
  5493.6   74.79  5570.9   77.69  5800.9   74.39  5860.9   77.39  6030.8   78.19
  6110.9   75.79  6160.9   77.99  6350.9   78.39  6420.9   75.89  6510.9   78.39
  6709.3   78.29  6769.3   76.09  6979.3   78.29  7349.3   76.89  7399.3   78.69
  7639.3   76.79  8104.4   78.49  8184.4   80.79  8494.4   77.79  9255.7   81.79
#Mann= 6 ,-1 , 0
  2566.1     .99       0  3595.4     .08       0 4904.77    .045       0
    5085    .045       0    5321     .08       0  6030.8     .99       0
#XS Ineff= 2 , 0
       0 4912.04  76.035 5079.34       0  76.035
Permanent Ineff=
       F       F
Bank Sta=4904.77,5085
XS Rating Curve= 0 ,0
Exp/Cntr=0.5,0.3

Type RM Length L Ch R = 1 ,5198.4  ,129,130,130
Node Photo=Sta 5198 Looking DS.JPG
BEGIN DESCRIPTION:
Interpolated Channel - LIDAR overbanks
MAPLE TREE - XS 1 and GOLF CART BRIDGE - XS 4
END DESCRIPTION:
XS GIS Cut Line= 5
      3089974.41     13881497.26       3087723.6     13882035.67
      3087603.27     13882321.07      3085622.58     13883758.42
       3085101.7     13884983.66
#Sta/Elev= 30
  2500.8   80.44  2930.8   79.61  2990.8   77.78  3670.8   77.68  4050.8   77.35
  4300.8   74.49  4420.8   76.95 4883.32   75.46 4946.92   60.31 4952.92   57.31
 4962.92   60.31 4989.92   61.31 5047.93   75.81  5124.8   78.51  5214.8   76.23
  5354.8   76.92  5404.8   75.34  5464.8   77.58  5674.8   77.14  5714.8   75.42
  5874.8   77.93  6294.8   78.22  6354.8   75.89  6434.8    77.9  7364.8   75.97
  7544.8   77.57  8002.1   77.16  8132.1   79.98  8432.1    77.9  8903.5   80.39
#Mann= 6 ,-1 , 0
  2500.8     .99       0  3670.8     .08       0 4883.32    .045       0
 5047.93    .045       0  5354.8     .08       0  5404.8     .99       0
Bank Sta=4883.32,5047.93
XS Rating Curve= 0 ,0
Exp/Cntr=0.3,0.1

Type RM Length L Ch R = 1 ,5068.7  ,34,34,33
XS GIS Cut Line= 6
3090029.10999998     13881482.223087659.88000004     13881953.75
 3087594.768951413882010.32168663087497.09000003     13882236.66
3085541.85000001     13883724.57      3084979.17     13885249.91
#Sta/Elev= 30
 2338.48   80.33 3590.35   76.32 3724.65   77.96 4396.12   77.21 4545.33   74.94
 4754.23   76.03 4811.74   78.26 4873.85   77.68 4939.98   61.15 4958.47   58.64
 4989.99   61.15 5047.48   75.52 5161.91   76.34 5506.49    77.9 5611.37   74.93
 5686.27   77.74 5791.15   77.94 5940.96    75.7 6105.76   77.95 6225.61   75.59
 6360.45   77.88    6735   76.25 7019.65   77.92 7214.42   75.78 7857.58   78.17
 7991.96   76.33 8186.06   78.81 8977.41   79.05 9022.07   81.63 9170.68   81.86
#Mann= 7 ,-1 , 0
 2338.48     .99       0 3590.35     .08       0 4754.23    .045       0
 4873.85    .045       0 5047.48    .045       0 5161.91     .08       0
 5791.15     .99       0
Bank Sta=4873.85,5047.48
XS Rating Curve= 0 ,0
Exp/Cntr=0.3,0.1

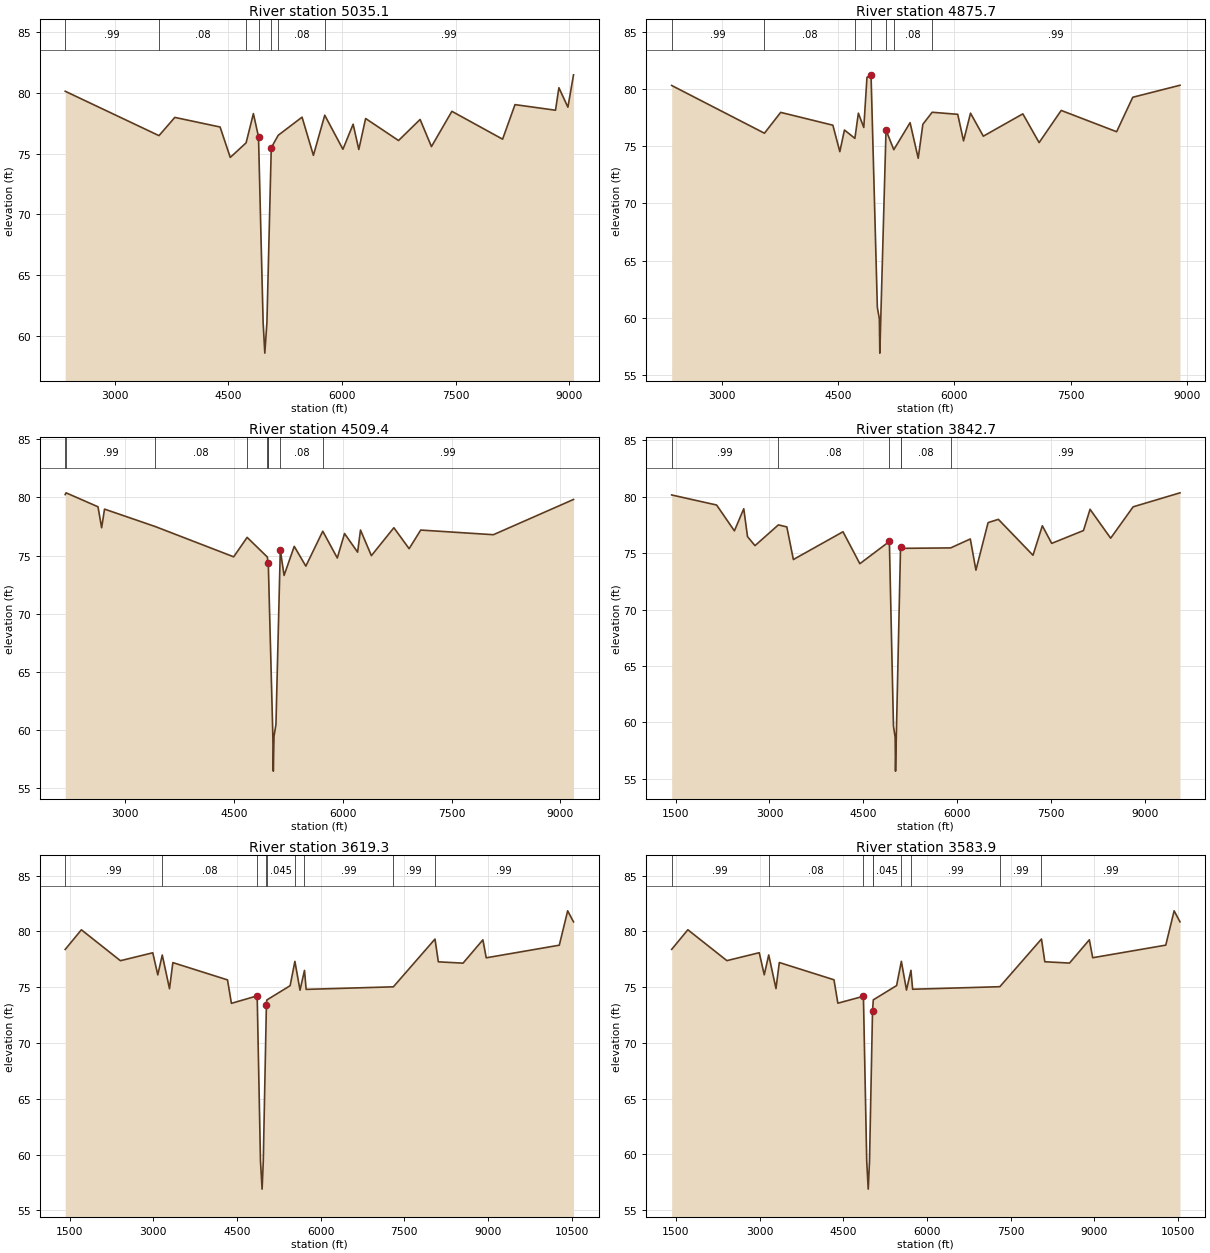
Type RM Length L Ch R = 1 ,5035.1  ,135,159,187
XS GIS Cut Line= 6
3090004.66000003     13881460.993087633.07000001       13881933.
3087564.0409114713881994.95766673087469.70000003     13882216.97
3085514.05000003     13883705.193085010.42000003      13885119.2
#Sta/Elev= 30
 2347.18   80.12 3585.29   76.47 3794.41   77.97 4391.91   77.18 4526.34   74.68
 4735.47   75.88  4831.6   78.28 4899.06   76.38 4960.11   61.11 4982.31   58.59
 5010.11   61.11 5067.58   75.48 5159.26    76.5 5473.95   77.99  5623.8   74.85
 5773.64   78.15  6013.4   75.35 6148.27   77.41 6223.19   75.33  6313.1   77.88
 6747.66   76.07 7032.37    77.8 7182.22   75.57 7451.95   78.47 8121.59   76.18
 8285.07   79.02  8820.1   78.56 8864.68   80.41 8983.58   78.81 9057.89   81.47
#Mann= 7 ,-1 , 0
 2347.18     .99       0 3585.29     .08       0 4735.47    .045       0
 4899.06    .045       0 5067.58    .045       0 5159.26     .08       0
 5773.64     .99       0
Bank Sta=4899.06,5067.58
XS Rating Curve= 0 ,0
Exp/Cntr=0.3,0.1

Type RM Length L Ch R = 1 ,4875.7  ,352,366,382
XS GIS Cut Line= 6
3089978.50000001     13881453.433087597.01000004      13881902.7
3087477.0334393113881932.07068913087323.57000002     13882080.65
3085454.15000002     13883655.713085058.95000003     13884964.84
#Sta/Elev= 30
  2353.3    80.3 3550.09   76.13 3759.53   77.95 4432.72   76.83 4522.48   74.52
 4582.32   76.41 4716.96   75.68 4761.84   77.88  4831.7   76.63 4872.87   81.01
 4925.34   81.23 5006.61   60.92 5032.55   59.92 5038.55   56.92 5118.54    76.4
  5218.9   74.69 5428.85   77.05 5533.83   73.94 5593.82   76.91 5713.79   77.96
 6043.72   77.78 6118.71   75.46 6208.69   77.88 6373.65   75.87 6883.55   77.82
 7093.51   75.31 7378.46   78.12 8093.52   76.26 8301.61   79.27 8911.02   80.32
#Mann= 7 ,-1 , 0
  2353.3     .99       0 3550.09     .08       0 4716.96    .045       0
 4925.34    .045       0 5118.54    .045       0  5218.9     .08       0
 5713.79     .99       0
Bank Sta=4925.34,5118.54
XS Rating Curve= 0 ,0
Exp/Cntr=0.3,0.1

Type RM Length L Ch R = 1 ,4509.4  ,614,667,720
BEGIN DESCRIPTION:
Cross Section X04
END DESCRIPTION:
XS GIS Cut Line= 6
       3089991.8     13881446.52      3087569.92     13881495.03
      3087219.01     13881696.13       3086780.4     13881962.95
      3085400.57     13883613.64      3085019.45     13885079.61
#Sta/Elev= 30
  2173.8   80.25  2185.9    80.4  2625.9    79.2  2675.9    77.4  2715.9      79
  3415.9    77.5  4495.9    74.9  4681.4   76.57  4960.3   74.88  4968.8   74.34
 4973.05   74.34 5035.98   59.48 5041.98   56.48 5052.01   59.48  5078.5   60.48
 5138.55   75.49  5190.6    73.3  5330.6    75.8  5490.6    74.1    5724    77.1
    5924    74.8    6024    76.9    6204    75.3    6244    77.2    6394      75
    6704    77.4    6914    75.6    7074    77.2  8075.4    76.8  9180.2   79.83
#Mann= 9 ,-1 , 0
  2173.8     .99       0  2185.9     .99       0  3415.9     .08       0
  4681.4    .045       0  4960.3     .04       0  4968.8     .04       0
 4973.05    .045       0 5138.55     .08       0    5724     .99       0
Bank Sta=4973.05,5138.55
XS Rating Curve= 0 ,0
Exp/Cntr=0.3,0.1

Type RM Length L Ch R = 1 ,3842.7  ,201,223,244
Node Photo=Sta 3842 Looking DS.JPG
XS GIS Cut Line= 5
3090512.03000005     13881426.233087538.73000005     13881230.12
3086671.36000001      13881060.73085358.00999999      13883598.7
3085041.66000004     13884971.29
#Sta/Elev= 30
 1436.06   80.15  2154.8   79.26  2439.3   76.97 2589.03   78.93 2648.93   76.46
 2768.72   75.66 3143.06    77.5 3277.82   77.32 3382.64   74.43 4176.24   76.89
 4445.77   74.06 4917.84   76.03 4983.23   59.68 5010.29   58.68 5016.29   55.68
 5096.55   75.51 5104.85   75.42 5898.05   75.46 6212.25   76.25 6302.02   73.49
 6496.53    77.7 6661.11   77.99  7214.7   74.81 7364.32   77.42 7513.94   75.86
 8022.64      77 8127.38   78.88    8457   76.32 8816.63    79.1 9565.88   80.34
#Mann= 6 ,-1 , 0
 1436.06     .99       0 3143.06     .08       0 4917.84    .045       0
 5096.55     .04       0 5104.85     .08       0 5898.05     .99       0
Bank Sta=4917.84,5096.55
XS Rating Curve= 0 ,0
Exp/Cntr=0.3,0.1

Type RM Length L Ch R = 1 ,3619.3  ,35,35,36
BEGIN DESCRIPTION:
Upstream Section of Bridge/Culvert/Weir
GOLF CART BRIDGE - XS 3
(Ineffective Deleted-Atkins)
END DESCRIPTION:
XS GIS Cut Line= 6
      3090496.41     13881366.34      3087523.11     13881170.23
      3086992.67     13880883.87       3086416.1     13880636.28
      3085301.82     13883526.58      3084962.81     13885299.56
#Sta/Elev= 30
  1422.2   78.39  1712.2   80.15  2412.2   77.38  2992.2   78.09  3082.2   76.11
  3162.2   77.89  3292.2   74.87  3352.2   77.21  4332.2   75.66    4402   73.56
 4864.15   74.23  4923.4   59.41 4952.21   56.91  4973.4   59.41 5029.56   73.45
 5036.99   73.86  5454.8   75.14  5540.1   77.32  5632.2   74.74  5712.2   76.51
  5742.2   74.81    7306   75.04  8052.2   79.32  8112.2   77.28  8554.5   77.16
  8910.7   79.25  8970.7   77.64 10280.7   78.77 10430.7   81.85 10535.8   80.86
#Mann= 9 ,-1 , 0
  1422.2     .99       0  3162.2     .08       0 4864.15    .045       0
 5029.56     .04       0 5036.99    .045       0  5540.1     .08       0
  5712.2     .99       0    7306     .99       0  8052.2     .99       0
Bank Sta=4864.15,5029.56
XS Rating Curve= 0 ,0
Exp/Cntr=0.3,0.1

Type RM Length L Ch R = 1 ,3583.9  ,116,113,111
BEGIN DESCRIPTION:
Downstream Section of Bridge/Culvert/Weir
GOLF CART BRIDGE - XS 2
(Ineffective Deleted-Atkins)
END DESCRIPTION:
XS GIS Cut Line= 6
      3090508.27     13881333.09      3087536.06     13881137.05
      3087006.38      13880851.1      3086427.96     13880602.92
      3085300.42     13883526.06      3084966.18     13885269.87
#Sta/Elev= 30
  1422.2   78.39  1712.2   80.15  2412.2   77.38  2992.2   78.09  3082.2   76.11
  3162.2   77.89  3292.2   74.87  3352.2   77.21  4332.2   75.66    4402   73.56
 4860.03   74.18 4919.25   59.37  4946.3   56.87 4969.25   59.37 5023.12   72.84
 5036.99   73.86  5454.8   75.14  5540.1   77.32  5632.2   74.74  5712.2   76.51
  5742.2   74.81    7306   75.04  8052.2   79.32  8112.2   77.28  8554.5   77.16
  8910.7   79.25  8970.7   77.64 10280.7   78.77 10430.7   81.85 10535.8   80.86
#Mann= 9 ,-1 , 0
  1422.2     .99       0  3162.2     .08       0 4860.03    .045       0
 5023.12     .04       0 5036.99    .045       0  5540.1     .08       0
  5712.2     .99       0    7306     .99       0  8052.2     .99       0
Bank Sta=4860.03,5023.12
XS Rating Curve= 0 ,0
Exp/Cntr=0.3,0.1