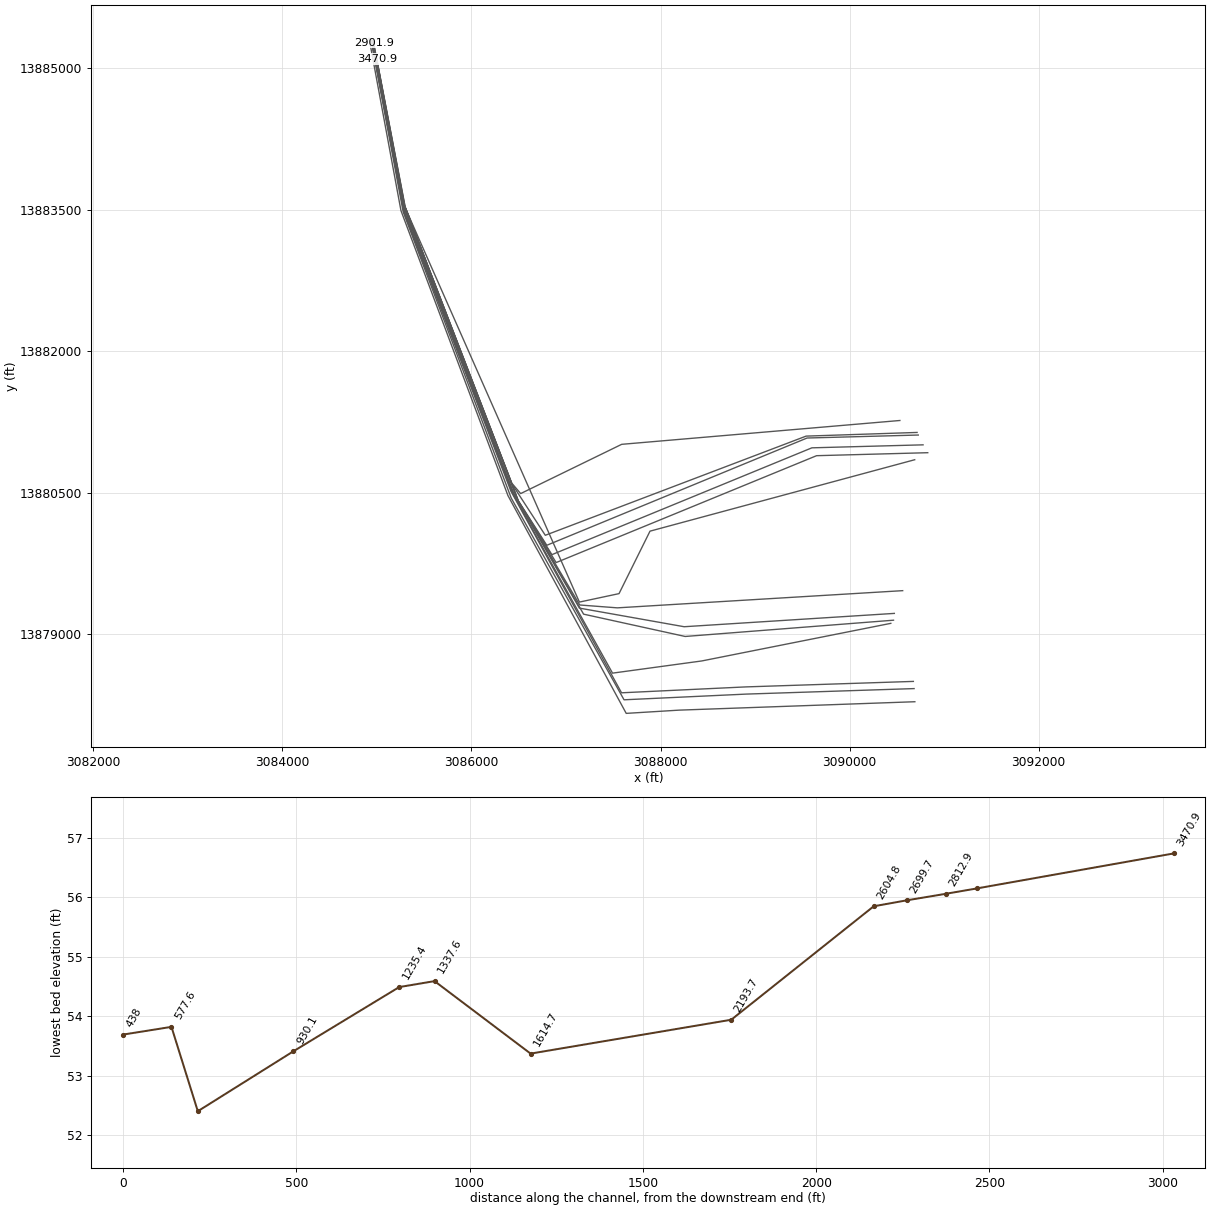
HEC-RAS study E121-00-00.prj: E121-00-00 LOMR

--- E121-00-00.g01 (geometry) --- (continued)

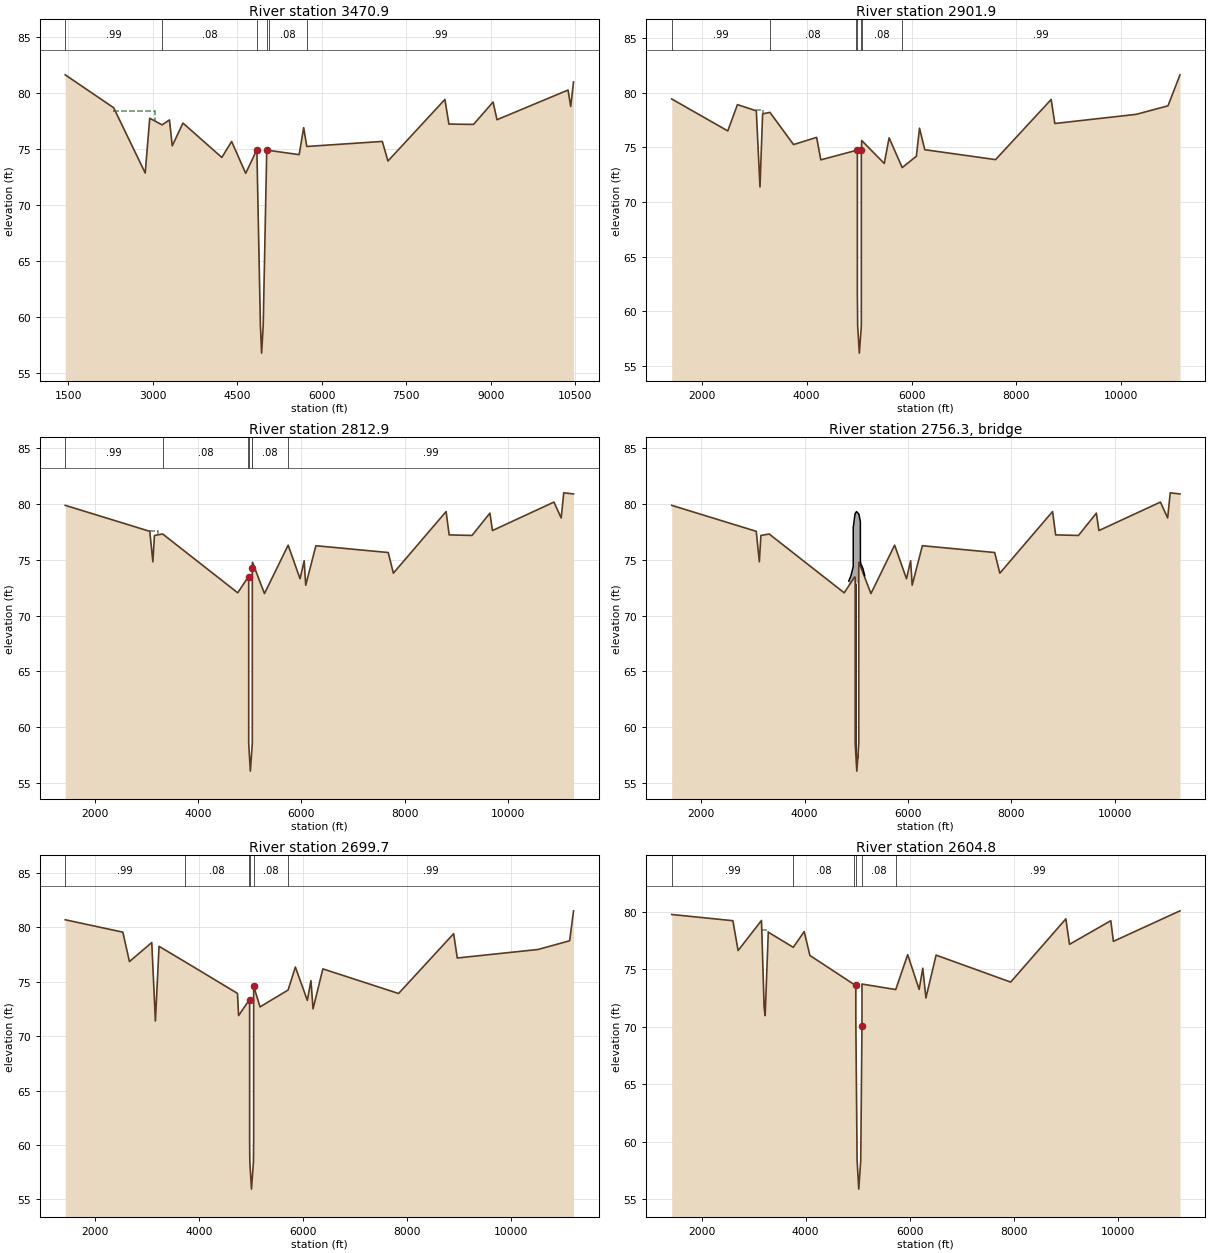
Type RM Length L Ch R = 1 ,3470.9  ,581,569,560
BEGIN DESCRIPTION:
Interpolated Channel - LIDAR overbanks
GOLF CART BRIDGE - XS 1
END DESCRIPTION:
XS GIS Cut Line= 6
      3090531.71     13881265.38      3087589.13      13881012.7
      3086520.86     13880490.78       3086426.3     13880601.25
      3085299.81     13883527.09      3084998.61     13885096.77
#Sta/Elev= 30
  1446.4    81.6  2306.4   78.66  2866.4   72.83  2946.4   77.72  3166.4   77.13
  3296.4   77.57  3346.4   75.26  3536.4   77.29  4226.4   74.22  4399.8   75.65
  4649.8    72.8 4847.98   74.91 4910.68   59.24  4932.1   56.74 4960.68   59.24
 5023.15   74.85  5059.8   74.85  5598.8   74.47  5678.8   76.88  5734.2    75.2
  7074.4   75.65  7174.4    73.9  8185.2    79.4  8256.5    77.2  8693.7   77.17
  9039.8   79.17  9109.8   77.59 10370.4   80.24 10418.1   78.77 10468.1   80.96
#Mann= 6 ,-1 , 0
  1446.4     .99       0  3166.4     .08       0 4847.98    .045       0
 5023.15     .04       0  5059.8     .08       0  5734.2     .99       0
#XS Ineff= 1 ,-1
    2295    3047    78.4
Permanent Ineff=
       F
Bank Sta=4847.98,5023.15
XS Rating Curve= 0 ,0
Exp/Cntr=0.3,0.1

Type RM Length L Ch R = 1 ,2901.9  ,88,89,90
BEGIN DESCRIPTION:
Interpolated Channel - LIDAR overbanks
VICTORY - XS 4
END DESCRIPTION:
XS GIS Cut Line= 6
      3090713.67     13881138.72      3089540.11     13881099.83
      3086781.24     13880048.55      3086427.51     13880594.62
      3085295.99      13883535.6      3084964.85     13885269.81
#Sta/Elev= 30
  1426.1   79.44  2496.1   76.51  2680.3   78.92  3040.3   78.35  3110.3   71.37
  3160.3   78.07  3300.3   78.21  3750.3   75.26  4190.3   75.92  4270.3   73.86
  4940.3   74.72 4967.18   74.72 4967.19   61.65 4973.19   58.65 5005.19   56.15
 5043.19   58.65  5043.2   74.72  5050.3   75.63  5480.3   73.53  5572.7   75.88
  5822.7   73.15  6092.7   74.19  6152.7   76.76  6253.3   74.79  7603.3   73.88
  8663.3   79.39  8733.3   77.19 10286.1   78.03 10891.4   78.81 11120.3   81.65
#Mann= 7 ,-1 , 0
  1426.1     .99       0  3300.3     .08       0  4940.3     .04       0
 4967.18    .015       0  5043.2     .04       0  5050.3     .08       0
  5822.7     .99       0
#XS Ineff= 1 ,-1
    3040    3161    78.4
Permanent Ineff=
       F
Bank Sta=4967.18,5043.2
XS Rating Curve= 0 ,0
Exp/Cntr=0.5,0.3

Type RM Length L Ch R = 1 ,2812.9  ,114,113,113
BEGIN DESCRIPTION:
Upstream Section of Bridge/Culvert/Weir
VICTORY - XS 3
END DESCRIPTION:
XS GIS Cut Line= 6
      3090726.44      13881111.2      3089549.77     13881079.57
      3086796.94     13879942.55      3086496.93     13880411.77
      3085291.27     13883545.43      3084960.57     13885283.31
#Sta/Elev= 30
  1426.5   79.88  3063.6   77.55  3123.6   74.82  3153.6   77.18  3313.6   77.31
    4766   72.04  4965.4   73.44 4978.33   73.44 4978.34   58.56 5010.34   56.06
 5048.34   58.56 5048.35   74.26  5051.1   74.78  5283.6   71.97    5742   76.31
    5972    73.3    6052   74.91    6082   72.72  6278.9   76.26  7678.9   75.65
  7778.9    73.8  8798.9   79.32  8858.9   77.23  9300.5   77.18  9646.8   79.18
  9696.8   77.62 10886.8   80.17 11026.8   78.75 11076.8      81 11265.8    80.9
#Mann= 7 ,-1 , 0
  1426.5     .99       0  3313.6     .08       0  4965.4     .04       0
 4978.33    .015       0 5048.35     .04       0  5051.1     .08       0
    5742     .99       0
#XS Ineff= 3 ,-1
  3041.9  3223.6   77.55    4900 4975.05   72.04 5051.75    5100   72.97
Permanent Ineff=
       F       F       F
Bank Sta=4978.33,5048.35
XS Rating Curve= 0 ,0
Exp/Cntr=0.5,0.3

Type RM Length L Ch R = 3 ,2756.3  ,,,
Node Photo=Victory Looking US.JPG
BEGIN DESCRIPTION:
VICTORY
Structure ID: E121-00-00-3
END DESCRIPTION:
Bridge Culvert--1,0,-1,-1, 0
Deck Dist Width WeirC Skew NumUp NumDn MinLoCord MaxHiCord MaxSubmerge Is_Ogee
1,93,2.6,0, 15, 15, , , 0.95, 0, ,,,
 4854.75 4897.75 4941.25 4941.35 4944.85 4975.95 4976.05 5003.65 5050.75 5050.85
 5079.25 5079.35 5089.55 5127.25 5162.75
   73.09   73.59   74.41   77.96   78.03   79.12   79.12   79.32   79.09   79.09
    78.4   74.85   74.61   74.24   73.58
   48.09   48.59   49.41   52.96   53.03   54.12    72.8      73   72.78   54.09
    53.4   49.85   49.61   49.24   48.58
 4858.37 4901.37 4944.87 4944.97 4948.47 4979.57 4979.67 5007.27 5054.37 5054.47
 5082.87 5082.97 5093.17 5130.87 5166.37
   73.09   73.59   74.41   77.96   78.03   79.12   79.12   79.32   79.09   79.09
    78.4   74.85   74.61   74.24   73.58
   48.09   48.59   49.41   52.96   53.03   54.12    72.8      73   72.78   54.09
    53.4   49.85   49.61   49.24   48.58
Pier Skew, UpSta & Num, DnSta & Num=  ,4998.25, 4 ,5001.87, 4 , 3 , 3 , 0 ,,
     1.5     1.5     2.3     2.3
   50.56   70.56   70.66   73.96
     1.5     1.5     2.3     2.3
   50.56   70.56   70.66   73.96
Pier Skew, UpSta & Num, DnSta & Num=  ,5028.55, 4 ,5032.17, 4 , 3 , 3 , 0 ,,
     1.5     1.5     2.3     2.3
   50.48   70.48   70.58   73.88
     1.5     1.5     2.3     2.3
   50.48   70.48   70.58   73.88
BR Coef= 1 , 1 , 0 ,1.25, 0 ,,,0.8,-1,2,0,
WSPro=,,,, 1 ,,,, 0 ,,,, 0 ,,,,-1 ,-1 ,-1 , 0 , 0 , 0 , 0 , 0
BC Design=,, 0 ,, 0 ,,,,,,
BC HTab HWMax=81.8
BC Use User HTab Curves=0
BC User HTab FreeFlow(D)= 0

Type RM Length L Ch R = 1 ,2699.7  ,97,95,95
BEGIN DESCRIPTION:
Downstream Section of Bridge/Culvert/Weir
VICTORY - XS 2
END DESCRIPTION:
XS GIS Cut Line= 6
        3090777.     13881007.27       3089601.2     13880975.66
      3086850.97     13879843.25      3086496.15     13880410.56
      3085289.29     13883546.69      3084990.76     13885123.12
#Sta/Elev= 30
  1428.5   80.68  2538.5   79.54  2664.7   76.84  3094.7   78.59  3164.7   71.38
  3234.7   78.24  3724.7   76.85  4744.7   73.92    4766   71.88  4965.4   73.28
 4978.01   73.28 4978.02   60.45 4982.02   58.45 5014.02   55.95 5052.02   58.45
 5056.02   60.45 5056.03   74.59  5178.7   72.68    5719   74.23    5859   76.34
    6089   73.28    6159   75.09    6199    72.5  6388.1   76.17  7845.2   73.91
  8905.2    79.4  8975.2   77.17 10528.5   77.95 11138.5   78.75   11213    81.5
#Mann= 6 ,-1 , 0
  1428.5     .99       0  3724.7     .08       0  4965.4     .04       0
 4978.01    .015       0 5056.03     .08       0    5719     .99       0
#XS Ineff= 3 ,-1
  3041.9  3234.7   78.24    4900 4968.67   72.04 5065.37    5100   72.97
Permanent Ineff=
       F       F       F
Bank Sta=4978.01,5056.03
XS Rating Curve= 0 ,0
Exp/Cntr=0.5,0.3

Type RM Length L Ch R = 1 ,2604.8  ,367,411,456
Node Photo=Sta 2604 Looking US.JPG
BEGIN DESCRIPTION:
Interpolated Channel - LIDAR overbanks
VICTORY - XS 1
END DESCRIPTION:
XS GIS Cut Line= 6
      3090826.48     13880923.93      3089650.68     13880892.32
      3086895.82     13879759.39      3086495.02     13880411.73
      3085285.64     13883553.95      3085011.72     13885007.94
#Sta/Elev= 30
  1426.3   79.78  2602.5   79.24  2702.5   76.64  3152.5   79.26  3202.5   71.69
  3222.5   70.96  3282.5   78.24  3762.5   76.92  3972.5   78.29  4082.5   76.21
  4922.5   73.71 4964.64   73.68 4964.64    70.6 4989.14   58.35 5021.14   55.85
 5059.14   58.35 5082.64    70.1 5082.64   73.72  5731.3   73.24  5961.3   76.28
  6181.3   73.25  6251.3    75.1  6311.3   72.51  6506.9   76.24  7940.3   73.89
  9000.3    79.4  9070.3   77.18  9863.8   79.24  9913.8   77.44 11193.4    80.1
#Mann= 6 ,-1 , 0
  1426.3     .99       0  3762.5     .08       0  4922.5     .04       0
 4964.64    .015       0 5082.64     .08       0  5731.3     .99       0
#XS Ineff= 1 ,-1
    3152    3283    78.4
Permanent Ineff=
       F
Bank Sta=4964.64,5082.64
XS Rating Curve= 0 ,0
Exp/Cntr=0.3,0.1

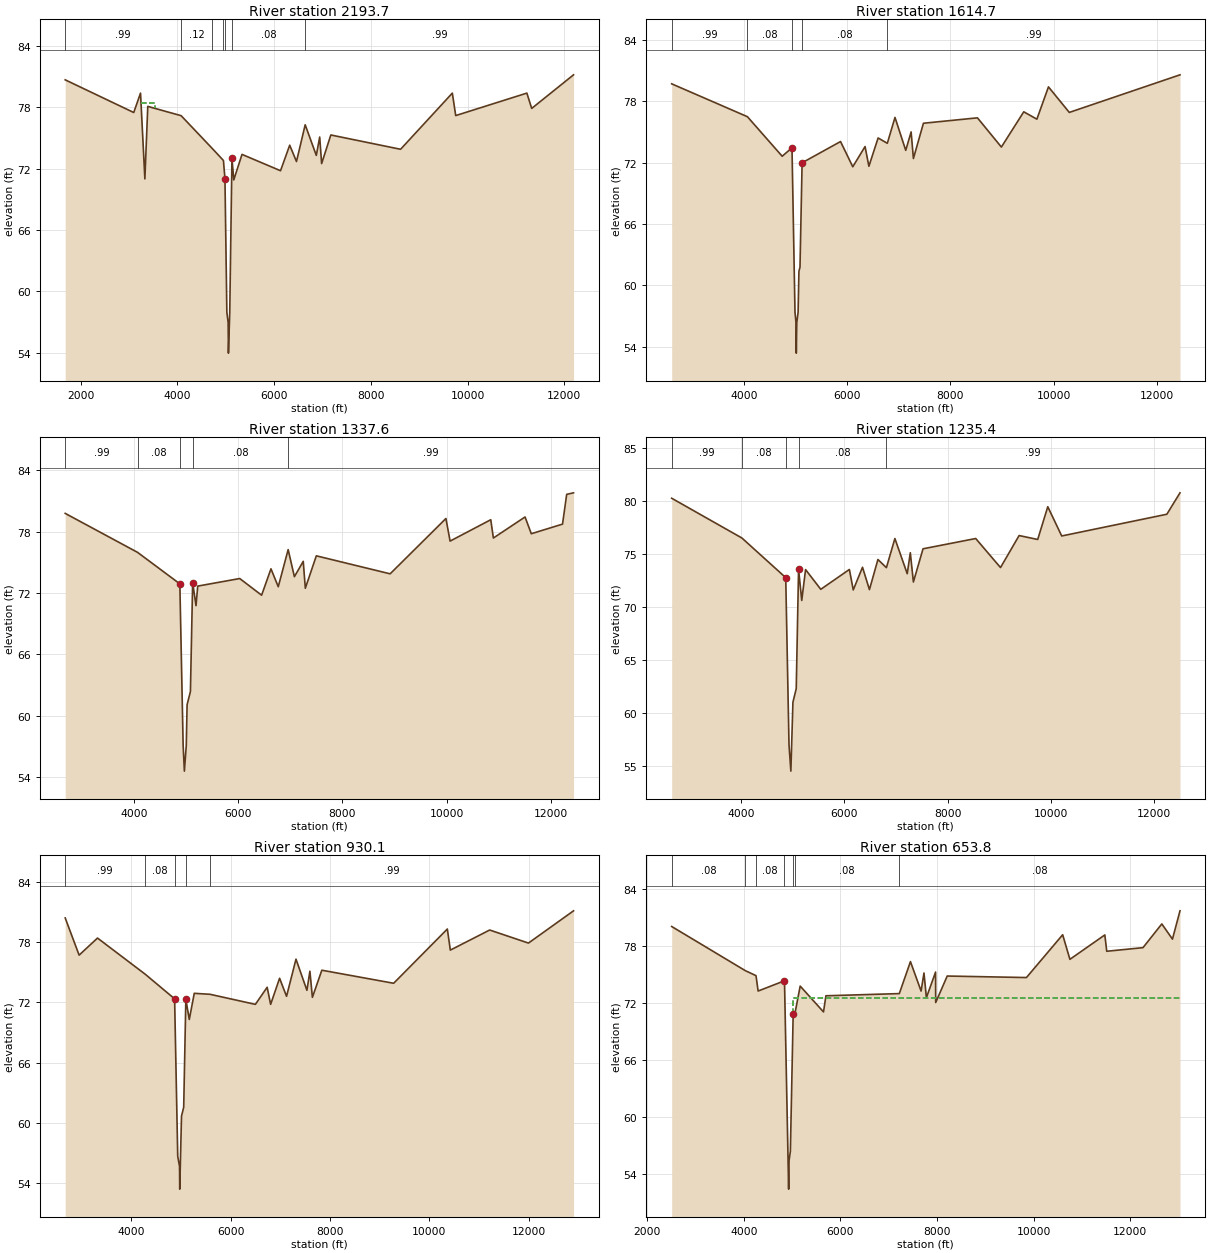
Type RM Length L Ch R = 1 ,2193.7  ,628,579,522
Node Photo=Sta 2193 Looking US.JPG
BEGIN DESCRIPTION:
Cross Section X03
END DESCRIPTION:
XS GIS Cut Line= 6
      3090688.54     13880849.44      3087888.78     13880092.41
      3087561.13     13879430.25      3087141.81     13879340.54
      3085284.51     13883554.18      3084953.76     13885311.94
#Sta/Elev= 30
    1679    80.7  3096.4    77.5  3236.4    79.4  3326.4      71  3386.4    78.1
    4076   77.19  4717.4   73.99    4951    72.8 4982.32   71.01 5021.53   57.94
  5048.1   56.94  5054.1   53.94 5081.53   57.94 5126.71      73  5164.7    70.9
  5334.7    73.4  6131.3    71.8  6321.3    74.3  6461.3    72.7  6641.3    76.3
  6871.3    73.3  6941.3    75.1  6981.3    72.5  7171.3    75.3    8614    73.9
    9684    79.4    9754    77.2 11225.2    79.4 11325.2    77.9   12190   81.19
#Mann= 7 ,-1 , 0
    1679     .99       0    4076     .12       0  4717.4     .05       0
    4951     .04       0 4982.32    .045       0 5126.71     .08       0
  6641.3     .99       0
#XS Ineff= 1 ,-1
  3236.4  3536.4    78.4
Permanent Ineff=
       F
Bank Sta=4982.32,5126.71
XS Rating Curve= 0 ,0
Exp/Cntr=0.3,0.1

Type RM Length L Ch R = 1 ,1614.7  ,309,277,225
Node Photo=Sta 1614 Looking DS.JPG
XS GIS Cut Line= 6
      3090561.22     13879461.683087543.54000001     13879279.43
3087145.63999999     13879309.713086448.92000003     13880486.96
      3085287.42     13883532.423084954.69000003     13885286.34
#Sta/Elev= 30
 2602.79   79.73  4070.4   76.51 4743.48   72.64  4933.5   73.47 4991.64   57.37
 5010.59   56.37 5016.59   53.37 5026.59   56.37 5051.64   57.37 5067.64   61.37
 5088.39   61.78 5129.28      72 5873.88   74.08  6110.8   71.61 6348.71   73.59
 6423.05   71.66 6601.48   74.43 6779.91   73.91 6928.61   76.44 7136.77   73.22
 7240.86   75.02 7285.47   72.42 7479.18   75.87 8525.79    76.4 8989.29   73.54
 9422.89   76.99 9677.07   76.27 9901.35   79.4310305.04   76.9312449.14   80.61
#Mann= 5 ,-1 , 0
 2602.79     .99       0  4070.4     .08       0  4933.5    .045       0
 5129.28     .08       0 6779.91     .99       0
Bank Sta=4933.5,5129.28
XS Rating Curve= 0 ,0
Exp/Cntr=0.3,0.1

Type RM Length L Ch R = 1 ,1337.6  ,104,102,104
BEGIN DESCRIPTION:
Interpolated Channel - LIDAR overbanks
CYPRESS GROVE (FOOTBRIDGE) - XS 1 and PIPELINE - XS 4
END DESCRIPTION:
XS GIS Cut Line= 6
      3090473.04     13879220.61      3088249.81     13879079.35
      3087142.07     13879276.63      3086443.74     13880494.29
      3085282.26     13883531.63      3084954.21     13885258.44
#Sta/Elev= 30
  2672.5   79.79  4062.5   75.98 4875.36    72.9 4938.58   57.09 4962.54   54.59
 4998.58   57.09 5014.58   61.09 5078.51   62.37 5121.16   73.03  5186.1   70.77
  5218.9   72.68  6026.2   73.42  6446.2   71.79  6626.2   74.37  6766.2   72.62
  6956.2   76.25  7076.2    73.6  7246.2    75.1  7286.2   72.47  7497.6   75.64
  8915.6   73.88  9987.7   79.29 10067.7   77.08 10849.3   79.17 10899.3   77.38
   11508   79.44   11628    77.8   12228   78.74   12308   81.65 12439.5    81.8
#Mann= 5 ,-1 , 0
  2672.5     .99       0  4062.5     .08       0 4875.36    .045       0
 5121.16     .08       0  6956.2     .99       0
Bank Sta=4875.36,5121.16
XS Rating Curve= 0 ,0
Exp/Cntr=0.3,0.1

Type RM Length L Ch R = 1 ,1235.4  ,290,305,335
XS GIS Cut Line= 6
      3090464.27     13879148.543088260.65772328 13878976.064218
3087186.40000004     13879212.54      3086424.67     13880527.98
3085289.65000001     13883481.933084944.82999998     13885288.55
#Sta/Elev= 30
 2657.91   80.23 4016.98   76.48 4865.94   72.74 4928.97   56.99    4965   54.49
 5004.97   60.99 5069.03   62.27 5114.08   73.53 5175.75   70.59 5249.43    73.5
 5544.14   71.64 6098.03   73.51 6172.65   71.58 6351.75   73.72 6486.07   71.61
 6650.25   74.45 6814.42   73.68 6978.59   76.43 7217.39   73.11 7277.09   75.09
 7336.79   72.33 7523.39   75.46 8543.22   76.43 9023.14   73.69 9383.08   76.71
 9743.02   76.34 9937.99   79.4310207.95   76.6712242.83   78.7212497.27   80.74
#Mann= 5 ,-1 , 0
 2657.91     .99       0 4016.98     .08       0 4865.94    .045       0
 5114.08     .08       0 6814.42     .99       0
Bank Sta=4865.94,5114.08
XS Rating Curve= 0 ,0
Exp/Cntr=0.3,0.1

Type RM Length L Ch R = 1 ,930.1   ,284,276,280
Node Photo=Sta 930-Looking US.JPG
BEGIN DESCRIPTION:
Cross Section X02
W LITTLE YORK - XS 4 and PIPELINE - XS 1
(Ineffective Deleted-Atkins)
END DESCRIPTION:
XS GIS Cut Line= 6
      3090435.67     13879115.16       3088436.6     13878716.61
      3087492.33     13878587.45      3086439.62     13880485.32
      3085286.25     13883481.21      3084941.32      13885303.5
#Sta/Elev= 30
  2674.3    80.4  2954.3    76.7  3324.3    78.4  4284.3    74.8 4875.46   72.35
 4938.14   56.68 4974.16   55.68  4978.7   53.41 5014.14   60.68 5058.25   61.56
 5101.24    72.3  5170.7    70.3  5270.7    72.9  5590.2    72.8  6500.2    71.8
  6737.3    73.5  6807.3    71.8  6987.3    74.4  7127.3    72.6  7317.3    76.3
  7537.3    73.2  7597.3    75.1  7647.3    72.5  7837.3    75.2  9282.4    73.9
 10362.4    79.3 10422.4    77.2 11214.1    79.2 11994.1    77.9   12901   81.11
#Mann= 5 ,-1 , 0
  2674.3     .99       0  4284.3     .08       0 4875.46    .045       0
 5101.24     .08       0  5590.2     .99       0
Bank Sta=4875.46,5101.24
XS Rating Curve= 0 ,0
Exp/Cntr=0.5,0.3

Type RM Length L Ch R = 1 ,653.8   ,76,76,76
BEGIN DESCRIPTION:
Upstream Section of Bridge/Culvert/Weir
W LITTLE YORK - XS 3
END DESCRIPTION:
XS GIS Cut Line= 6
      3090674.33     13878499.73      3088900.94     13878441.47
      3087587.56     13878378.99      3086417.73     13880516.18
      3085284.45     13883479.96      3084943.59     13885283.06
#Sta/Elev= 30
  2505.7   80.07  4029.4   75.42  4251.8   74.89  4295.4   73.27 4841.28   74.35
 4927.28    52.4 4935.74    55.4 4963.17    56.4 5020.92   70.84  5055.1   70.84
  5166.2   73.79  5648.9   71.07  5698.9   72.77  7218.4      73  7448.9   76.37
  7668.9   73.27  7728.9   75.17  7778.9   72.57  7968.9   75.27  7971.5   72.06
    8210   74.85    9850   74.69   10600    79.2   10750   76.61 11472.7   79.18
 11512.7   77.46 12262.7   77.84 12652.7   80.34 12872.7   78.74 13028.9   81.72
#Mann= 7 ,-1 , 0
  2505.7     .08       0  4029.4     .12       0  4251.8     .08       0
 4841.28    .045       0 5020.92     .04       0  5055.1     .08       0
  7218.4     .08       0
#XS Ineff= 2 , 0
       0 4832.09   73.75 5024.78       0    72.5
Permanent Ineff=
       F       F
Bank Sta=4841.28,5020.92
XS Rating Curve= 0 ,0
Exp/Cntr=0.5,0.3

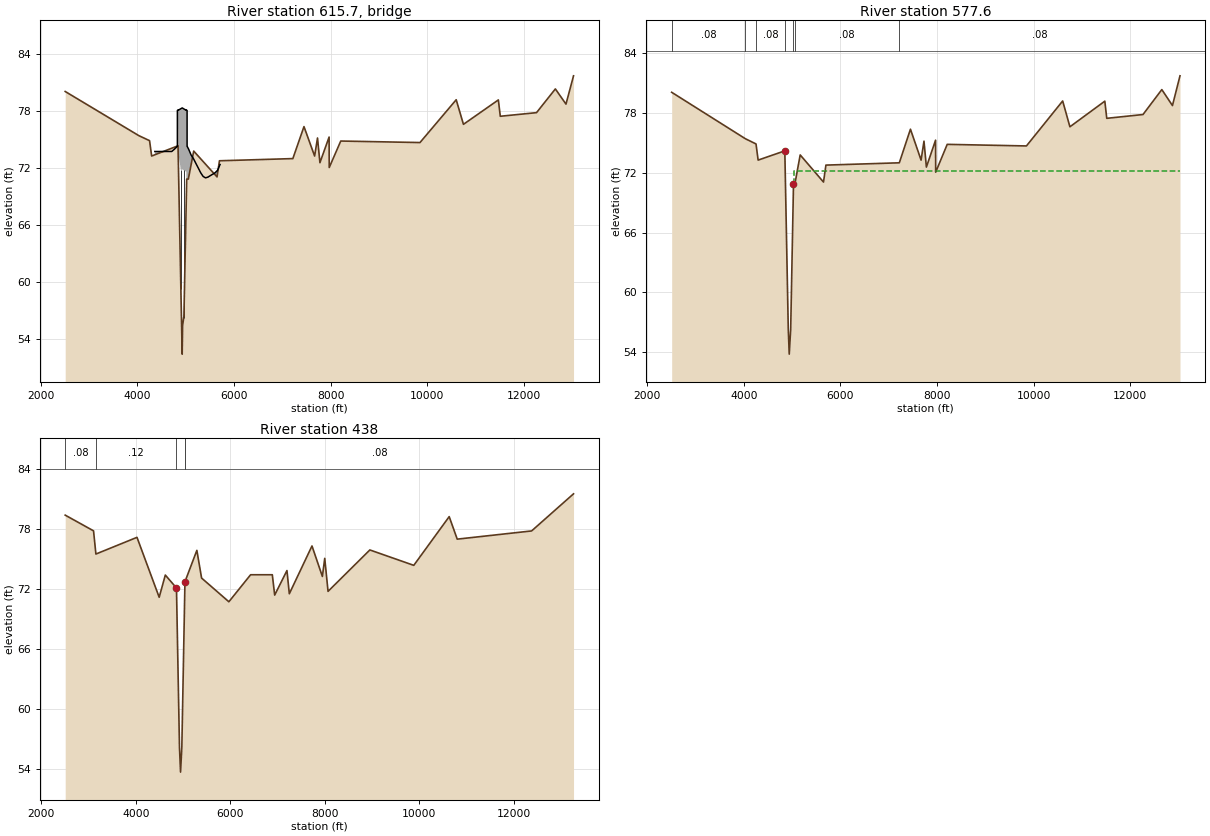
Type RM Length L Ch R = 3 ,615.7   ,,,
BEGIN DESCRIPTION:
W LITTLE YORK
Structure ID: E121-00-00-01
END DESCRIPTION:
Bridge Culvert--1,0,-1,-1, 0
Deck Dist Width WeirC Skew NumUp NumDn MinLoCord MaxHiCord MaxSubmerge Is_Ogee
12,58,2.6,0, 37, 37, , , 0.95, 0, ,,,
 4361.11 4411.11 4461.11 4511.11 4561.11 4611.11 4661.11 4711.11 4761.11 4811.11
 4824.09 4827.89 4827.99 4843.99 4844.09 4900.28 4928.51 4956.53 5012.78 5012.88
 5028.88 5028.98 5032.84 5061.11 5111.11 5161.11 5211.11 5261.11 5311.11 5361.11
 5411.11 5461.11 5511.11 5561.11 5611.11 5661.11 5711.11
   73.75   73.75   73.75   73.75   73.75   73.75   73.75   73.75   73.97   74.21
   74.28   74.29   78.08   78.13   78.09   78.26   78.34   78.25   78.08   78.12
   78.07   74.28   74.27   73.99   73.39   72.99   72.49      72    71.5   71.12
   70.97   71.05   71.21   71.36   71.52   71.78   72.38
   48.75   48.75   48.75   48.75   48.75   48.75   48.75   48.75   48.97   49.21
   49.28   49.29   53.08   53.13   71.62   71.78   71.87   71.78   71.61   53.12
   53.07   49.28   49.27   48.99   48.39   47.99   47.49      47    46.5   46.12
   45.97   46.05   46.21   46.36   46.52   46.78   47.38
 4373.21 4423.21 4473.21 4523.21 4573.21 4623.21 4673.21 4723.21 4773.21 4823.21
 4836.19 4839.99 4840.09 4856.09 4856.19 4912.38 4940.61 4968.63 5024.88 5024.98
 5040.98 5041.08 5044.94 5073.21 5123.21 5173.21 5223.21 5273.21 5323.21 5373.21
 5423.21 5473.21 5523.21 5573.21 5623.21 5673.21 5723.21
   73.75   73.75   73.75   73.75   73.75   73.75   73.75   73.75   73.97   74.21
   74.28   74.29   78.08   78.13   78.09   78.26   78.34   78.25   78.08   78.12
   78.07   74.28   74.27   73.99   73.39   72.99   72.49      72    71.5   71.12
   70.97   71.05   71.21   71.36   71.52   71.78   72.38
   48.75   48.75   48.75   48.75   48.75   48.75   48.75   48.75   48.97   49.21
   49.28   49.29   53.08   53.13   71.62   71.78   71.87   71.78   71.61   53.12
   53.07   49.28   49.27   48.99   48.39   47.99   47.49      47    46.5   46.12
   45.97   46.05   46.21   46.36   46.52   46.78   47.38
Pier Skew, UpSta & Num, DnSta & Num=  ,4900.34, 4 ,4912.44, 4 , 3 , 3 , 0 ,,
     2.5     2.5    2.75    2.75
   48.68   68.68   68.78   72.78
     2.5     2.5    2.75    2.75
   48.68   68.68   68.78   72.78
Pier Skew, UpSta & Num, DnSta & Num=  ,4956.59, 4 ,4968.69, 4 , 3 , 3 , 0 ,,
     2.5     2.5    2.75    2.75
   48.68   68.68   68.78   72.78
     2.5     2.5    2.75    2.75
   48.68   68.68   68.78   72.78
BR Coef= 1 , 1 , 0 ,0.9, 0 ,,,0.8,-1,1.2,0,
WSPro=,,,, 1 ,,,, 0 ,,,, 0 ,,,,-1 ,-1 ,-1 , 0 , 0 , 0 , 0 , 0
BC Design=,, 0 ,, 0 ,,,,,,
BC HTab HWMax=80.67
BC Use User HTab Curves=0
BC User HTab FreeFlow(D)= 0

Type RM Length L Ch R = 1 ,577.6   ,141,140,141
BEGIN DESCRIPTION:
Downstream Section of Bridge/Culvert/Weir
W LITTLE YORK - XS 2
END DESCRIPTION:
XS GIS Cut Line= 6
      3090682.12     13878423.62      3088908.76     13878365.36
      3087614.06     13878304.78      3086420.83     13880442.91
        3085278.     13883477.51      3084956.96      13885204.1
#Sta/Elev= 30
  2505.7   80.07  4029.4   75.42  4251.8   74.89  4295.4   73.27 4848.05    74.2
 4919.54   56.33 4939.61   53.82 4969.54   56.33 5027.58   70.84  5055.1   70.84
  5166.2   73.79  5648.9   71.07  5698.9   72.77  7218.4      73  7448.9   76.37
  7668.9   73.27  7728.9   75.17  7778.9   72.57  7968.9   75.27  7971.5   72.06
    8210   74.85    9850   74.69   10600    79.2   10750   76.61 11472.7   79.18
 11512.7   77.46 12262.7   77.84 12652.7   80.34 12872.7   78.74 13028.9   81.72
#Mann= 7 ,-1 , 0
  2505.7     .08       0  4029.4     .12       0  4251.8     .08       0
 4848.05    .045       0 5027.58     .04       0  5055.1     .08       0
  7218.4     .08       0
#XS Ineff= 2 , 0
       0 4853.19   72.81 5027.88       0  72.185
Permanent Ineff=
       F       F
Bank Sta=4848.05,5027.58
XS Rating Curve= 0 ,0
Exp/Cntr=0.5,0.3

Type RM Length L Ch R = 1 ,438     ,0,0,0
BEGIN DESCRIPTION:
Cross Section X01
W LITTLE YORK - XS 1
END DESCRIPTION:
XS GIS Cut Line= 6
      3090690.06     13878284.33      3088196.83     13878195.24
      3087637.07      13878160.9      3086386.26     13880469.15
      3085254.76     13883489.22      3084917.37     13885316.07
#Sta/Elev= 30
  2506.7   79.38  3106.7   77.81  3156.7   75.49  4026.7   77.16  4496.7   71.17
  4626.7   73.39 4862.78    72.1  4926.4   56.19 4949.15   53.69  4976.4   56.19
  5042.6   72.74  5046.5   72.77  5294.6   75.86  5394.6   73.09  5972.4   70.72
  6432.4   73.42  6892.4   73.42  6942.4   71.39  7202.4   73.84  7252.4   71.52
  7732.4    76.3  7952.4   73.25  8002.4   75.06  8072.4   71.76  8957.8    75.9
  9887.8   74.36 10637.8   79.23 10807.8   76.98 12382.9    77.8 13270.6   81.51
#Mann= 5 ,-1 , 0
  2506.7     .08       0  3156.7     .12       0 4862.78    .045       0
  5042.6     .04       0  5046.5     .08       0
Bank Sta=4862.78,5042.6
XS Rating Curve= 0 ,0
Exp/Cntr=0.3,0.1

Chan Stop Cuts=-1
Use User Specified Reach Order=0